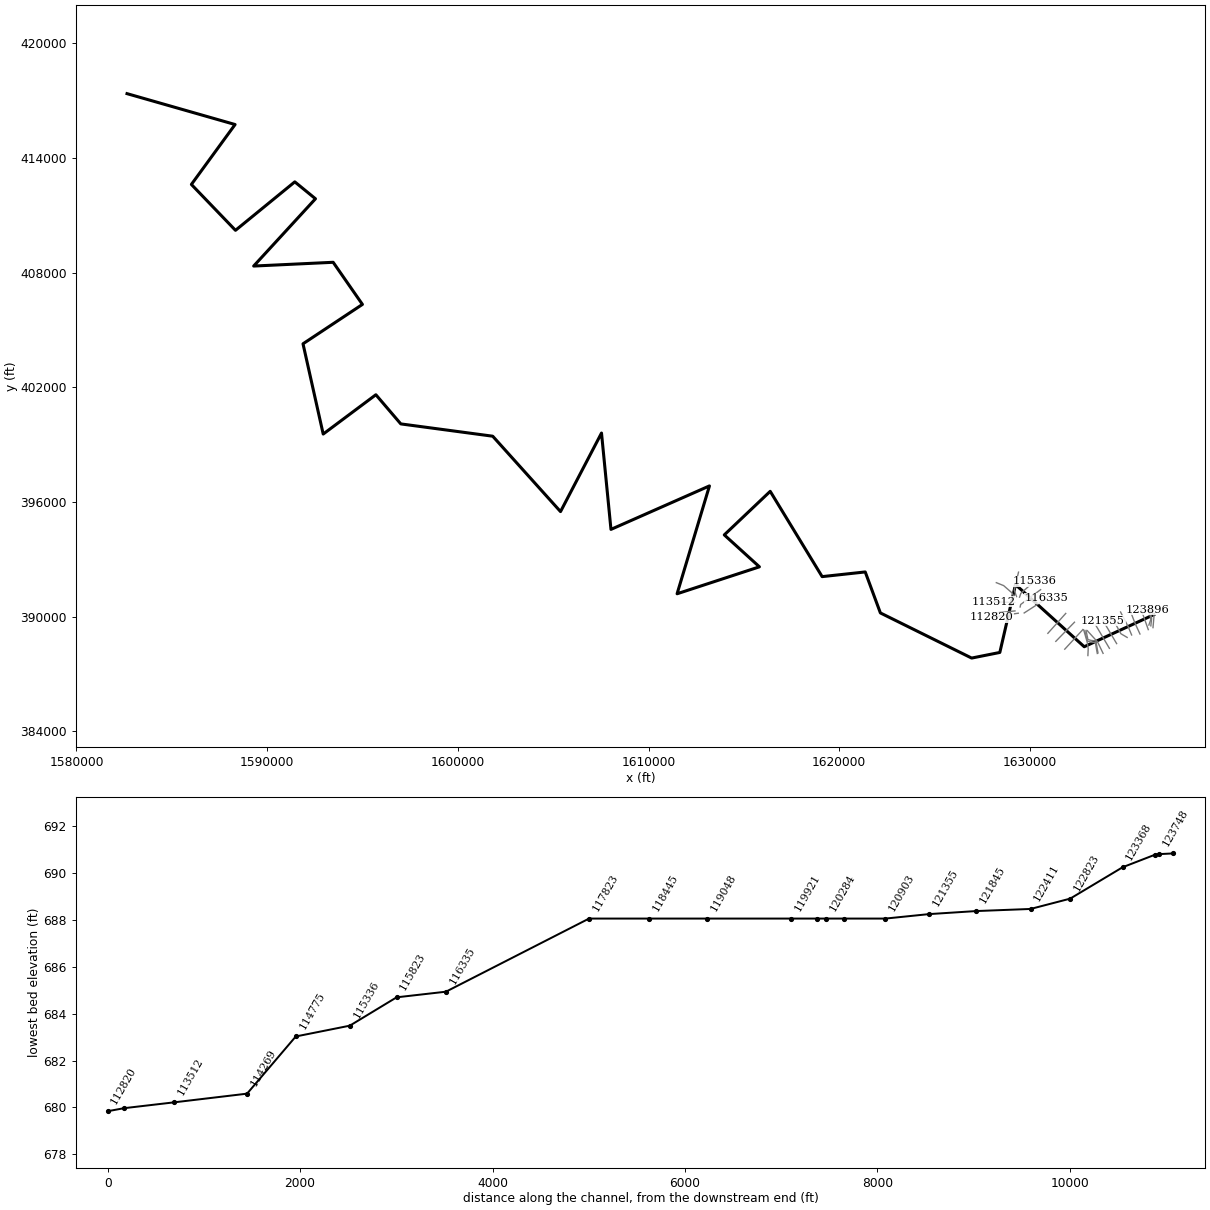
--- FISHINGCK.prj (project) ---

Proj Title=FISHINGCK
Current Plan=p01
Default Exp/Contr=0,0
English Units
Geom File=g01
Flow File=f01
Plan File=p01
BEGIN DESCRIPTION:
---------- MODELED AS PART OF WVEMD CTP PROGRAM, 2023----------
Stream Name: Fishing Creek
Flood Zone:  AFH
Wetzel County, WV
HEC-RAS Version: RAS 6.3
Vertical Datum: NAVD88
Projection: NAD 1983 StatePlane West Virginia S FIPS 4702 (US Feet)
Terrain: 1-meter West Virginia FEMA R3 South Central (collected 2018-2020)
Land Use: 2019 NLCD
Hydrologic Method:
WV 2010 Regional Regression Equations
Additional Model Notes:
DS extent connects to Floodway; XS placed at border between AFH and Floodway.
LOB on XSs 24761 and 14488 needs to be fixed by mapping; the neck/pinch at the oxbow needs to be mapped; parallel edgelines cut off the floodplain
END DESCRIPTION:
DSS Export Rating Curves= 0
DSS Export Rating Curve Sorted= 0
DSS Export Volume Flow Curves= 0
DXF OffsetX= 0
DXF OffsetY= 0
DXF ScaleX= 0
DXF ScaleY= 0

--- FISHINGCK.p01 (plan) ---

Plan Title=Floodplain
Program Version=6.31
Short Identifier=Floodplain
Geom File=g01
Flow File=f01
Subcritical Flow
K Sum by GR= 0
Std Step Tol= 0.01
Critical Tol= 0.01
Num of Std Step Trials= 20
Max Error Tol= 0.3
Flow Tol Ratio= 0.001
Split Flow NTrial= 30
Split Flow Tol= 0.02
Split Flow Ratio= 0.02
Log Output Level= 0
Friction Slope Method= 1
Unsteady Friction Slope Method= 2
Unsteady Bridges Friction Slope Method= 1
Parabolic Critical Depth
Global Vel Dist= 0 , 0 , 0
Global Log Level= 0
CheckData=True
Encroach Param=-1 ,0,0, 0
Mapping Interval=1HOUR
Computation Time Step Use Courant=        0
Computation Time Step Use Time Series=    0
Computation Time Step Count To Double=0
Computation Time Step Max Doubling=0
Computation Time Step Max Halving=0
Computation Time Step Residence Courant=0
Run HTab= 0
Run UNet= 0
Run Sediment= 0
Run PostProcess= 0
Run WQNet= 0
Run RASMapper=-1
UNET Theta= 0
UNET Theta Warmup= 0
UNET ZTol= 0
UNET ZSATol= 0
UNET MxIter= 0
UNET Max Iter WO Improvement= 0
UNET MaxInSteps= 0
UNET DtIC= 0
UNET DtMin= 0
UNET MaxCRTS= 0
UNET WFStab= 0
UNET SFStab= 0
UNET WFX= 1
UNET SFX= 1
UNET Gravity=32.17405
UNET 1D Methodology=Finite Difference
UNET DSS MLevel= 1
UNET Pardiso=0
UNET DZMax Abort= 0
UNET Use Existing IB Tables= 0
UNET Froude Reduction=False
UNET Froude Limit= 0
UNET Froude Power= 0
UNET D1 Cores= 0
UNET WindReference=Eulerian
UNET WindDragFormulation=Hsu (1988)
UNET D2 Coriolis=0
UNET D2 Cores= 0
UNET D2 Theta= 1
UNET D2 Theta Warmup= 1
UNET D2 Z Tol= 0.01
UNET D2 Volume Tol= 0.01
UNET D2 Max Iterations= 20
UNET D2 Equation= 0
UNET D2 RampUpFraction=0.1
UNET D2 TimeSlices= 1
UNET D2 Turbulence Formulation=Non-Conservative (original)
UNET D2 Eddy Viscosity=0.3
UNET D2 Transverse Eddy Viscosity=0.1
UNET D2 Smagorinsky Mixing=0
UNET D2 BCVolumeCheck=0
UNET D2 Cores=0
UNET D2 SolverType=PARDISO (Direct)
UNET D2 Minimum Iterations= 3
UNET D2 Maximum Iterations= 30
UNET D2 Restart Number= 10
UNET D2 Relaxation Coeff=1.3
UNET D2 SOR Precondition Iterations= 10
UNET D2 ILUT Maximum Fill= 8
UNET D2 ILUT Tolerance=1E-08
UNET D2 Convergence Tolerance=0.00001
UNET D1D2 MaxIter= 0
UNET D1D2 ZTol=0.01
UNET D1D2 QTol=0.1
UNET D1D2 MinQTol=1
Write IC File= 0
Write IC File at Fixed DateTime=0
Write IC File at Sim End=0
Echo Input=False
Echo Parameters=False
Echo Output=False
Write Detailed= 0
HDF Write Warmup=0
HDF Write Time Slices=0
HDF Flush=0
HDF Compression= 1
HDF Chunk Size= 1
HDF Spatial Parts= 1
HDF Use Max Rows=0
HDF Fixed Rows= 1
Calibration Method= 0
Calibration Iterations= 20
Calibration Max Change=0.05
Calibration Tolerance=0.2
Calibration Maximum=1.5
Calibration Minimum=0.5
Calibration Optimization Method= 1
WQ AD Non Conservative
WQ ULTIMATE=-1
WQ Max Comp Step=1HOUR
WQ Output Interval=15MIN
WQ Output Selected Increments= 0
WQ Create Restart=0
WQ Fixed Restart=0
WQ System Summary=0
WQ Write To DSS=0
Sorting and Armoring Iterations= 10
XS Update Threshold= 0.02
Bed Roughness Predictor= 0
Hydraulics Update Threshold= 0.02
Energy Slope Method= 1
Volume Change Method= 1
Sediment Retention Method= 0
Sediment TS Multiplier= 1
Warm Up Method= 0
XS Weighting Method= 0
Number of US Weighted Cross Sections= 1
Number of DS Weighted Cross Sections= 1
Upstream XS Weight=0
Main XS Weight=1
Downstream XS Weight=0
Number of DS XS's Weighted with US Boundary= 1
Upstream Boundary Weight= 1
Weight of XSs Associated with US Boundary= 0
Number of US XS's Weighted with DS Boundary= 1
Downstream Boundary Weight= 0.5
Weight of XSs Associated with DS Boundary= 0.5
Percentile Method= 0
Sediment Output Level= 3
Mass or Volume Output= 0
Output Increment Type= 1
Profile and TS Output Increment= 1
Transport Output Increment 1
XS Output Flag= 0
XS Output Increment= 10
Read HDF5 Sediment Hotstart= 0
Sediment Hotstart Type= 0
Write Gradation File= 0
Read Gradation Hotstart= 0
Write HDF5 File= 1
Write Binary Output= 1
Write DSS Sediment File= 0
DSS Sediment Output Type= 1
SV Curve= 0
Specific Gage Flag= 0
Subcell Erosion Methods= 0
Subcell Deposition Methods= 0
Advection Scheme= 1
Matrix Solver= 0
Implicit Weighting Factor= 1
Maximum Outer Loop Convergence Iterations= 5
Convergence Maximum Absolute= 0.001
Convergence RMSE= 0.0001
Grain Fractions Max Abs Error= 0.001
Max Subgrid Regions= 1
Max Subgrid Length Scale= 3.402823E+38
Initial Layer Thickness= 3.402823E+38
Min Layer Thickness= 3.402823E+38
Max Layer Thickness= 3.402823E+38
Number of Layers= 5

--- FISHINGCK.f01 (steady flow) ---

Flow Title=Flow
Program Version=6.31
Number of Profiles= 1
Profile Names=F01pct
River Rch & RM=FISHINGCK,Main,123896
   13900
River Rch & RM=FISHINGCK,Main,114269
   15700
River Rch & RM=FISHINGCK,Main,101860
   17500
River Rch & RM=FISHINGCK,Main,30845
   20500
Boundary for River Rch & Prof#=FISHINGCK,Main            , 1
Up Type= 0
Dn Type= 3
Dn Slope=0.00074
DSS Import GetInterval= 0
DSS Import GetPeak= 0
DSS Import FillOption= 0

--- FISHINGCK.g01 (geometry) ---

Geom Title=Geometry
Program Version=6.31

River Reach=FISHINGCK       ,Main
Reach XY= 30
     1636493.101      390104.613     1632845.683      388427.798
     1629242.612      391678.878     1628419.448      388128.466
     1626942.189      387834.677     1622156.644      390196.075
     1621361.973      392340.624     1619102.126      392095.837
     1616379.312      396558.768      1613971.13      394278.633
     1615813.464       392608.47     1611495.986      391198.284
     1613193.532      396842.579     1608028.833      394566.878
     1607532.718      399608.408     1605383.757      395497.739
      1601828.17      399442.715      1597007.92      400086.399
     1595701.254      401612.168     1592939.203      399555.104
      1591880.02      404277.723     1594996.267      406338.192
     1593461.395      408542.023     1589293.228      408345.121
     1592533.817      411865.644     1591449.667      412750.519
     1588339.555      410214.509     1586026.543      412615.297
     1588318.301      415750.251     1582651.755       417365.94

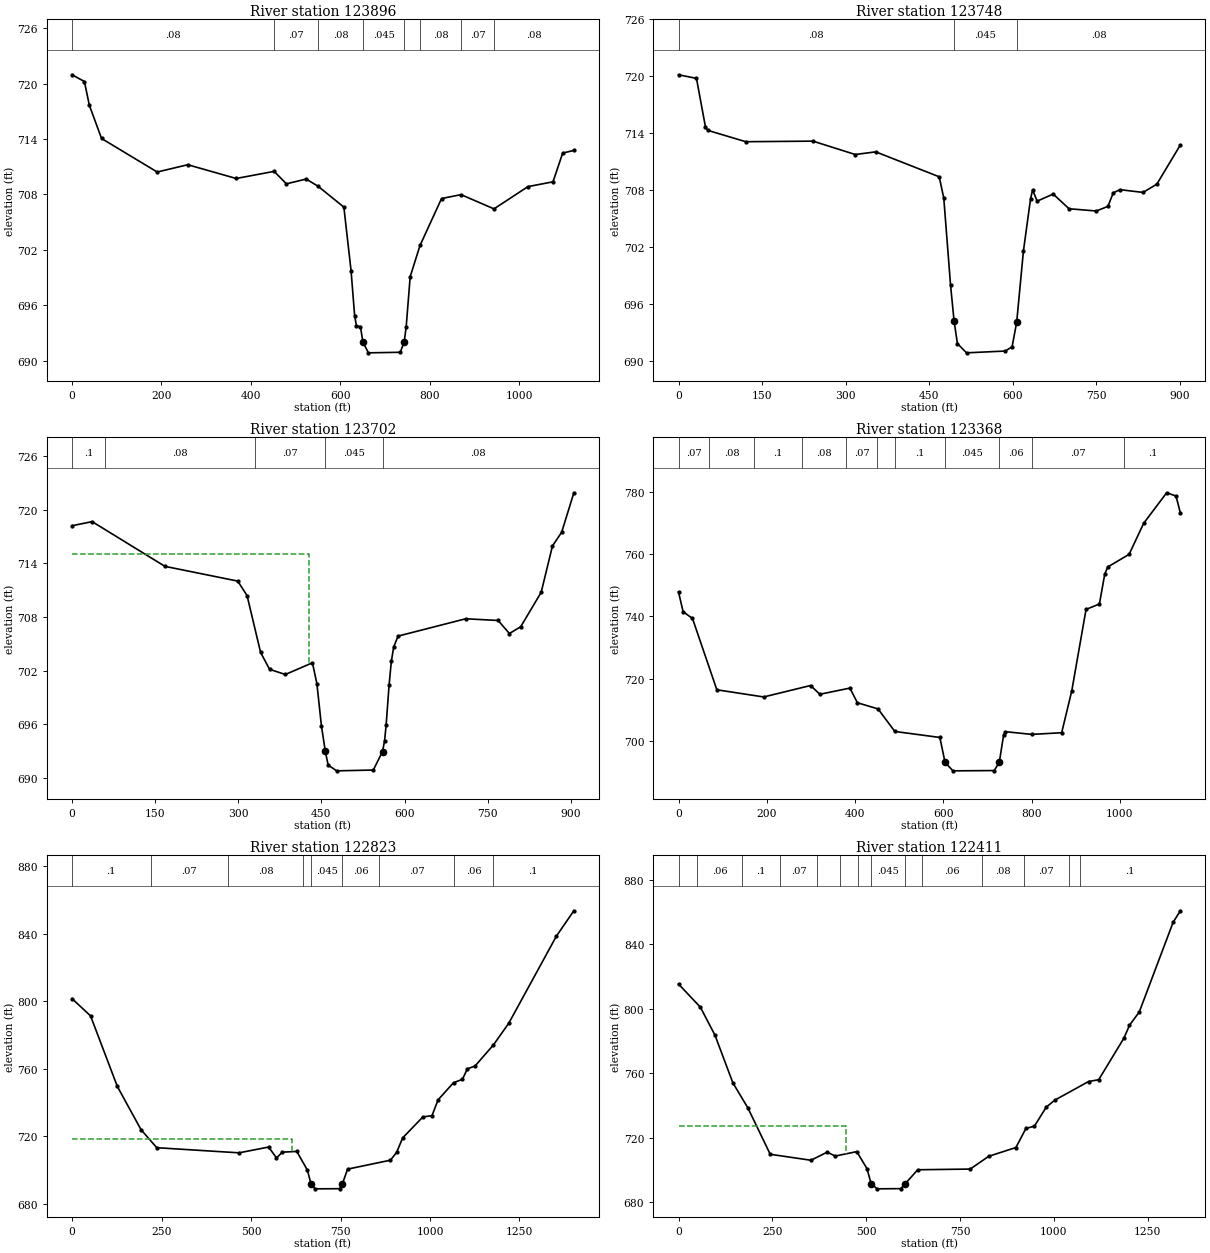
Type RM Length L Ch R = 1 ,123896  ,157.5,148.2,132
XS GIS Cut Line= 5
1636451.97444457389426.753403418 1636507.5766169390060.061015926
1636449.44571555390179.1117490661636402.56941026390284.689533684
1636180.83817379390373.676511169
#Sta/Elev= 30
       0  720.95    27.6  720.22    38.7  717.64      66  714.05   190.5  710.42
   258.8  711.21   367.2  709.72   452.1  710.49   479.6  709.14   523.8  709.66
   550.4  708.88   608.1  706.62   624.2  699.75   632.2  694.87   636.3  693.75
   645.2  693.68   650.7  692.01     663  690.84   734.2   690.9   743.1     692
   747.6  693.69   756.5  699.09   778.5  702.47   826.7  707.55   870.3  707.97
     944  706.43    1020  708.84    1076  709.36  1097.7  712.47  1122.7  712.76
#Mann= 8 ,-1,0
       0     .08       0   452.1     .07       0   550.4     .08       0
   650.7    .045       0   743.1     .07       0   778.5     .08       0
   870.3     .07       0     944     .08       0
Bank Sta=650.7,743.1
XS Rating Curve= 0 ,0
Exp/Cntr(USF)=0,0
Exp/Cntr=0.3,0.1

Type RM Length L Ch R = 1 ,123748  ,47.1,46.4,46
XS GIS Cut Line= 4
1636338.61614445389520.5314132661636378.76531905389905.524973803
1636301.38632123390274.4783962591636189.19121273390352.191101435
#Sta/Elev= 30
       0  720.14    32.2  719.76    48.3  714.64    52.3  714.28   120.7  713.08
   241.3  713.14   317.1  711.73   353.9  712.01   467.8  709.38     476  707.13
   488.2  697.92  494.49694.1606   500.5  691.79   516.8  690.81   586.3     691
   598.6  691.45   606.8  694.03     619  701.58   631.7  707.05   635.4  707.99
   643.6  706.81   672.3  707.56   700.8  706.01   749.8  705.77   770.5  706.26
   780.2  707.69   792.3  708.02   833.7  707.73   858.4  708.61   900.5  712.73
#Mann= 3 ,-1,0
       0     .08       0  494.49    .045       0   606.8     .08       0
Bank Sta=494.49,606.8
XS Rating Curve= 0 ,0
Exp/Cntr(USF)=0,0
Exp/Cntr=0.3,0.1

Type RM Length L Ch R = 1 ,123702  ,327.4,333.4,344.4
XS GIS Cut Line= 4
1636235.08897371389562.3907271611636337.89178058  389855.2190803
1636256.14470364390293.8235892781636110.45552517390325.357796356
#Sta/Elev= 30
       0  718.23    36.2  718.69   167.6  713.68     299  712.03   315.8  710.41
   340.2  704.05   356.4  702.15   384.9  701.57   433.8  702.88   441.9  700.52
     450  695.83  457.07692.9468   462.2  691.42   477.6  690.78   543.6  690.87
   560.3692.9391     564  694.15   566.8   695.9   572.1  700.37   576.2  703.05
   580.5  704.66   588.4  705.87   710.4  707.81   768.9  707.62   789.3  706.16
   809.7  706.92   846.6  710.77     867  715.97   883.6   717.5   905.6  721.92
#Mann= 5 ,-1,0
       0      .1       0      60     .08       0  330.35     .07       0
  457.07    .045       0   560.3     .08       0
#XS Ineff= 2 , 0
          428.04  715.08
Permanent Ineff=
       F       F
Bank Sta=457.07,560.3
XS Rating Curve= 0 ,0
Exp/Cntr(USF)=0,0
Exp/Cntr=0.3,0.1

Type RM Length L Ch R = 1 ,123368  ,544.4,545.3,548.6
XS GIS Cut Line= 2
1636204.23581146389322.7319465771635823.26125218390393.773632096
#Sta/Elev= 30
       0  747.87    10.4  741.53    31.6  739.37    86.8  716.37     193  714.06
     299  717.75   320.3  714.93   388.3  716.92   405.2  712.19   451.9  710.22
     490  702.94     592  701.01  603.72  693.03   621.6  690.25   715.2  690.34
  726.64     693   736.4  701.73   740.6  702.87     800     702     868  702.53
   890.9  716.06   923.2  742.27   953.5  744.03   965.6  753.67   972.3  755.95
  1020.8  760.03  1053.7  770.02  1105.8  779.87    1127  778.83  1136.8  773.42
#Mann= 11 ,-1,0
       0     .07       0      70     .08       0     170      .1       0
     280     .08       0     380     .07       0     450     .06       0
     490      .1       0  603.72    .045       0  726.64     .06       0
     800     .07       0    1010      .1       0
Bank Sta=603.72,726.64
XS Rating Curve= 0 ,0
Exp/Cntr(USF)=0,0
Exp/Cntr=0.3,0.1

Type RM Length L Ch R = 1 ,122823  ,407.7,411.7,417.3
XS GIS Cut Line= 6
1635768.53705792389093.755247086 1635643.3663765389364.062121168
1635563.62112917389537.6018003371635527.57559758389617.475656345
1635497.65866268389686.3177102511635226.77206534390386.107977346
#Sta/Elev= 30
       0   801.6    51.6  791.43   126.5  749.58   192.6     724   236.7  713.29
   466.6  710.25   549.1  713.68   571.1  707.24   587.5  710.65   627.8  711.08
   657.6  699.93   667.4691.8564   679.2  688.91   747.2     689  755.24691.8617
   769.7  700.59   889.5  705.89     907   710.6   923.5   719.1   979.9  731.48
  1005.7  732.33  1022.4  741.62  1065.7  751.82  1090.5   753.8  1104.3  760.01
  1125.8   761.7  1177.1  774.19  1220.1  787.07  1353.3  838.75  1401.9  853.71
#Mann= 9 ,-1,0
       0      .1       0  219.24     .07       0  434.95     .08       0
   646.5    .025       0   667.4    .045       0  755.24     .06       0
  856.56     .07       0 1067.81     .06       0 1174.68      .1       0
#XS Ineff= 2 , 0
          614.23  718.34
Permanent Ineff=
       F       F
Bank Sta=667.4,755.24
XS Rating Curve= 0 ,0
Exp/Cntr(USF)=0,0
Exp/Cntr=0.3,0.1

Type RM Length L Ch R = 1 ,122411  ,564.2,565.8,574.4
XS GIS Cut Line= 3
1635331.33615208389042.8121161891635159.42248306389457.588109864
1634750.61227891 390245.56127508
#Sta/Elev= 30
       0  815.46    58.2  801.11    97.1  783.74   144.8  754.16   184.4  738.79
   244.3   709.9   352.8  706.19   395.9  711.22   417.5   708.8   474.8  711.55
   501.9  701.04     513  691.76   528.9  688.47     592   688.6  604.43  691.78
   637.1   700.3     777  700.73   826.3  708.65   898.7   714.1   925.4  725.92
     948  727.34   979.5  739.13  1002.1  743.44  1092.2  755.02  1119.2  756.14
  1186.5  781.95  1201.3  789.91  1227.4  798.17  1317.5  853.75  1336.7   860.9
#Mann= 14 ,-1,0
       0      .1       0      50     .06       0     170      .1       0
     270     .07       0     370     .08       0     430     .07       0
  478.99     .06       0     513    .045       0  604.43      .1       0
  648.99     .06       0  808.99     .08       0  918.99     .07       0
 1038.99     .06       0 1068.99      .1       0
#XS Ineff= 2 , 0
          445.81  727.72
Permanent Ineff=
       F       F
Bank Sta=513,604.43
XS Rating Curve= 0 ,0
Exp/Cntr(USF)=0,0
Exp/Cntr=0.3,0.1

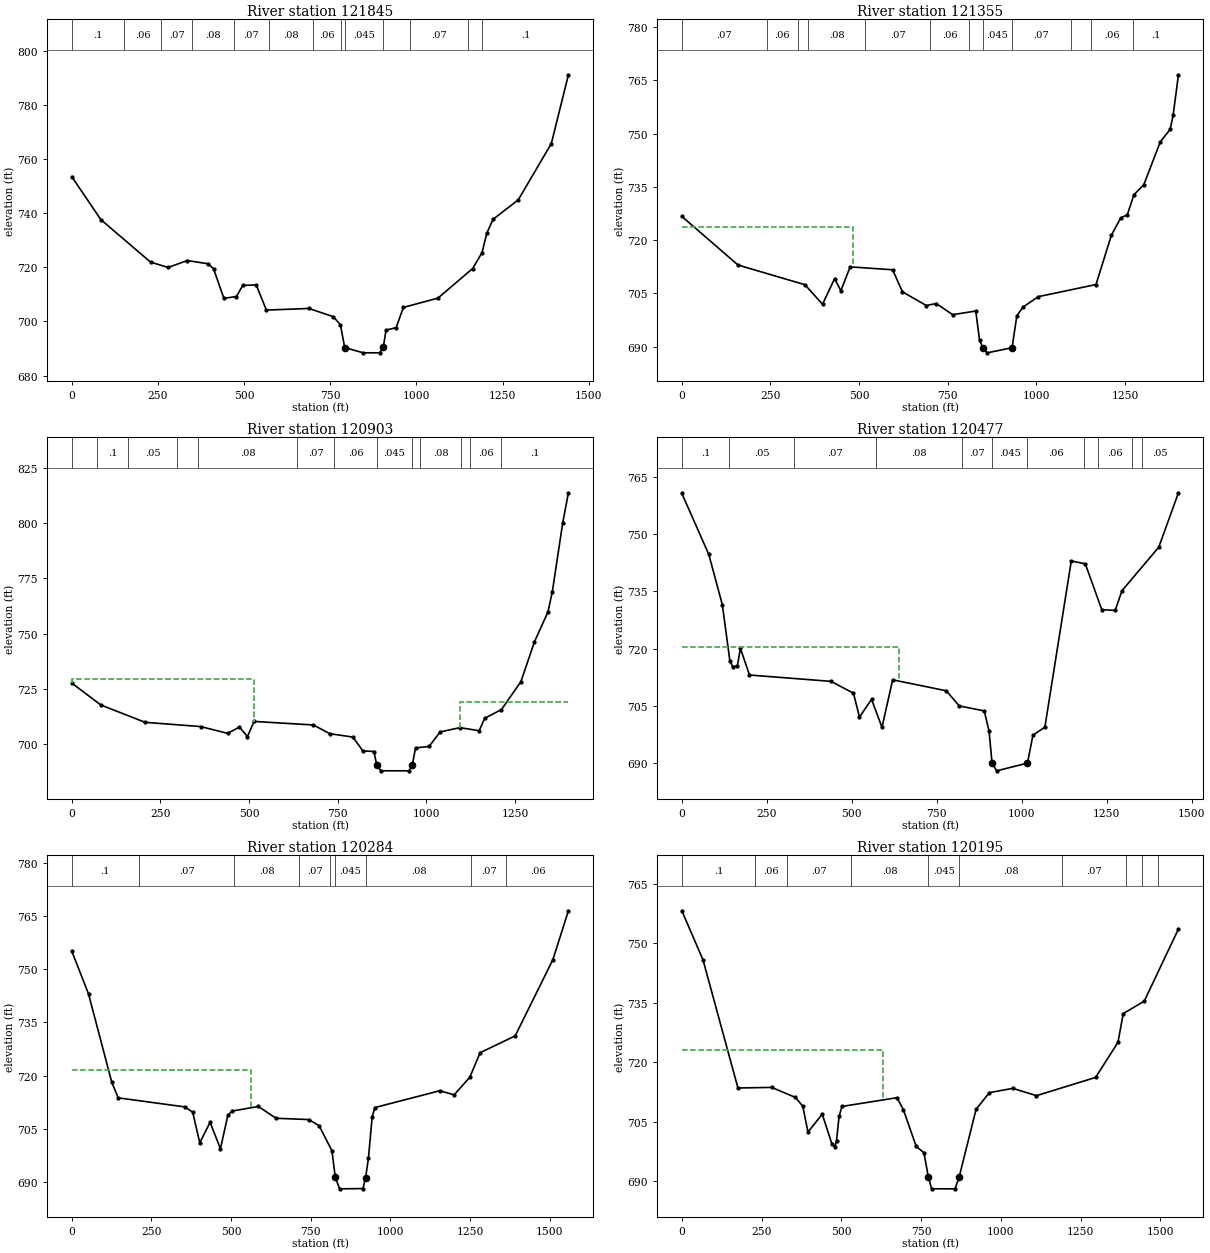
Type RM Length L Ch R = 1 ,121845  ,488.6,490.1,485.4
XS GIS Cut Line= 3
1635096.89502142 388914.38078685 1634768.6258478389107.825121305
1634256.68225561390035.967130052
#Sta/Elev= 30
       0  753.47    84.5  737.59   228.4  721.92   279.5  719.93   335.2   722.5
   395.5  721.29   411.4  719.45   441.2  708.52   477.8   709.2     496  713.29
     535   713.5   564.6  704.18   687.9  704.78   758.5  701.76   779.3  698.79
   791.9 690.337   845.9  688.38   893.5   688.4  903.81   690.4   911.7  696.78
   941.3  697.71     962  705.16  1062.5  708.61    1163  719.53  1190.4  725.41
  1204.1  732.62  1222.4  737.72  1295.5  744.93  1391.4  765.72    1441  791.15
#Mann= 13 ,-1,0
       0      .1       0     150     .06       0     260     .07       0
     350     .08       0  471.03     .07       0  571.03     .08       0
  701.03     .06       0  781.03     .07       0   791.9    .045       0
  903.81     .06       0  981.03     .07       0 1151.03     .05       0
 1191.03      .1       0
Bank Sta=791.9,903.81
XS Rating Curve= 0 ,0
Exp/Cntr(USF)=0,0
Exp/Cntr=0.3,0.1

Type RM Length L Ch R = 1 ,121355  ,451.9,452,451.8
XS GIS Cut Line= 6
1634544.88825986388590.984657561 1634443.6571631388762.112924224
1634080.10113169389376.6960126511634032.36927177389457.385155728
1633983.04653578389540.7642540691633831.69742902389796.616104564
#Sta/Elev= 30
       0  726.68   158.6  712.98   347.2  707.44   396.8  701.94     431  709.16
   448.5  705.73   474.8  712.47   594.5  711.65   622.2  705.44   689.6  701.58
   717.5  702.14     764     699   829.1  700.03   839.8  691.75   849.2689.7037
   861.6  688.25  931.57   689.7   944.9  698.67   962.4  701.15  1005.7  704.08
  1168.3  707.49  1211.4  721.32    1238  726.27  1256.6  727.14  1275.2  732.79
  1303.1   735.6  1349.6  747.68  1377.5  751.23  1385.8  755.18  1400.8  766.58
#Mann= 12 ,-1,0
       0     .07       0  238.83     .06       0  327.27     .07       0
  357.27     .08       0  517.89     .07       0  700.39     .06       0
  810.39     .07       0   849.2    .045       0  931.57     .07       0
 1096.64     .08       0 1153.52     .06       0 1271.95      .1       0
#XS Ineff= 2 , 0
          484.13  723.84
Permanent Ineff=
       F       F
Bank Sta=849.2,931.57
XS Rating Curve= 0 ,0
Exp/Cntr(USF)=0,0
Exp/Cntr=0.3,0.1

Type RM Length L Ch R = 1 ,120903  ,415.7,426.3,436.9
XS GIS Cut Line= 6
1634165.12504333388346.0656248261634063.89394657388517.193891489
1633700.33791516389131.7769799161633652.60605524389212.466122993
1633603.28331925389295.8452213341633451.93421249389551.697071829
#Sta/Elev= 30
       0  727.69    81.9  717.81   206.9  709.97   363.4  708.06   439.7  704.98
   472.7  707.84   495.5  703.55   514.1  710.38   681.4  708.78   727.9  704.83
   792.9  703.31   820.8  697.11   852.3  696.78  860.17  690.56   871.9  688.09
     951  688.06   960.2   690.5   969.5  698.42  1007.6  699.06    1039  705.64
  1094.7  707.57    1149   706.2  1164.7  711.81  1211.9  715.73  1266.9  728.39
  1304.9  746.31  1342.9  759.79  1355.3  768.85  1384.7  800.04  1400.8  813.67
#Mann= 13 ,-1,0
       0     .06       0      70      .1       0  159.61     .05       0
  297.27     .07       0  357.27     .08       0  635.39     .07       0
  740.39     .06       0  860.17    .045       0   960.2     .07       0
  982.89     .08       0 1096.64     .07       0 1123.52     .06       0
 1211.95      .1       0
#XS Ineff= 2 , 0
          513.65  729.63 1094.22          719.31
Permanent Ineff=
       F       F
Bank Sta=860.17,960.2
XS Rating Curve= 0 ,0
Exp/Cntr(USF)=0,0
Exp/Cntr=0.3,0.1

Type RM Length L Ch R = 1 ,120477  ,151.8,192.7,216.7
XS GIS Cut Line= 3
1633833.99655255 388081.028740821633551.66509336388670.981694955
1633007.57948433389267.189557355
#Sta/Elev= 30
       0  760.61    79.3  744.66   119.2  731.49   141.4  716.74   150.2   715.2
   163.5  715.59   172.4  720.08     199  713.12   438.9  711.46     505  708.37
   522.7  702.12   558.2  706.76   588.9  699.45   620.3  711.86     778     709
   816.2  705.04   889.8  703.73     904  698.46   912.7 690.149   926.3  688.06
 1016.94  690.08  1033.1   697.4  1068.2  699.48  1145.9  742.95  1187.1   742.2
  1235.6  730.22  1274.9     730  1295.1  735.18  1403.4  746.56  1461.2  760.78
#Mann= 11 ,-1,0
       0      .1       0     140     .05       0     330     .07       0
     570     .08       0  824.03     .07       0   912.7    .045       0
 1016.94     .06       0 1184.03     .07       0 1224.03     .06       0
 1324.03     .07       0 1354.03     .05       0
#XS Ineff= 2 , 0
          639.61  720.48
Permanent Ineff=
       F       F
Bank Sta=912.7,1016.94
XS Rating Curve= 0 ,0
Exp/Cntr(USF)=0,0
Exp/Cntr=0.3,0.1

Type RM Length L Ch R = 1 ,120284  ,90.7,88.9,89.9
XS GIS Cut Line= 6
1633567.42028201388100.9544552361633456.13251755388739.150283688
1633402.13753688388737.6700153731633217.73322644 388756.51826073
1633037.23754373388805.0386055431632942.54922719389280.253831245
#Sta/Elev= 30
       0  755.08    52.4  743.04   125.4  718.12   145.7  713.72   355.2  711.16
   379.4  709.68   401.6  701.05     434  706.82   466.5  699.36     490  708.89
   503.8  710.01   585.6  711.29   641.1  707.96   744.1   707.6   776.3  705.86
   816.5  698.78   826.9 691.356   840.6  688.06   913.7  688.13   922.1691.2173
     931  696.63   942.7  708.32     951  710.98  1155.2  715.73    1200  714.57
    1249   719.5  1281.6  726.45  1391.7  731.21    1510  752.71  1558.7  766.48
#Mann= 9 ,-1,0
       0      .1       0     210     .07       0     510     .08       0
  711.84     .07       0  811.84     .08       0   826.9    .045       0
   922.1     .08       0 1254.11     .07       0 1364.11     .06       0
#XS Ineff= 2 , 0
          562.85  721.68
Permanent Ineff=
       F       F
Bank Sta=826.9,922.1
XS Rating Curve= 0 ,0
Exp/Cntr(USF)=0,0
Exp/Cntr=0.3,0.1

Type RM Length L Ch R = 1 ,120195  ,333.2,274.2,194.5
XS GIS Cut Line= 6
1633530.17189108388075.4055967991633425.39740388388654.981929963
1633373.57351563388653.5016616471633189.16920519388672.349907004
1633008.67352248388720.8702518181632876.91080762389248.513649686
#Sta/Elev= 30
       0  758.23    66.2  745.88   175.9  713.51   281.6  713.66   356.1  711.13
   379.2  708.91   395.4  702.39   440.2   706.9   470.9   699.3   480.1  698.65
   484.9  700.23     493  706.34   501.9  708.85   674.4  711.06   694.6  708.03
   734.8  698.76   758.9  697.18   772.6  691.16     783  688.07   856.6  688.06
   869.7  691.15   922.5  708.12     964  712.33  1037.5  713.42  1111.7  711.57
  1297.2  716.18  1367.3  725.03  1383.8  732.28  1449.8  735.43  1556.9  753.63
#Mann= 10 ,-1,0
       0      .1       0     230     .06       0     330     .07       0
     530     .08       0   772.6    .045       0   869.7     .08       0
 1193.08     .07       0 1393.08     .06       0 1443.08     .07       0
 1493.08     .05       0
#XS Ineff= 2 , 0
          631.73     723
Permanent Ineff=
       F       F
Bank Sta=772.6,869.7
XS Rating Curve= 0 ,0
Exp/Cntr(USF)=0,0
Exp/Cntr=0.3,0.1

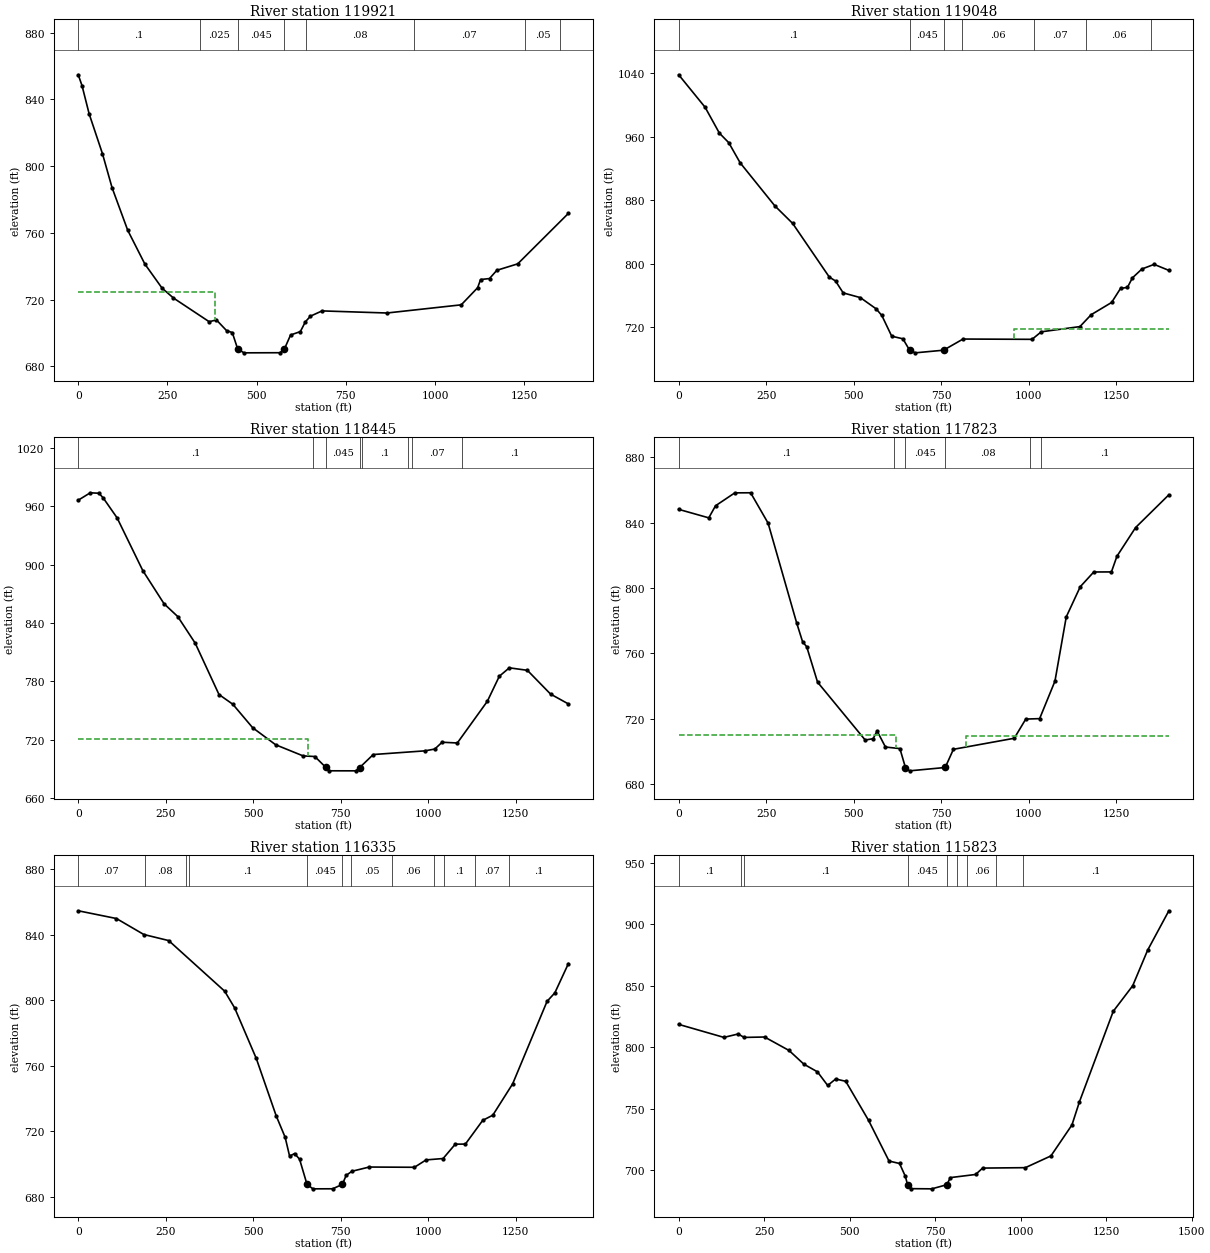
Type RM Length L Ch R = 1 ,119921  ,914.6,873.4,806.9
XS GIS Cut Line= 4
1633038.28320731387965.932225001 1633054.2334243388334.997186237
1632993.09776226388701.2479873941632816.39994689389308.830575046
#Sta/Elev= 30
       0  854.75    10.6  848.24    30.6   831.3    67.8   807.5    94.7  787.13
   138.7  761.51   186.8  741.25   234.8  726.86   266.9   720.9   366.9  706.72
   387.2  707.79   415.6  701.39   431.7  700.21   446.6  690.47   464.2  688.06
   565.6  688.13   577.8  690.41     595  698.76   622.4   700.8   636.4  706.65
   650.8  710.06   683.2   713.2     865  711.94  1073.2  716.84  1119.1  727.08
  1127.4     732  1152.4  732.59  1172.9  737.54  1231.5  741.41  1373.5  771.67
#Mann= 8 ,-1,0
       0      .1       0     340    .025       0   446.6    .045       0
   577.8     .07       0  639.41     .08       0  940.73     .07       0
 1250.73     .05       0 1350.73      .1       0
#XS Ineff= 2 , 0
          383.18  724.66
Permanent Ineff=
       F       F
Bank Sta=446.6,577.8
XS Rating Curve= 0 ,0
Exp/Cntr(USF)=0,0
Exp/Cntr=0.3,0.1

Type RM Length L Ch R = 1 ,119048  ,604.7,603.2,602
XS GIS Cut Line= 6
 1631824.7399495388299.565915452 1632266.6209555388776.796588288
1632334.56209259388850.1724257931632574.47827942389109.281159537
1632641.35741075389181.511001961 1632776.4430986389327.403098615
#Sta/Elev= 30
       0 1038.09    75.6  997.14   116.3  964.64   143.1  952.62   175.7  927.27
   274.8  873.08   325.8  850.95   430.5  783.41   448.3   778.5   470.1  763.52
   519.2  757.57   564.3  743.44   580.5  735.12   608.8  709.01   640.8  705.73
   659.8  691.46   676.1  688.06  756.89  691.39   812.6  705.43  1009.8  705.06
  1036.2  714.53  1146.6  721.09  1178.8  736.07  1237.2  751.47  1262.7  769.13
  1282.5  770.46  1296.6   782.4  1323.8  793.59  1358.7  799.42  1400.8  791.86
#Mann= 7 ,-1,0
       0      .1       0   659.8    .045       0  756.89      .1       0
  810.39     .06       0 1016.64     .07       0 1163.52     .06       0
 1351.17      .1       0
#XS Ineff= 2 , 0
                          957.22          717.75
Permanent Ineff=
       F       F
Bank Sta=659.8,756.89
XS Rating Curve= 0 ,0
Exp/Cntr(USF)=0,0
Exp/Cntr=0.3,0.1

Type RM Length L Ch R = 1 ,118445  ,620.7,621.7,624
XS GIS Cut Line= 6
1631354.56512519388709.2610061611631424.22115386388780.465260073
 1631931.7565561389299.2778707441631992.94475394389361.825973987
1632264.46783295389639.3821773971632334.12418968389710.586431324
#Sta/Elev= 30
       0  966.08    34.5  973.68    59.4  973.19    71.7  968.21   110.9     948
   184.4  893.81   245.2   859.7   284.4  846.52   334.4  819.12   402.2  766.46
   441.8  756.44   498.4  732.37   564.2  714.84   642.5  703.42   676.1  702.77
   707.7  691.55   717.2   688.1   793.6  688.06  804.45  691.49   843.1  704.81
   990.6  708.59  1018.9  710.44  1039.8  717.44  1083.3  716.67  1169.1  759.49
  1203.4  785.27    1232  793.87  1283.5  791.32  1349.8   766.9  1400.8  756.78
#Mann= 8 ,-1,0
       0      .1       0  670.39    .025       0   707.7    .045       0
  804.45    .025       0  810.39      .1       0  942.89     .08       0
  952.89     .07       0 1096.64      .1       0
#XS Ineff= 2 , 0
          655.33  720.45
Permanent Ineff=
       F       F
Bank Sta=707.7,804.45
XS Rating Curve= 0 ,0
Exp/Cntr(USF)=0,0
Exp/Cntr=0.3,0.1

Type RM Length L Ch R = 1 ,117823  ,1500.3,1487.5,1474.4
XS GIS Cut Line= 6
1630938.57657351389129.2997954191631005.21161084389203.339017421
1631071.58549385389277.0875575841631137.43706818389350.255390257
1631202.24304092389422.2621360121631875.65114293390170.490954503
#Sta/Elev= 30
       0  848.17      86  842.97   105.3  850.36   160.4  858.27   205.6  858.32
   255.5  839.74   337.1  778.68   354.1  767.11   365.9  764.03   396.9  742.36
     533  706.93   555.7  707.73     567  712.46   590.9  702.64   632.2  701.68
  648.08690.0209     660  688.06   761.7  690.11   785.1  701.24     959  708.01
   991.9  719.75  1031.5  720.03  1075.3  742.98  1107.6  782.33  1147.6  800.79
  1186.2  809.82  1236.7  809.86  1252.4  819.44  1305.8  837.04  1400.8  857.08
#Mann= 6 ,-1,0
       0      .1       0  615.39    .025       0  648.08    .045       0
   761.7     .08       0 1002.89     .07       0 1036.64      .1       0
#XS Ineff= 2 , 0
          622.37  709.78  821.64          709.66
Permanent Ineff=
       F       F
Bank Sta=648.08,761.7
XS Rating Curve= 0 ,0
Exp/Cntr(USF)=0,0
Exp/Cntr=0.3,0.1

Type RM Length L Ch R = 1 ,116335  ,508.8,512.5,515.7
XS GIS Cut Line= 6
1629696.33857243390195.0458472541629863.49637459390302.706721174
1630106.51557359390459.2277335851630390.25713208390641.976383837
 1630542.6367486390740.1189040861630873.99665017390953.537112417
#Sta/Elev= 30
       0  854.55   109.2  849.82   187.4  840.08   258.5  836.37   418.4  805.52
     447   795.3   508.8  764.47   565.9  729.36   591.3  716.39     604  704.89
   618.3  706.46   632.5  703.02  653.69  687.73   670.6  684.94   727.3  684.97
   754.9687.6733   765.7  693.18   782.3  695.66   831.5  698.24   960.8  698.09
   994.1  702.59  1042.7  703.43  1077.5  712.19  1106.4  712.24  1155.9  726.71
  1184.7  729.86  1241.5  749.01  1339.8  799.32    1362  804.48  1400.8  822.35
#Mann= 12 ,-1,0
       0     .07       0  189.61     .08       0  307.27     .07       0
  317.27      .1       0  653.69    .045       0   754.9      .1       0
  780.39     .05       0  895.39     .06       0 1016.64     .07       0
 1046.64      .1       0 1133.52     .07       0 1231.95      .1       0
Bank Sta=653.69,754.9
XS Rating Curve= 0 ,0
Exp/Cntr(USF)=0,0
Exp/Cntr=0.3,0.1

Type RM Length L Ch R = 1 ,115823  ,477.7,486.5,491
XS GIS Cut Line= 6
1629484.21071585390508.5552390071629512.40915026390637.680636927
1629592.07828225390696.8291406781629671.12536825390755.515375003
1630318.33765651391236.301486924 1630556.9969561 391413.48781234
#Sta/Elev= 30
       0  818.56   132.2  807.96     174  810.74   191.2  807.94   251.2  808.27
   322.7  797.32     366  786.18   405.8  779.92   435.7  768.83     459   774.1
   488.5  772.22   555.3  740.39   615.1  707.32   645.8  705.33   662.9  694.81
  669.22688.0539   680.1  684.84   740.1   684.7  784.07688.0449   794.4  693.84
   868.2  696.39   888.8  701.59  1013.7  701.93  1088.5  711.51  1149.9  736.67
  1171.8   755.5  1270.7  829.19  1327.6     850  1371.3  878.96  1433.3  911.01
#Mann= 9 ,-1,0
       0      .1       0  182.17     .06       0  192.17      .1       0
  669.22    .045       0  784.07    .025       0  812.97      .1       0
  842.97     .06       0  927.97     .07       0 1005.47      .1       0
Bank Sta=669.22,784.07
XS Rating Curve= 0 ,0
Exp/Cntr(USF)=0,0
Exp/Cntr=0.3,0.1

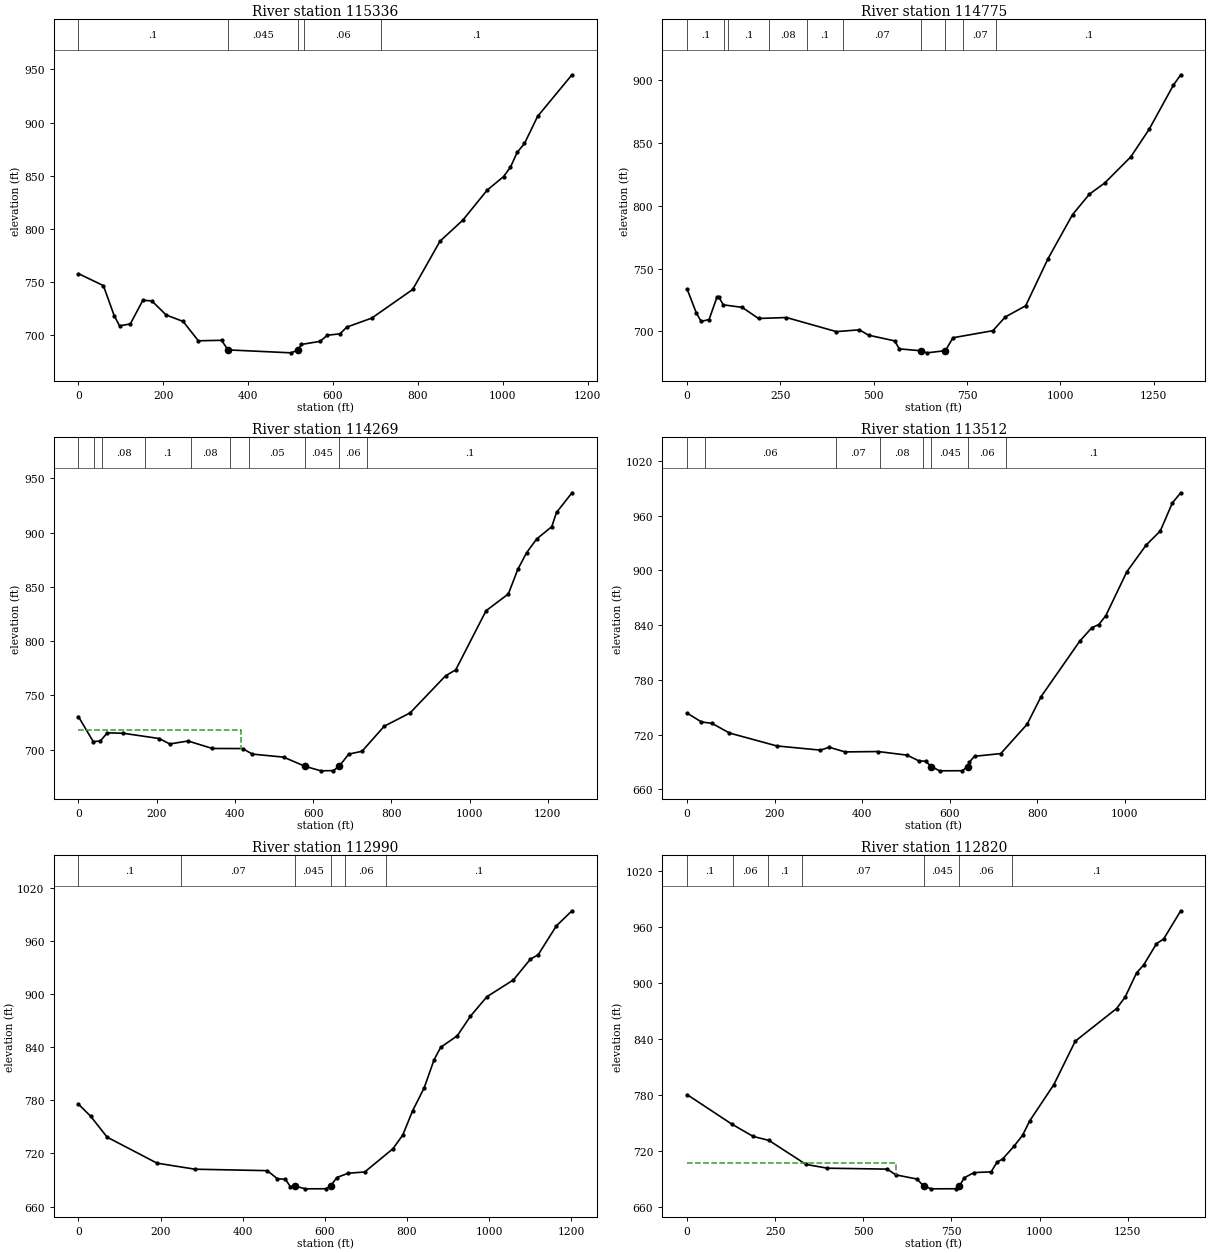
Type RM Length L Ch R = 1 ,115336  ,527.1,561.3,588.7
XS GIS Cut Line= 3
1629453.58653623391020.8242944921629522.35451514391221.750828208
1630232.35849775391854.449528843
#Sta/Elev= 30
       0  757.99    58.9  746.71    84.3  718.53    96.9  708.87   122.3  710.66
   151.9   732.9     173  732.34   206.9  719.07   246.8  713.03   282.7  694.81
   337.4  695.28   352.6686.2636   501.7  683.49  517.67  686.25   525.5  691.38
   569.7   694.3   586.7  700.07   616.6  701.34   632.6   707.7   691.6  716.19
   787.9  743.07   852.3   788.5   905.9   808.2   963.5  836.53  1002.3  849.29
  1018.4  858.16  1034.2     872  1051.4  880.39  1082.5  905.96  1163.4  944.99
#Mann= 5 ,-1,0
       0      .1       0   352.6    .045       0  517.67      .1       0
  532.37     .06       0  712.37      .1       0
Bank Sta=352.6,517.67
XS Rating Curve= 0 ,0
Exp/Cntr(USF)=0,0
Exp/Cntr=0.3,0.1

Type RM Length L Ch R = 1 ,114775  ,469.6,506.2,548.3
XS GIS Cut Line= 3
1629293.89689264391052.8823396231629178.07033577391392.279835245
1629399.59391237392330.813170781
#Sta/Elev= 30
       0  733.65      25  714.42    37.7  707.97    58.8  709.51    79.9  727.25
    84.2  727.69    96.8   721.2   147.6  719.13   191.3  710.32   266.1  711.09
     400  699.88   461.6  701.32   486.3  697.05   556.2  692.52   568.5  686.19
     626  684.69   642.5  683.03  692.14  684.74   712.3  695.01   819.4  700.63
   852.6  711.52   907.3  720.42   967.1  757.78  1032.9  792.83  1078.1  809.08
  1119.2  817.97  1189.1  838.73  1238.4  860.73    1303   895.6  1322.9  903.94
#Mann= 10 ,-1,0
       0      .1       0     100     .08       0     110      .1       0
     220     .08       0     320      .1       0  418.62     .07       0
     626    .045       0  692.14     .08       0  738.62     .07       0
  828.62      .1       0
Bank Sta=626,692.14
XS Rating Curve= 0 ,0
Exp/Cntr(USF)=0,0
Exp/Cntr=0.3,0.1

Type RM Length L Ch R = 1 ,114269  ,727.3,757,785.9
XS GIS Cut Line= 4
1629182.83618684391007.2260116681629050.53921926391250.781686822
1628620.22769622391626.1970035141628236.11068202391780.094874786
#Sta/Elev= 30
       0  730.54    37.9  707.53    56.1  708.06    73.8  715.59   114.6   715.2
   206.3  710.37   233.6  705.35   280.4  708.07   342.5  701.18   419.8  701.12
   444.6  696.01   524.6  693.21   579.7 684.709   620.3  680.59     652  680.81
  666.59   684.8   691.2  695.98   725.2  698.62   781.9  721.68   848.2  733.98
   938.8  768.14   964.7  773.59  1042.3  828.06  1099.3  843.52  1123.4  866.09
  1145.7  881.37  1171.5  894.08  1210.3  905.49  1222.4  918.55    1262  936.69
#Mann= 10 ,-1,0
       0     .08       0      40     .07       0      60     .08       0
     170      .1       0  287.17     .08       0  387.17     .07       0
  437.17     .05       0   579.7    .045       0  666.59     .06       0
  737.17      .1       0
#XS Ineff= 2 , 0
          414.57  718.17
Permanent Ineff=
       F       F
Bank Sta=579.7,666.59
XS Rating Curve= 0 ,0
Exp/Cntr(USF)=0,0
Exp/Cntr=0.3,0.1

Type RM Length L Ch R = 1 ,113512  ,515.8,521.8,527.1
XS GIS Cut Line= 2
1629204.79544625390742.4945040191628076.97653645390778.353380036
#Sta/Elev= 30
       0  743.51    32.7  733.83    56.7  732.34    96.7   721.7   204.8  707.55
   304.8  702.92   324.8  706.13   360.9  700.98   436.9  701.38   502.9  697.43
   528.9  691.34     545  690.67   558.5684.9456     577  680.22     629  680.37
  641.16  684.97     645  689.73     657  696.19     717  699.15   777.1  731.28
   809.1  761.64   897.1  822.19   925.1  837.22   941.2  840.69   957.2  850.53
  1005.2   898.6  1049.2  927.83  1081.6  943.27  1109.2  974.09  1128.4  985.23
#Mann= 8 ,-1,0
       0     .05       0      40     .06       0     340     .07       0
     440     .08       0     540     .07       0   558.5    .045       0
  641.16     .06       0     730      .1       0
Bank Sta=558.5,641.16
XS Rating Curve= 0 ,0
Exp/Cntr(USF)=0,0
Exp/Cntr=0.3,0.1

Type RM Length L Ch R = 1 ,112990  ,167.6,170.2,171.2
XS GIS Cut Line= 2
1629213.65403188390301.2454055861628018.16954621390176.715799005
#Sta/Elev= 30
       0   775.6    29.7     762    69.9  738.35   191.4  708.97   283.8  702.15
     460  700.49   484.1  691.52   504.3  690.58   516.3  682.43   528.4  683.03
   552.5  679.97   602.5  680.07  613.97   683.1   629.4  692.77   657.1  697.59
   697.3  699.03   765.7  725.12   789.8  740.61   813.9  768.13   842.1  794.06
   866.2  825.74   882.3   839.8   922.5  852.67   954.7  874.88   994.9  896.91
  1059.2  915.78  1100.8  939.28  1119.6   944.2  1163.8  976.74    1202  993.88
#Mann= 6 ,-1,0
       0      .1       0     250     .07       0   528.4    .045       0
  613.97     .08       0     650     .06       0     750      .1       0
Bank Sta=528.4,613.97
XS Rating Curve= 0 ,0
Exp/Cntr(USF)=0,0
Exp/Cntr=0.3,0.1

Type RM Length L Ch R = 1 ,112820  ,99.2,98.5,97.3
XS GIS Cut Line= 6
1629385.61937758390181.2796468441629091.58486067390137.571729004
 1628816.4823925390096.6784380821628569.19942251 390059.91998142
1628482.65038301390047.0548496691628000.06243743389975.318772674
#Sta/Elev= 30
       0  780.75   126.9  749.13   187.5  735.96     232  731.74   337.2     706
   397.8  701.95   567.7  700.96   591.9  694.85   652.6  690.29  671.27682.6968
     693  679.84   761.8  679.94  772.81682.6645     786  691.61   814.4  697.28
   862.9  698.01   879.1  708.31   895.2  711.79   927.6  725.47   951.9  737.17
   972.1  752.59  1040.6   791.4  1101.5  838.03  1218.8  872.98    1243  885.18
  1275.4  911.13  1295.6  919.61    1332  942.43  1352.2  947.41  1400.8  977.65
#Mann= 7 ,-1,0
       0      .1       0  129.61     .06       0  228.83      .1       0
  327.27     .07       0  671.27    .045       0  772.81     .06       0
  922.89      .1       0
#XS Ineff= 2 , 0
          591.57  707.34
Permanent Ineff=
       F       F
Bank Sta=671.27,772.81
XS Rating Curve= 0 ,0
Exp/Cntr(USF)=0,0
Exp/Cntr=0.3,0.1