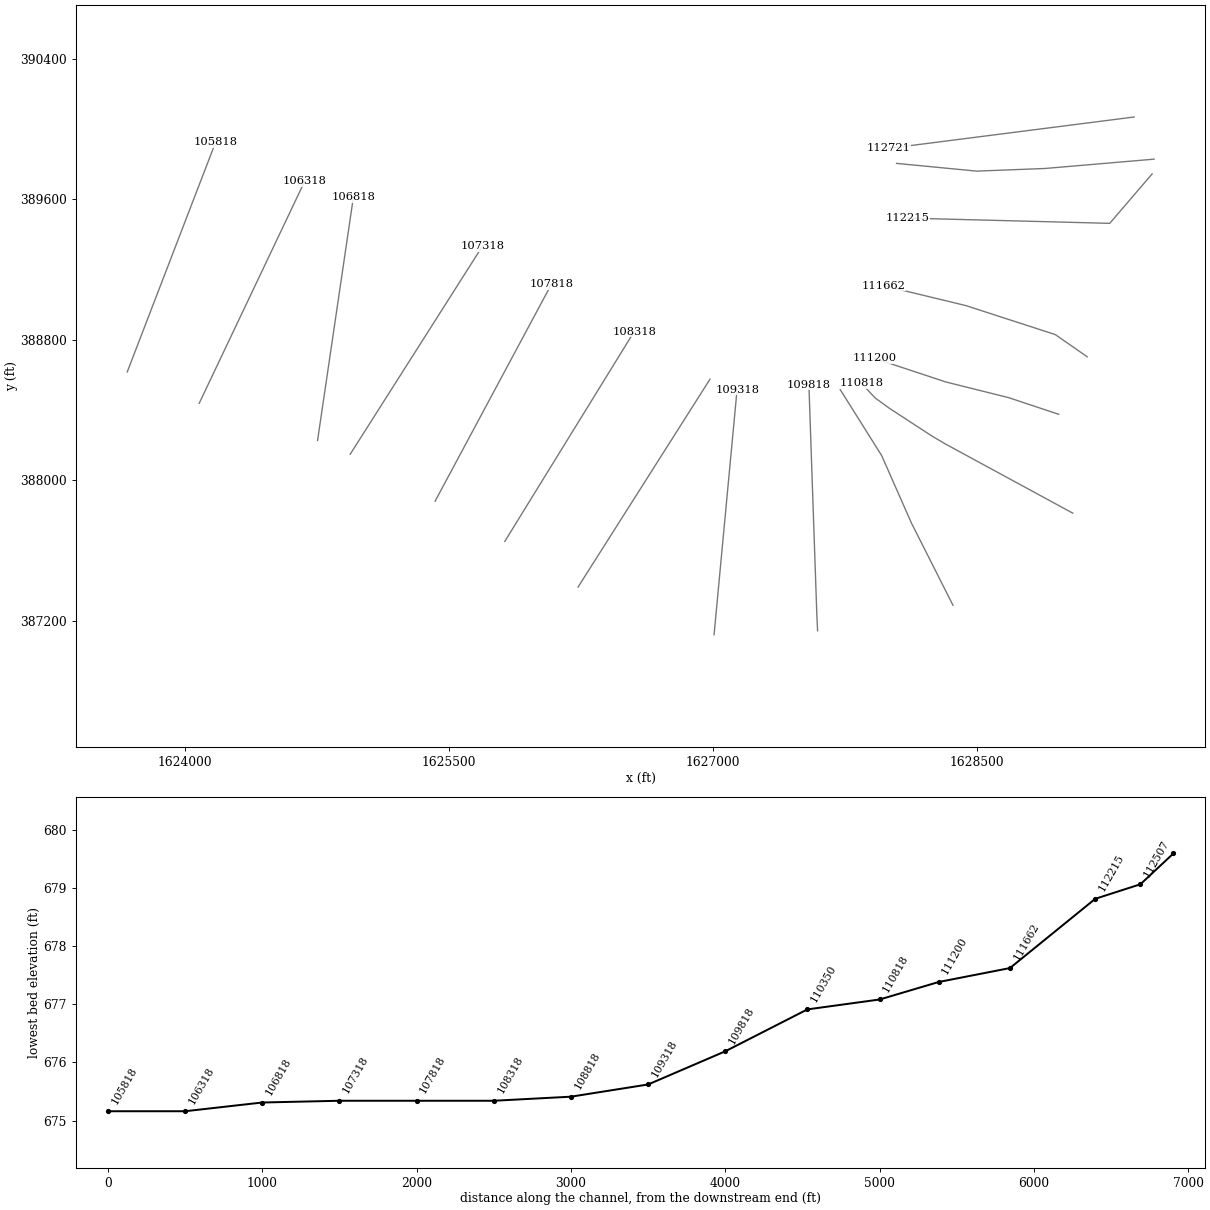
HEC-RAS study FISHINGCK.prj: FISHINGCK

--- FISHINGCK.g01 (geometry) --- (continued)

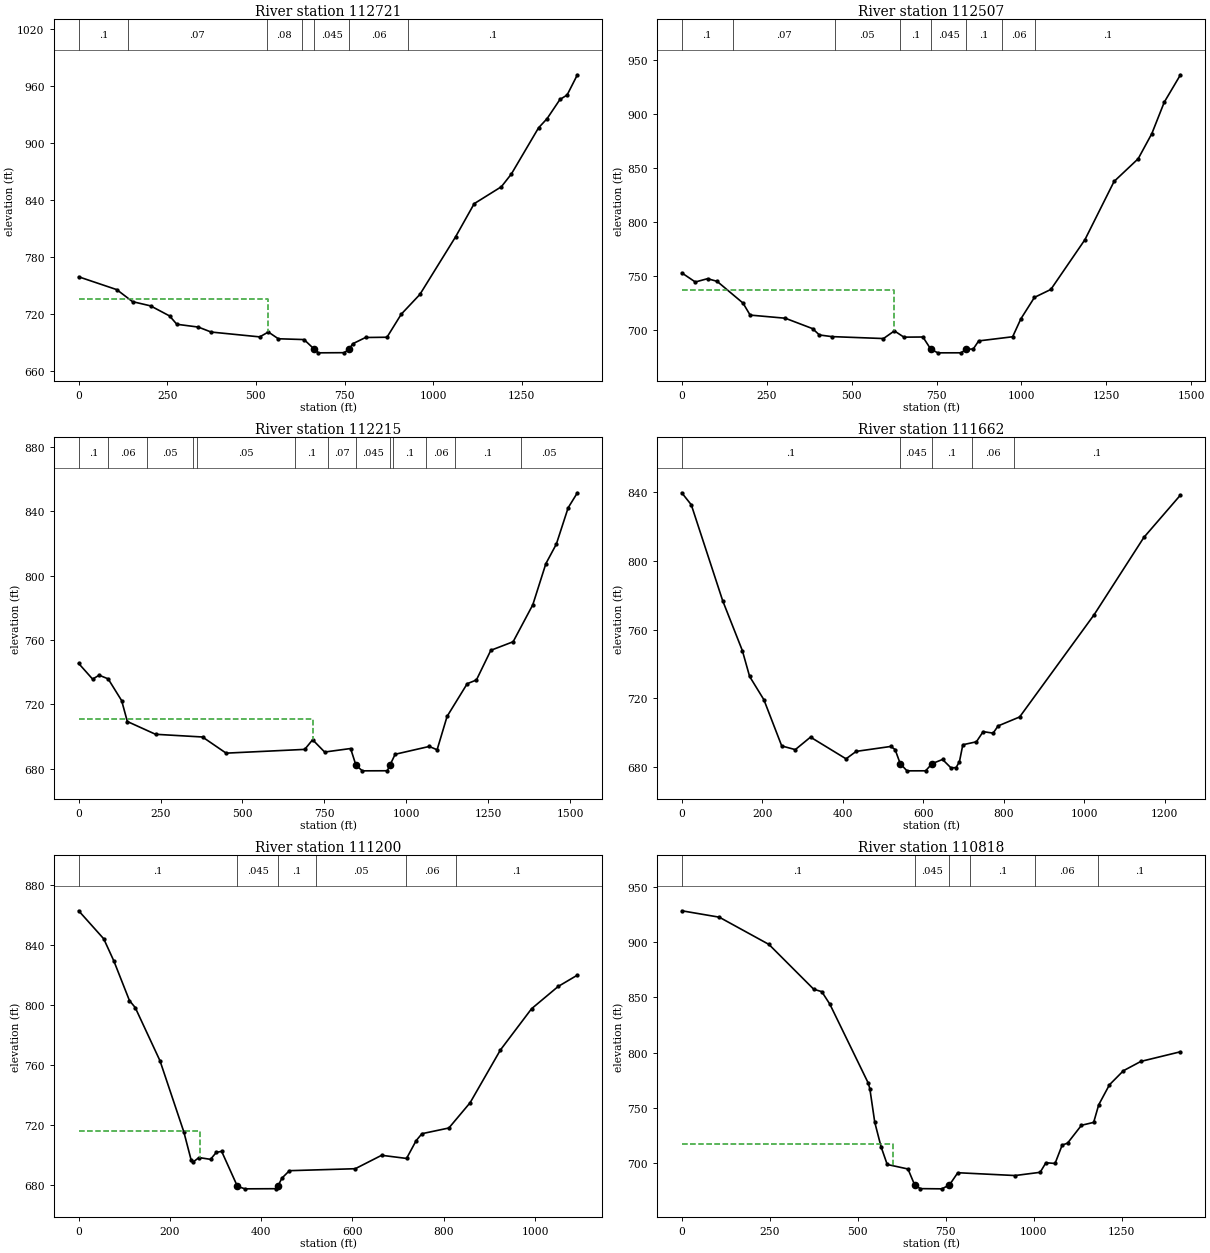
Type RM Length L Ch R = 1 ,112721  ,217.6,214,208
XS GIS Cut Line= 2
1629394.78597056390068.7529551821627999.34085372389890.198086267
#Sta/Elev= 30
       0  759.49   107.5     746   151.9  733.39   202.8  728.94   256.4  718.37
   276.9   709.6   337.4  706.67   373.7  701.44   510.8  696.35     535  701.47
   563.2  694.38   635.8  693.53   665.1683.2456   676.1  679.59   748.7  679.76
  762.83  683.27   772.9  689.09   809.2  695.71   869.7  695.98     910  720.21
   962.5  740.95  1063.3  801.55  1115.7  836.32  1192.3   854.1  1220.5  867.46
  1297.2  915.98  1321.4  925.72  1357.6   945.8  1377.8  950.49  1406.8  971.75
#Mann= 7 ,-1,0
       0      .1       0     140     .07       0     530     .08       0
     630     .07       0   665.1    .045       0  762.83     .06       0
     930      .1       0
#XS Ineff= 2 , 0
          533.33  735.83
Permanent Ineff=
       F       F
Bank Sta=665.1,762.83
XS Rating Curve= 0 ,0
Exp/Cntr(USF)=0,0
Exp/Cntr=0.3,0.1

Type RM Length L Ch R = 1 ,112507  ,295.9,292.6,289.1
XS GIS Cut Line= 4
1629507.82307901389828.816248357 1628887.5755144389775.701752939
1628499.63624872389760.7040697391628044.16277032389804.668691206
#Sta/Elev= 30
       0  753.11    39.9  744.66      76  747.73   104.1  745.25   180.4  725.12
   201.3  714.02   304.8  711.11   385.1  701.48   405.2  695.62   441.3   694.1
   593.9  692.29     626  699.38     654  693.59     710  693.72   733.4  682.33
   754.1  679.06   822.1  679.09   838.1  682.38   858.2  682.62   874.2   690.1
   974.2  693.95   998.3   710.5  1038.4  730.42  1086.6  737.75  1187.1   783.9
  1272.8  837.75  1343.7  858.75    1384  882.08  1420.6   911.2  1468.3  936.53
#Mann= 8 ,-1,0
       0      .1       0     150     .07       0     450     .05       0
  642.52      .1       0   733.4    .045       0   838.1      .1       0
  942.52     .06       0 1040.75      .1       0
#XS Ineff= 2 , 0
          623.86  736.91
Permanent Ineff=
       F       F
Bank Sta=733.4,838.1
XS Rating Curve= 0 ,0
Exp/Cntr(USF)=0,0
Exp/Cntr=0.3,0.1

Type RM Length L Ch R = 1 ,112215  ,566.3,552.6,538
XS GIS Cut Line= 3
1629496.75386359389744.8768060111629255.82773795389463.503228623
1628103.95465552 389493.39917122
#Sta/Elev= 30
       0  745.44    42.6  735.72    62.5  738.15      90  735.88   131.2  722.39
   148.6  709.42   234.7  701.49   378.1  699.81   450.2  689.79   690.2  692.12
   714.3  698.09   751.1  690.47   830.3  692.66  846.55  682.31   866.1  678.81
   942.3  678.86   950.3  682.28   966.3  689.09  1070.4  693.94  1094.4  691.88
  1124.9   712.6  1186.3  732.87  1214.4  735.18  1258.4  753.59  1326.5   758.9
  1386.5  781.81  1426.5  807.38  1458.5  819.51  1494.5  842.03  1522.7  851.33
#Mann= 13 ,-1,0
       0      .1       0      90     .06       0     210     .05       0
     350      .1       0     360     .05       0  660.43      .1       0
  760.43     .07       0  846.55    .045       0   950.3     .07       0
  960.43      .1       0 1060.43     .06       0 1150.43      .1       0
 1350.43     .05       0
#XS Ineff= 2 , 0
          714.85  711.15
Permanent Ineff=
       F       F
Bank Sta=846.55,950.3
XS Rating Curve= 0 ,0
Exp/Cntr(USF)=0,0
Exp/Cntr=0.3,0.1

Type RM Length L Ch R = 1 ,111662  ,458.7,462.6,462
XS GIS Cut Line= 4
1629127.59543183388704.2173664441628946.31680283388830.412679499
1628438.47766839388995.282042944 1627967.7298781 389109.23319439
#Sta/Elev= 30
       0  839.78    23.7  832.76   101.7  776.83   150.5  747.79   168.6  732.67
   204.1  719.08   248.4  692.14   282.1  689.99   319.9  697.28   408.2  684.63
   433.5  688.97   519.6  691.85   530.2     690   542.8  681.83   559.6  677.62
   605.9  677.64  622.09  681.83     648  684.25     669  679.34   681.6   679.5
     690     683   698.4  692.83   732.1  694.56   748.9  700.48   773.7   699.6
     786  703.81   839.6  709.05  1024.8  768.73  1148.2  813.74  1239.2  838.47
#Mann= 5 ,-1,0
       0      .1       0   542.8    .045       0  622.09      .1       0
  720.88     .06       0  824.81      .1       0
Bank Sta=542.8,622.09
XS Rating Curve= 0 ,0
Exp/Cntr(USF)=0,0
Exp/Cntr=0.3,0.1

Type RM Length L Ch R = 1 ,111200  ,392.9,381.5,370.3
XS GIS Cut Line= 4
1628965.66123627 388376.697785961628680.77048917388471.661368329
1628324.15363366388560.7136201211627920.75057714388694.355295799
#Sta/Elev= 30
       0  862.83    54.9  844.14      77  829.43   111.3  802.93   123.9   798.3
   178.2  762.78   230.4   715.4   246.2  696.89   250.9  695.29   263.6  698.24
   288.9  697.05   301.6  701.71   313.3  702.37   347.8   679.1   364.2  677.38
   432.9  677.47  436.45  679.11   445.3   684.5   461.8  689.49   606.1   690.8
   663.8  699.75   718.5  697.66   739.5  709.53   752.2  714.16   811.2  717.96
   857.7   734.8   924.1  769.98   992.4  797.51  1050.7  812.35  1092.8  819.91
#Mann= 6 ,-1,0
       0      .1       0   347.8    .045       0  436.45      .1       0
   520.3     .05       0  717.87     .06       0  827.87      .1       0
#XS Ineff= 2 , 0
          264.79  715.72
Permanent Ineff=
       F       F
Bank Sta=347.8,436.45
XS Rating Curve= 0 ,0
Exp/Cntr(USF)=0,0
Exp/Cntr=0.3,0.1

Type RM Length L Ch R = 1 ,110818  ,488.8,468.1,430
XS GIS Cut Line= 6
1629045.74144842387814.0852342551628320.64841042388208.432542667
1628245.24206518388252.9242515861628002.45285259388411.527608916
1627921.54750259388470.4352995011627843.42758009388554.252717167
#Sta/Elev= 30
       0  928.31   106.6  922.53   247.8  897.91   375.2   857.4     398  855.23
   420.8  844.01     530  772.68   534.6  767.57   548.6  737.23   566.3  715.32
     584  699.09     643  695.01   662.1  680.56   678.4  677.26   739.5  677.08
     761  680.64   784.6  691.64   947.5   689.1  1018.7  692.01  1035.1  700.66
  1061.1  700.01  1081.3  716.61  1096.6  718.36  1136.1  734.49  1170.8  737.13
  1185.2  753.05  1215.7  771.09  1255.3  783.77  1305.1  792.22  1417.6  800.93
#Mann= 6 ,-1,0
       0      .1       0   662.1    .045       0     761    .025       0
  820.39      .1       0 1002.94     .06       0 1184.12      .1       0
#XS Ineff= 2 , 0
          599.35  717.33
Permanent Ineff=
       F       F
Bank Sta=662.1,761
XS Rating Curve= 0 ,0
Exp/Cntr(USF)=0,0
Exp/Cntr=0.3,0.1

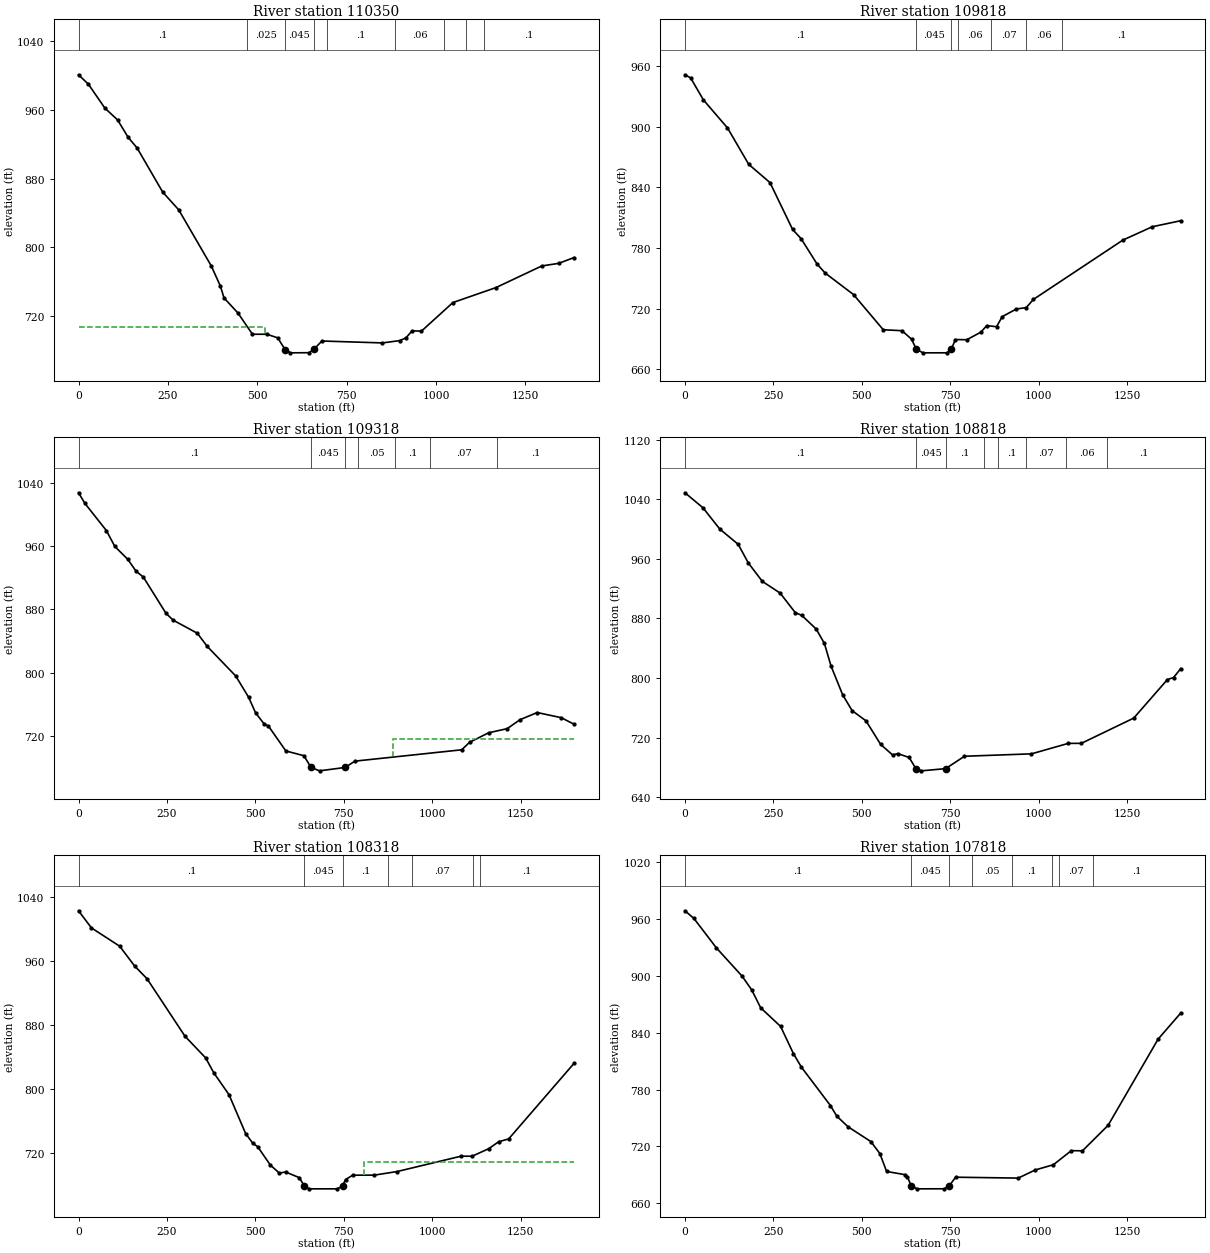
Type RM Length L Ch R = 1 ,110350  ,540.1,531.9,511.2
XS GIS Cut Line= 4
 1628364.5735766387290.230044947 1628128.3502151387758.289498272
1627959.52606867388141.5083304921627723.81268392388517.161118464
#Sta/Elev= 30
       0 1001.02    27.7  990.03    73.5  962.28   109.3   948.4     139  928.02
   163.9  915.71   235.6  864.22   280.4  843.56   371.3  778.26   396.9  754.72
     407  740.94   446.2  723.25   486.5   698.6   526.7  698.58   557.3  694.38
  577.74  680.77   592.9  676.91   644.8  677.08   657.8680.8346   680.9  690.71
   850.2  688.47   898.3  691.14   915.8  694.33   933.2  702.55   959.3  702.21
  1047.3  735.52  1167.7  752.97  1295.9  778.19  1343.3  781.21  1386.5  788.03
#Mann= 9 ,-1,0
       0      .1       0     470    .025       0  577.74    .045       0
   657.8    .025       0  694.29      .1       0  884.29     .06       0
 1023.05      .1       0 1083.05     .06       0 1133.05      .1       0
#XS Ineff= 2 , 0
          522.67   706.8
Permanent Ineff=
       F       F
Bank Sta=577.74,657.8
XS Rating Curve= 0 ,0
Exp/Cntr(USF)=0,0
Exp/Cntr=0.3,0.1

Type RM Length L Ch R = 1 ,109818  ,505.2,500,492.8
XS GIS Cut Line= 6
1627595.09802426387144.5334237521627590.56686534387244.046020001
1627583.75585534387441.5846669231627580.41793551387538.402058586
1627571.58626026387794.4999715831627545.72574767388544.444665924
#Sta/Elev= 30
       0  951.47      16  948.37    52.1  926.58   120.1   898.9   180.2  862.78
   240.2  844.75   304.2  798.33   328.2   789.2   373.3  764.11     396  755.24
   476.3  733.87   560.4  699.05   613.2  698.12   640.4  689.69  653.53679.9778
   672.4  676.19   740.5  676.22  752.64679.9347   764.5  689.34   796.5  689.17
   836.5  696.69   852.6  703.11   880.6  702.07   896.6  712.05   936.6  719.58
   964.6  721.01   984.6  729.06  1237.5   787.8  1320.5     801  1400.8  806.97
#Mann= 7 ,-1,0
       0      .1       0  653.53    .045       0  752.64      .1       0
   770.4     .06       0   865.4     .07       0   962.9     .06       0
 1066.65      .1       0
Bank Sta=653.53,752.64
XS Rating Curve= 0 ,0
Exp/Cntr(USF)=0,0
Exp/Cntr=0.3,0.1

Type RM Length L Ch R = 1 ,109318  ,520.9,500,478.3
XS GIS Cut Line= 6
1627006.66219325387122.3129957621627015.95941876387221.487338096
1627091.87035617388031.2183301751627100.62066676388124.559022754
1627128.11240968388417.8044992541627137.40963517388516.978841588
#Sta/Elev= 30
       0 1027.38    18.3 1013.82    78.6  979.66   102.7  959.43   138.8  943.41
   162.9  928.04     183   920.9   247.3  874.87   267.4  866.24   335.7  849.72
   363.8  833.02   444.2  795.68   480.9  768.58   500.4     749   524.5  734.98
   536.6  732.39     586  700.78     637  694.75  657.07 679.924   681.2  675.62
  753.65679.9179   781.1  687.89    1083  702.25  1105.3  711.74  1159.3  723.79
  1211.5  728.99  1247.7  740.31  1296.3  749.38  1364.2  742.87  1400.8   734.5
#Mann= 7 ,-1,0
       0      .1       0  657.07    .045       0  753.65      .1       0
  790.39     .05       0  895.39      .1       0  992.89     .07       0
 1183.52      .1       0
#XS Ineff= 2 , 0
                          888.88          715.85
Permanent Ineff=
       F       F
Bank Sta=657.07,753.65
XS Rating Curve= 0 ,0
Exp/Cntr(USF)=0,0
Exp/Cntr=0.3,0.1

Type RM Length L Ch R = 1 ,108818  ,499.5,500,500.6
XS GIS Cut Line= 6
1626233.51183668387393.465012506 1626392.6706391387644.533079922
 1626444.5386456387726.3527981791626824.34562875388325.485130087
1626877.04991968388408.6247275921626983.50475925388576.553525582
#Sta/Elev= 30
       0 1048.68      51 1028.46    98.4  999.98   150.5  979.44   178.9  954.56
   218.6  929.74   268.9  914.04   311.5  887.91   330.4  883.98   370.9  865.73
   394.1  846.36   412.8  816.08   445.6  777.52   472.5  756.15   511.4  742.62
     553  710.89   586.7  696.76   601.2  698.55   633.5  693.39   652.5  678.43
   667.9  675.41  736.78678.3785   789.8  694.99   979.3  698.23  1083.4  712.29
  1120.1  712.29  1268.2   746.2  1363.5  797.97  1380.9   800.7  1400.8  812.51
#Mann= 8 ,-1,0
       0      .1       0   652.5    .045       0  736.78      .1       0
  845.39     .05       0  885.39      .1       0  962.89     .07       0
 1076.64     .06       0 1193.52      .1       0
Bank Sta=652.5,736.78
XS Rating Curve= 0 ,0
Exp/Cntr(USF)=0,0
Exp/Cntr=0.3,0.1

Type RM Length L Ch R = 1 ,108318  ,496.2,500,502.7
XS GIS Cut Line= 6
1625817.08845693387653.3883771751626072.93177725388068.817336336
1626249.91272251388356.191761583  1626295.796489388430.696533844
1626395.75790326388593.0095294271626551.64013742388846.125493005
#Sta/Elev= 30
       0 1023.11    36.6 1001.68   116.4  978.79   158.7  953.95   193.5  938.22
     301  866.15   359.2  839.17   382.4  820.42   425.3  793.12   472.6  744.21
   492.9  732.23   506.4  728.01   542.3  705.01   567.4  695.13   585.5  696.36
   623.8  689.36   638.3  678.87     652  675.34   731.8  675.34  746.08678.8563
   754.6  686.93   774.9  692.39     836   692.5   899.9  696.93  1081.3   716.2
  1112.4  716.14  1159.3  725.53  1187.7  734.32  1215.7  737.76  1400.8  832.47
#Mann= 7 ,-1,0
       0      .1       0   638.3    .045       0  746.08      .1       0
  875.39     .05       0  942.89     .07       0 1113.52     .08       0
 1133.52      .1       0
#XS Ineff= 2 , 0
                          805.94          709.39
Permanent Ineff=
       F       F
Bank Sta=638.3,746.08
XS Rating Curve= 0 ,0
Exp/Cntr(USF)=0,0
Exp/Cntr=0.3,0.1

Type RM Length L Ch R = 1 ,107818  ,504.4,500,496.3
XS GIS Cut Line= 6
1625420.96096835387882.2215809231625514.81379901388057.505023003
1625561.27892917388144.2860174181625810.56944109  388609.8720285
   1625851.87218 388687.010325671626082.17060393389117.126263335
#Sta/Elev= 30
       0  968.63    25.3  960.53    88.8  929.49   161.4   899.7   188.7   885.1
   213.8  866.36   270.3  846.62   306.6  817.88   329.3  803.56     411  763.24
   429.1  751.98   460.9   740.8   525.4  725.18   550.7  712.61   569.8  693.66
   621.6   690.3   628.8  687.81   639.4  678.45     656  675.34   733.1  675.39
  746.55678.4057   764.9  687.61   941.8  686.68   989.7  695.22  1041.3  700.78
  1091.8  715.61  1123.3  715.44  1195.9  742.37  1337.1  833.23  1400.8  860.66
#Mann= 8 ,-1,0
       0      .1       0   639.4    .045       0  746.55      .1       0
  810.39     .05       0  922.89      .1       0 1036.64     .06       0
 1056.64     .07       0 1153.52      .1       0
Bank Sta=639.4,746.55
XS Rating Curve= 0 ,0
Exp/Cntr(USF)=0,0
Exp/Cntr=0.3,0.1

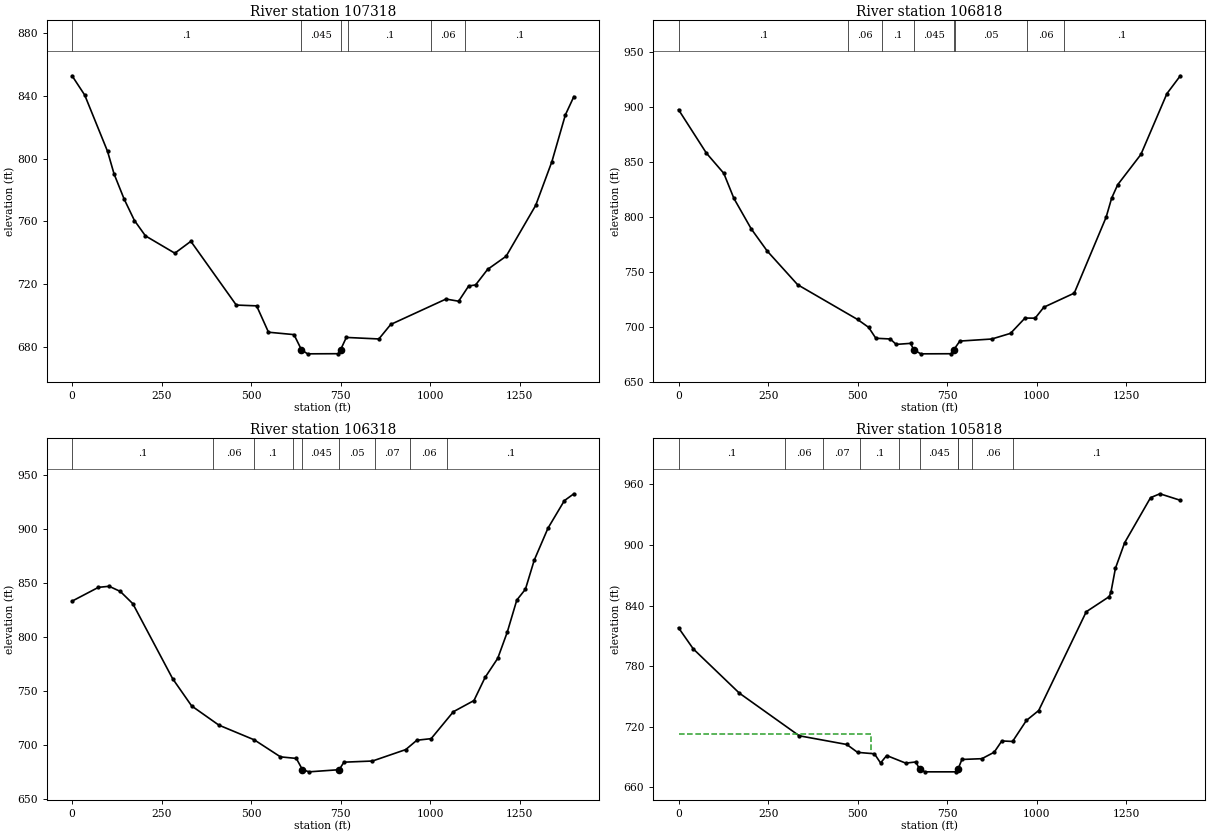
Type RM Length L Ch R = 1 ,107318  ,478.2,500,524.7
XS GIS Cut Line= 6
1624938.35563435388149.557332337  1625097.692586388400.512867168
1625199.86954701388561.4406949281625427.67289717388920.231315926
1625529.84985818389081.1591436711625689.18680984389332.114678502
#Sta/Elev= 30
       0  852.93    35.3  840.62    99.1  804.62   117.2  790.26   145.4  774.17
   174.1   760.5   204.8  750.69   286.9  739.62   331.6  747.21   458.4  706.49
   515.2  705.99   548.3  689.15   619.5  687.62  640.46677.9074   657.4  675.34
   742.7  675.43   749.5  677.89   765.6  685.82   856.4  684.84   889.6  694.12
  1043.8  710.33  1079.1  708.95  1107.1  718.66  1126.5  719.36    1160  729.27
  1211.8  737.69  1294.3  770.19  1339.5  798.11  1377.1  827.96  1400.8  839.63
#Mann= 6 ,-1,0
       0      .1       0  640.46    .045       0   749.5    .025       0
  770.39      .1       0 1002.89     .06       0 1096.64      .1       0
Bank Sta=640.46,749.5
XS Rating Curve= 0 ,0
Exp/Cntr(USF)=0,0
Exp/Cntr=0.3,0.1

Type RM Length L Ch R = 1 ,106818  ,514.7,500,483
XS GIS Cut Line= 6
1624752.83697651388227.6165594161624823.82338309388710.315397173
1624862.01654817 388970.022226841624899.29961009389223.545341834
1624942.15319893389514.9423968341624956.64693634 389613.49174042
#Sta/Elev= 30
       0  897.72    77.7  858.19   126.3  839.77   154.6   816.9   203.1  789.07
   247.6  768.94   332.5  738.28   499.7  706.63   530.6  699.47   550.8   689.5
   591.2  688.85   607.4  683.92   647.8  684.85  656.42679.1635   676.1  675.31
     761   675.4   768.6  679.16   785.3  686.94   874.3  688.81   926.8  693.97
   967.2  707.91   995.5   707.8  1019.8  717.79  1104.7  730.62  1193.6  799.71
  1209.1  817.15    1226   829.4  1290.7  856.93  1363.4  912.37  1400.8  928.61
#Mann= 8 ,-1,0
       0      .1       0  474.14     .06       0  567.89      .1       0
  656.42    .045       0   768.6    .025       0  770.39     .05       0
  972.89     .06       0 1076.64      .1       0
Bank Sta=656.42,768.6
XS Rating Curve= 0 ,0
Exp/Cntr(USF)=0,0
Exp/Cntr=0.3,0.1

Type RM Length L Ch R = 1 ,106318  ,498,500,506.3
XS GIS Cut Line= 6
1624079.83701017388438.9271604271624165.07043551388618.559675172
1624207.26884192388707.4935524171624288.98587009388879.714992762
 1624326.4956376388958.7673280841624680.32432626389704.471545339
#Sta/Elev= 30
       0  832.94    73.5  845.69   103.5  846.67   134.6  841.92   169.6  830.57
   280.7  761.29   333.8  736.09   409.8  718.34   508.9  704.69   581.8     689
     626  687.57   643.1677.1874   661.5  675.16  745.61677.1384   758.9  684.09
   838.6  685.16   931.5  695.73   962.5  704.37  1002.4  705.84  1064.4  730.72
  1121.9  741.05  1152.9  762.39  1188.3  780.08  1214.9  804.29  1241.5  833.92
  1265.6  843.96  1290.2  870.84  1328.6  900.42  1374.3  925.84  1400.8  932.18
#Mann= 9 ,-1,0
       0      .1       0  394.14     .06       0  507.89      .1       0
  615.39    .025       0   643.1    .045       0  745.61     .05       0
  845.39     .07       0  942.89     .06       0 1046.64      .1       0
Bank Sta=643.1,745.61
XS Rating Curve= 0 ,0
Exp/Cntr(USF)=0,0
Exp/Cntr=0.3,0.1

Type RM Length L Ch R = 1 ,105818  ,499.6,500,502
XS GIS Cut Line= 6
1623671.06289335388618.066237837 1623706.7901841 388711.04800725
1623812.43006468388985.9821686741623904.33932967389225.182477668
1623967.10692067389388.5384501671624173.48282026389925.644987509
#Sta/Elev= 30
       0  817.92    41.2  796.97   169.8  753.15   336.9   710.9   469.7  702.27
   499.7  694.47   546.9  693.04     564  683.94   581.1  691.32   634.2  683.79
   662.6  684.96     673677.6409   688.3  675.16     774  675.16  780.16677.8301
   791.1  687.43   846.8  688.19   881.1  694.58   902.5  705.78   932.5  705.27
   971.1  726.09  1005.4  735.92  1138.2  833.83  1202.5  848.86  1207.4  853.76
  1219.6  876.84  1245.3   902.2  1317.7  946.91  1343.9  950.74  1400.8  944.28
#Mann= 10 ,-1,0
       0      .1       0  297.27     .06       0  404.14     .07       0
  507.89      .1       0  615.39    .025       0     673    .045       0
  780.16      .1       0  780.39     .05       0  820.39     .06       0
  932.89      .1       0
#XS Ineff= 2 , 0
          536.33  713.03
Permanent Ineff=
       F       F
Bank Sta=673,780.16
XS Rating Curve= 0 ,0
Exp/Cntr(USF)=0,0
Exp/Cntr=0.3,0.1