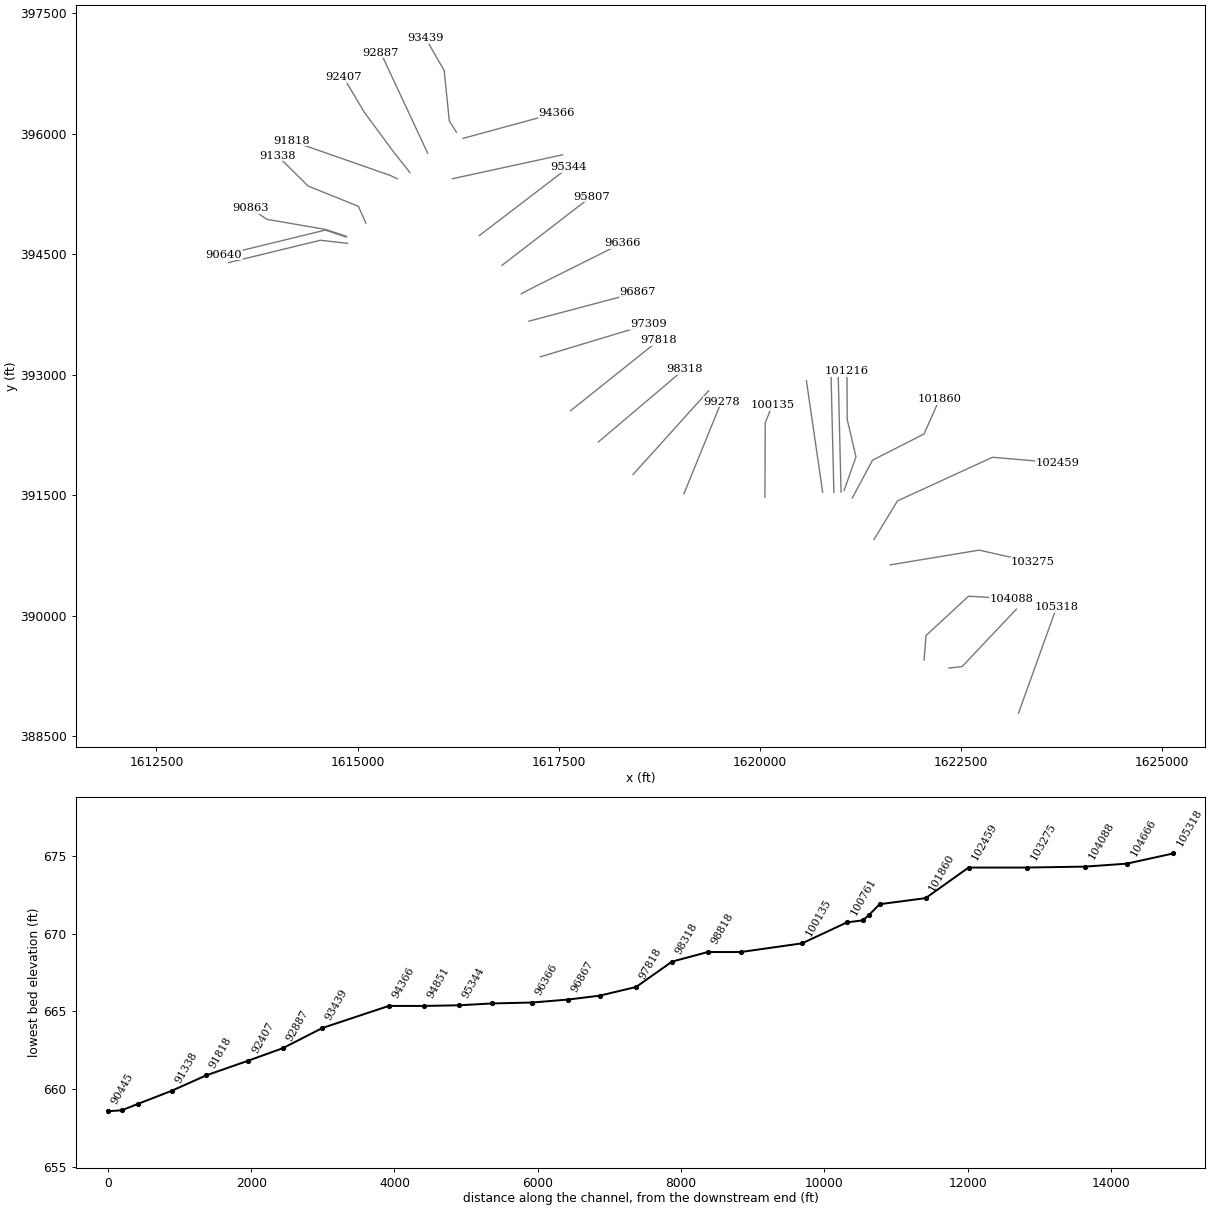
HEC-RAS study FISHINGCK.prj: FISHINGCK

--- FISHINGCK.g01 (geometry) --- (continued)

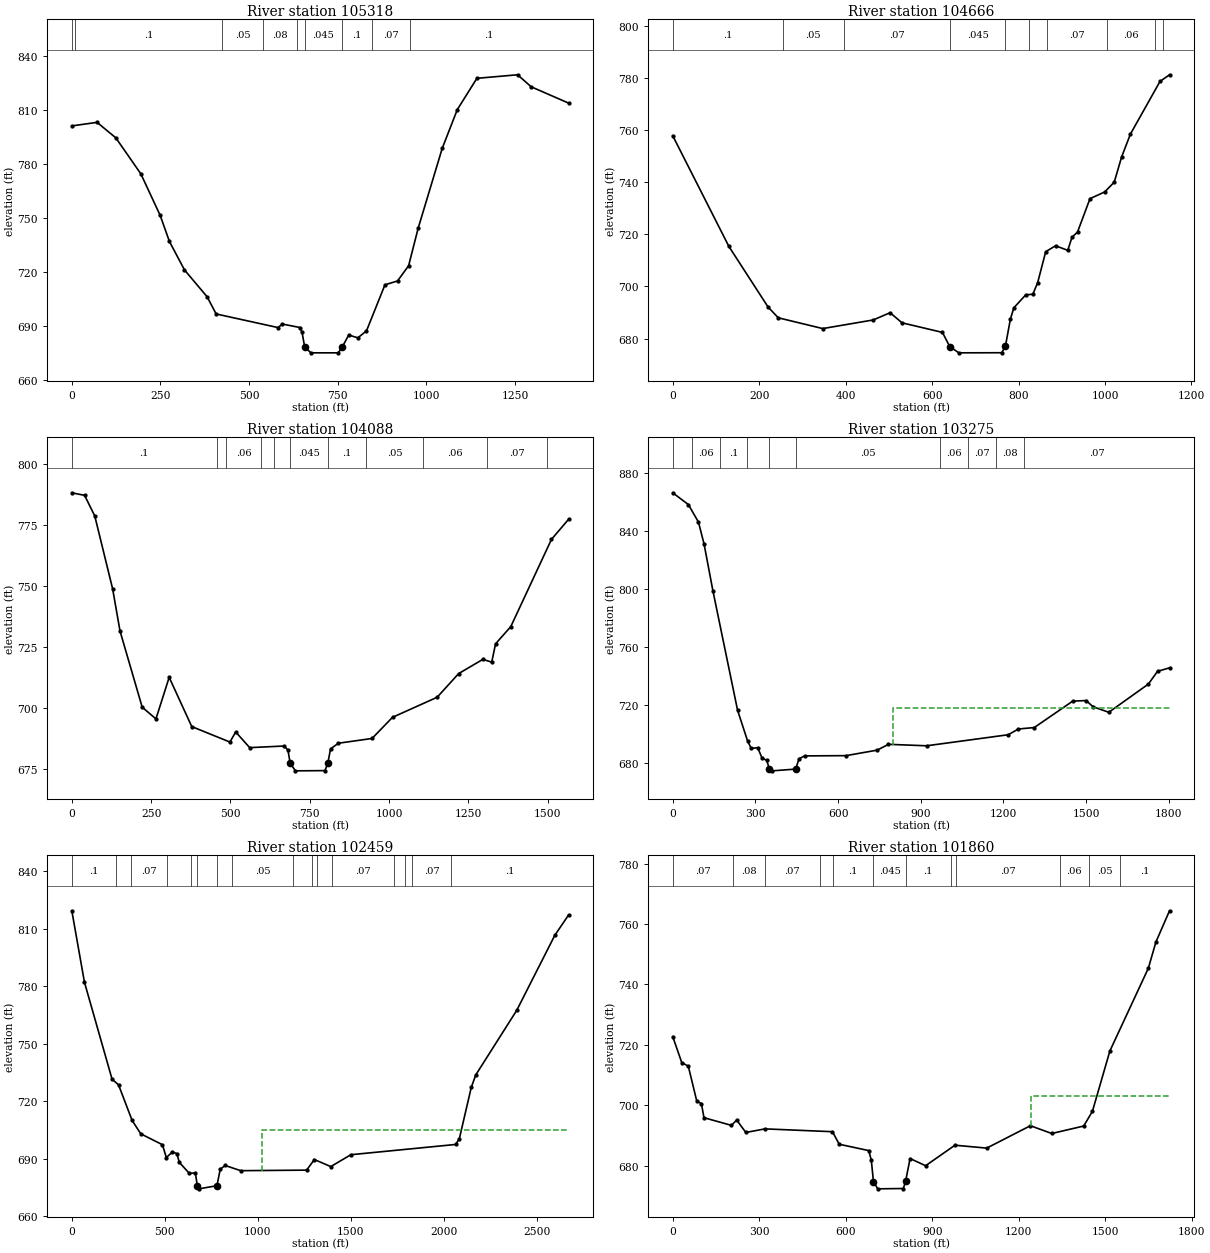
Type RM Length L Ch R = 1 ,105318  ,675.3,651.8,626.1
XS GIS Cut Line= 6
1623216.34497076388785.4963491711623381.26918159389244.661113262
1623524.94999659389644.6370193361623589.38982834389824.044140846
1623656.20596768390010.0654223411623689.87781633390103.811297834
#Sta/Elev= 30
       0  801.18    71.2  803.16   124.2  794.53   194.5  774.61   249.2  751.47
   275.2  737.02   317.7  721.21   381.5  706.29     407  696.75   581.3   689.2
     594  691.13   643.2  689.23   649.3  686.54  656.71678.3141   674.5  675.16
   751.3  675.16  762.33678.3052   780.8  685.07   806.5  683.49   830.9  687.35
     883  712.94   918.4  715.06   949.7  723.53   976.5  744.28  1044.5  788.72
    1087  810.24  1142.3  827.62    1257  829.58  1295.3  822.91  1400.8  813.85
#Mann= 9 ,-1,0
       0     .06       0      10      .1       0  424.14     .05       0
  537.89     .08       0  635.39     .07       0  656.71    .045       0
  762.33      .1       0  845.39     .07       0  952.89      .1       0
Bank Sta=656.71,762.33
XS Rating Curve= 0 ,0
Exp/Cntr(USF)=0,0
Exp/Cntr=0.3,0.1

Type RM Length L Ch R = 1 ,104666  ,580,578.1,574.6
XS GIS Cut Line= 3
1622351.02154946389349.5344835481622515.15613627389367.120332134
1623191.23431527390082.278174663
#Sta/Elev= 30
       0  757.77   129.8  715.33   220.5  692.08   244.1  687.94     347  683.81
   463.9  687.12   502.8   689.9   530.3  686.02   623.9  682.34  640.62  676.93
   661.9   674.5     761  674.54   769.5     677     781  687.38     789  691.77
   816.6  696.74   833.1  696.99   844.1   701.4   862.8  713.31   885.5  715.57
   913.8  713.82   923.4  718.78   936.4  720.86   965.2  733.65   999.1  736.21
  1021.3  739.97  1038.3  749.61  1058.7  758.41  1127.2  778.63  1149.2  781.17
#Mann= 10 ,-1,0
       0      .1       0  255.07     .05       0  395.07     .07       0
  640.62    .045       0   769.5      .1       0  825.07     .06       0
  865.07     .07       0 1005.07     .06       0 1115.07      .1       0
 1135.07     .06       0
Bank Sta=640.62,769.5
XS Rating Curve= 0 ,0
Exp/Cntr(USF)=0,0
Exp/Cntr=0.3,0.1

Type RM Length L Ch R = 1 ,104088  ,838.4,813.2,781.6
XS GIS Cut Line= 4
1622043.07246268389448.3355309861622067.86419784389754.100264573
1622596.19679291390243.4866720511623133.90880954390212.747364955
#Sta/Elev= 30
       0   788.3    40.3  787.24    72.4  778.76   128.6  748.93   151.9  731.62
   221.8   700.4   265.1   695.6   306.8  712.64     378  692.45   498.3  686.11
   516.4  690.25   560.6  683.82   669.4  684.49   681.2  682.78  688.04  677.47
   704.7  674.31   797.8   674.4   806.8  677.43   815.3   683.3   840.1  685.63
   946.1  687.58  1010.6  696.25  1151.1  704.46  1219.2  714.19  1295.3     720
  1323.3  718.88  1335.4  726.39  1383.4  733.44  1511.6  769.21  1565.5  777.43
#Mann= 11 ,-1,0
       0      .1       0  456.77     .05       0  486.77     .06       0
  596.77     .07       0  636.77    .025       0  688.04    .045       0
   806.8      .1       0  926.77     .05       0 1106.93     .06       0
 1306.93     .07       0 1496.93     .06       0
Bank Sta=688.04,806.8
XS Rating Curve= 0 ,0
Exp/Cntr(USF)=0,0
Exp/Cntr=0.3,0.1

Type RM Length L Ch R = 1 ,103275  ,803.8,816.4,831.4
XS GIS Cut Line= 3
1621620.01083624390633.0128386831622728.27129015390816.899220044
1623390.94077907390667.263506392
#Sta/Elev= 30
       0  866.27    56.9  858.08    93.4  845.97   113.6   830.9   146.1   798.2
   235.3  716.03   271.8  694.74   284.8  689.76   308.3  690.24   324.5  682.81
   340.7  681.66  350.73  675.53     361  674.25   445.8675.4477   458.3  682.59
   478.6  684.57   628.6  684.74   742.1  688.55   782.7  692.56   921.3  691.55
  1217.6  699.18  1254.5  703.15  1311.9  704.14  1451.4  722.38  1500.5  722.79
  1525.1  718.51  1582.5  714.69  1726.1  734.18  1759.2  742.96  1802.8  745.38
#Mann= 10 ,-1,0
       0      .1       0      70     .06       0     170      .1       0
     270     .07       0  350.73    .045       0   445.8     .05       0
     970     .06       0    1070     .07       0 1173.41     .08       0
 1273.41     .07       0
#XS Ineff= 2 , 0
                          799.51          717.34
Permanent Ineff=
       F       F
Bank Sta=350.73,445.8
XS Rating Curve= 0 ,0
Exp/Cntr(USF)=0,0
Exp/Cntr=0.3,0.1

Type RM Length L Ch R = 1 ,102459  ,597.2,599.1,601.3
XS GIS Cut Line= 4
1621421.48347547390949.7228190441621712.25073964391429.233745925
1622893.57826686391972.2894721951623701.71096819391903.643492732
#Sta/Elev= 30
       0  819.28      68  781.99   216.5  731.44   251.2  728.51   324.3  709.93
   370.9  702.95   487.4  697.26   508.5  690.55   541.3  693.53     565   692.6
   578.2  688.06   632.5  682.27   664.5  682.58   675.1  675.88   683.8  674.25
  780.54  675.89   798.4  684.53   824.8  686.43   908.4  683.72  1262.9  684.01
  1304.6  689.53    1393  685.86  1501.1  692.05  2064.2  697.39  2084.3  700.34
  2148.5  727.15  2172.6  733.64  2393.4   767.4  2598.1  806.52    2672  817.08
#Mann= 16 ,-1,0
       0      .1       0     240     .06       0     320     .07       0
     510     .06       0  640.78      .1       0   675.1    .045       0
  780.54      .1       0  860.78     .05       0 1190.78     .06       0
 1290.78     .07       0 1320.78     .06       0 1400.78     .07       0
 1730.78     .06       0 1790.78     .08       0 1830.78     .07       0
 2040.95      .1       0
#XS Ineff= 2 , 0
                         1022.14          704.93
Permanent Ineff=
       F       F
Bank Sta=675.1,780.54
XS Rating Curve= 0 ,0
Exp/Cntr(USF)=0,0
Exp/Cntr=0.3,0.1

Type RM Length L Ch R = 1 ,101860  ,596.4,643.3,720.5
XS GIS Cut Line= 4
1621150.58680067391465.0026803931621402.43352117391936.129735125
1622042.90578452392261.7935978431622233.96191731 392691.66989663
#Sta/Elev= 30
       0  722.68    31.2  714.09    53.9  712.91    83.5  701.27    99.3  700.54
   108.3  695.84   203.6   693.3   221.7  695.07   253.5  690.95     320  692.14
   554.1   691.2   577.4  687.05   679.7  684.95   688.7  681.81  696.19  674.68
   711.1  672.28   799.9  672.39   807.5674.7527   823.3  682.31   877.1  679.94
     979  686.73  1089.1  685.77  1240.6  693.18  1314.8  690.61  1425.4  693.08
  1455.7  697.94  1516.3  717.94  1649.7  745.34    1676  754.03  1723.2  764.37
#Mann= 12 ,-1,0
       0     .07       0     210     .08       0     320     .07       0
     510     .06       0  554.22      .1       0  696.19    .045       0
   807.5      .1       0  964.22     .06       0  984.22     .07       0
 1342.73     .06       0 1442.73     .05       0 1552.73      .1       0
#XS Ineff= 2 , 0
                         1241.18          703.13
Permanent Ineff=
       F       F
Bank Sta=696.19,807.5
XS Rating Curve= 0 ,0
Exp/Cntr(USF)=0,0
Exp/Cntr=0.3,0.1

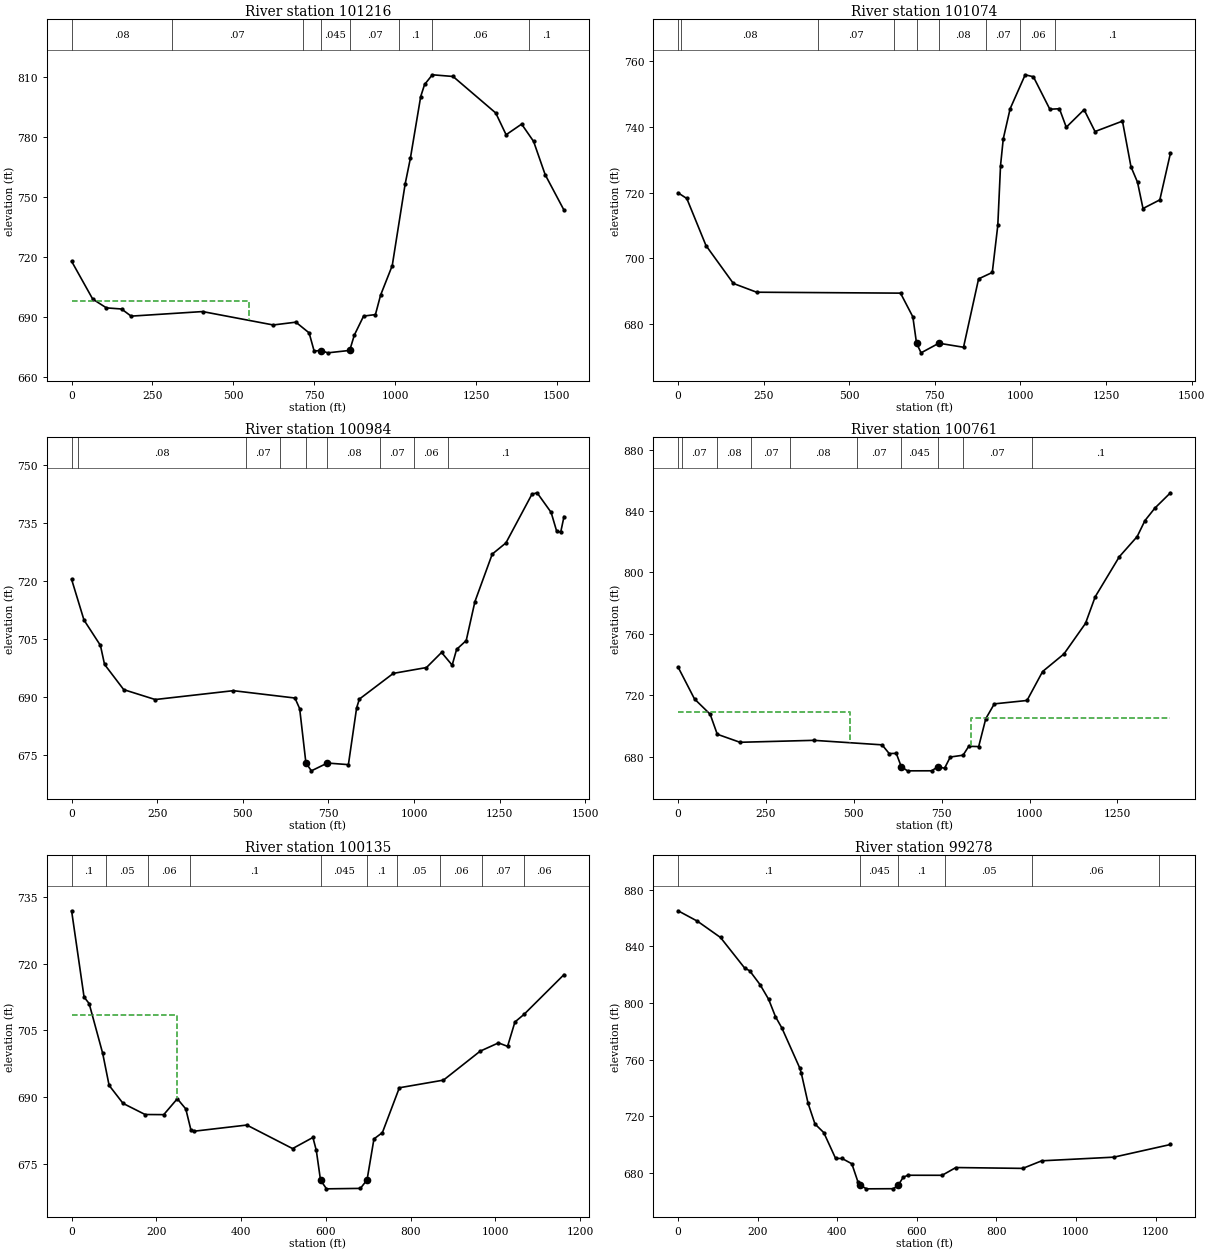
Type RM Length L Ch R = 1 ,101216  ,144.8,141.9,138.2
XS GIS Cut Line= 4
1621049.32863551391558.9501198381621196.65365135391977.779412108
1621087.64816038 392444.860905121621084.61202951393043.553777918
#Sta/Elev= 30
       0  717.72    65.3  698.79   107.7  694.39   154.3  693.84     184  690.26
   404.9  692.55   623.4  685.84   693.3  687.24   734.3  681.88   749.8   672.8
   771.3  673.06   791.8  671.89   859.8   673.1     874  680.74   902.7  690.28
   939.3  691.04   955.3  700.78   991.3  715.55  1031.3   756.5  1047.3  769.21
  1079.3  800.18  1091.3  806.21  1115.3  811.07  1179.3  810.22  1311.3  791.94
  1343.3  781.06  1391.3  786.38  1428.3  777.71  1464.1  761.06  1522.3  743.31
#Mann= 8 ,-1,0
       0     .08       0     310     .07       0  713.98      .1       0
   771.3    .045       0   859.8     .07       0 1013.62      .1       0
 1113.62     .06       0 1413.62      .1       0
#XS Ineff= 2 , 0
          546.99  698.04
Permanent Ineff=
       F       F
Bank Sta=771.3,859.8
XS Rating Curve= 0 ,0
Exp/Cntr(USF)=0,0
Exp/Cntr=0.3,0.1

Type RM Length L Ch R = 1 ,101074  ,90.1,90,90.5
XS GIS Cut Line= 2
1621011.08953004391539.0556159381620976.47968189392976.695462272
#Sta/Elev= 30
       0  719.94    25.5  718.22    81.5   703.9   161.5  692.35   229.5  689.68
   649.7   689.4   685.7  682.18  696.45  674.16   709.7  671.22   761.7  674.15
   833.7  672.92   877.7  693.74   917.7   695.7   933.8  710.01   941.8  728.26
   949.8   736.4   969.8  745.54  1013.8  755.89  1037.8  755.28  1085.8   745.4
  1113.8  745.55  1133.8  739.92  1185.8  745.26  1217.8  738.61  1297.9  741.78
  1322.7  727.91  1341.9  723.16  1357.9  715.17    1407   717.8  1438.1  732.05
#Mann= 9 ,-1,0
       0     .07       0      10     .08       0     410     .07       0
     630      .1       0  696.45    .045       0   761.7     .08       0
     900     .07       0    1000     .06       0    1100      .1       0
Bank Sta=696.45,761.7
XS Rating Curve= 0 ,0
Exp/Cntr(USF)=0,0
Exp/Cntr=0.3,0.1

Type RM Length L Ch R = 1 ,100984  ,221.4,222.7,228.3
XS GIS Cut Line= 2
1620921.90261365391536.393319926 1620887.2927655392974.033166261
#Sta/Elev= 30
       0  720.34    36.2  709.82    84.2  703.27    96.2  698.36   152.2  691.84
   244.2  689.28   472.3  691.57   652.3  689.67   666.1  686.92   684.3  672.91
   700.3  670.85  747.07672.8663   808.4  672.45   832.4   687.1   840.4  689.39
   939.6  696.04  1036.4  697.55  1080.5  701.45  1111.5  698.17  1124.5  702.25
  1152.5  704.52  1177.9  714.58  1228.5  726.87  1268.5  729.76  1344.5  742.35
  1359.5  742.72  1400.5  737.65  1416.9  732.72  1428.6  732.59  1438.1  736.56
#Mann= 9 ,-1,0
       0      .1       0      20     .08       0     510     .07       0
     610      .1       0   684.3    .045       0  747.07     .08       0
     900     .07       0    1000     .06       0    1100      .1       0
Bank Sta=684.3,747.07
XS Rating Curve= 0 ,0
Exp/Cntr(USF)=0,0
Exp/Cntr=0.3,0.1

Type RM Length L Ch R = 1 ,100761  ,632.5,626.7,616
XS GIS Cut Line= 6
1620782.49840455 391538.22961651 1620739.6589233391832.392085927
1620712.18719347392021.0272073471620650.93994063392441.590998756
1620637.42914088392534.3621386761620580.62872955392924.388589593
#Sta/Elev= 30
       0  738.32    46.8  717.53    91.3  707.59   111.5  694.56   176.1  689.32
   386.3  690.59   580.4  687.65   600.6  681.99   620.8   682.1   635.1  673.36
   652.8  670.72   721.8  670.75   738.5673.3967   758.2  672.42   774.4  679.72
   810.8  680.91   826.9  686.71   855.2  686.52   875.4   704.7   899.7  714.35
   992.7  716.56  1037.1  735.42  1097.8  746.87  1159.1  766.79  1186.7  784.12
  1255.4  810.23  1306.1  823.33  1328.2  833.75  1356.5  841.88  1400.8  851.86
#Mann= 10 ,-1,0
       0      .1       0      10     .07       0  109.61     .08       0
  208.83     .07       0  317.27     .08       0  507.89     .07       0
   635.1    .045       0   738.5     .05       0  810.39     .07       0
 1006.64      .1       0
#XS Ineff= 2 , 0
          487.92  709.22  834.61          705.07
Permanent Ineff=
       F       F
Bank Sta=635.1,738.5
XS Rating Curve= 0 ,0
Exp/Cntr(USF)=0,0
Exp/Cntr=0.3,0.1

Type RM Length L Ch R = 1 ,100135  ,875.4,857,841.5
XS GIS Cut Line= 4
1620064.49291594391475.1728116661620065.95206541391723.728599587
1620068.81040319392402.7625413481620156.50844549392619.900706604
#Sta/Elev= 30
       0  731.88    29.4  712.49    41.4  711.02    73.4  699.81    88.5  692.63
   121.4  688.58   173.4  686.08   217.4  686.05   249.4  689.62   269.4  687.34
   281.4  682.66   289.4  682.33   413.4  683.71   521.4  678.42   569.4  680.92
   577.4  677.99  587.27  671.35   601.4  669.37   681.4  669.47   697.1  671.38
   713.4  680.59   733.3  682.01   773.3  692.09   877.4  693.81     964  700.32
  1007.2  702.18  1028.7   701.4    1046  706.88  1067.6   708.6  1161.8  717.53
#Mann= 10 ,-1,0
       0      .1       0      80     .05       0     180     .06       0
  278.56      .1       0  587.27    .045       0   697.1      .1       0
  768.56     .05       0  868.56     .06       0   967.6     .07       0
  1067.6     .06       0
#XS Ineff= 2 , 0
          249.45  708.39
Permanent Ineff=
       F       F
Bank Sta=587.27,697.1
XS Rating Curve= 0 ,0
Exp/Cntr(USF)=0,0
Exp/Cntr=0.3,0.1

Type RM Length L Ch R = 1 ,99278   ,476.7,459.7,442.8
XS GIS Cut Line= 2
1619057.78209367391517.7389161741619523.93132313392664.211369067
#Sta/Elev= 30
       0  865.02    48.7  857.67   106.7  846.17   167.1   824.7   180.1  822.65
     206  812.94   227.6  802.58   244.8  790.32   261.1  782.21   305.3  754.41
   309.6  750.62   326.9  729.06   344.1  714.58   366.2   708.5     396  690.25
   412.2  690.25   436.8  686.48   452.1  673.72  457.18  671.48   473.5  668.81
   541.2   668.9   553.5671.4518   565.7  676.93   577.3   678.4   663.7  678.37
   698.2  683.84   866.4  683.24   914.1  688.59  1095.5  691.17  1237.6   700.1
#Mann= 6 ,-1,0
       0      .1       0  457.18    .045       0   553.5      .1       0
     670     .05       0     890     .06       0    1210     .07       0
Bank Sta=457.18,553.5
XS Rating Curve= 0 ,0
Exp/Cntr(USF)=0,0
Exp/Cntr=0.3,0.1

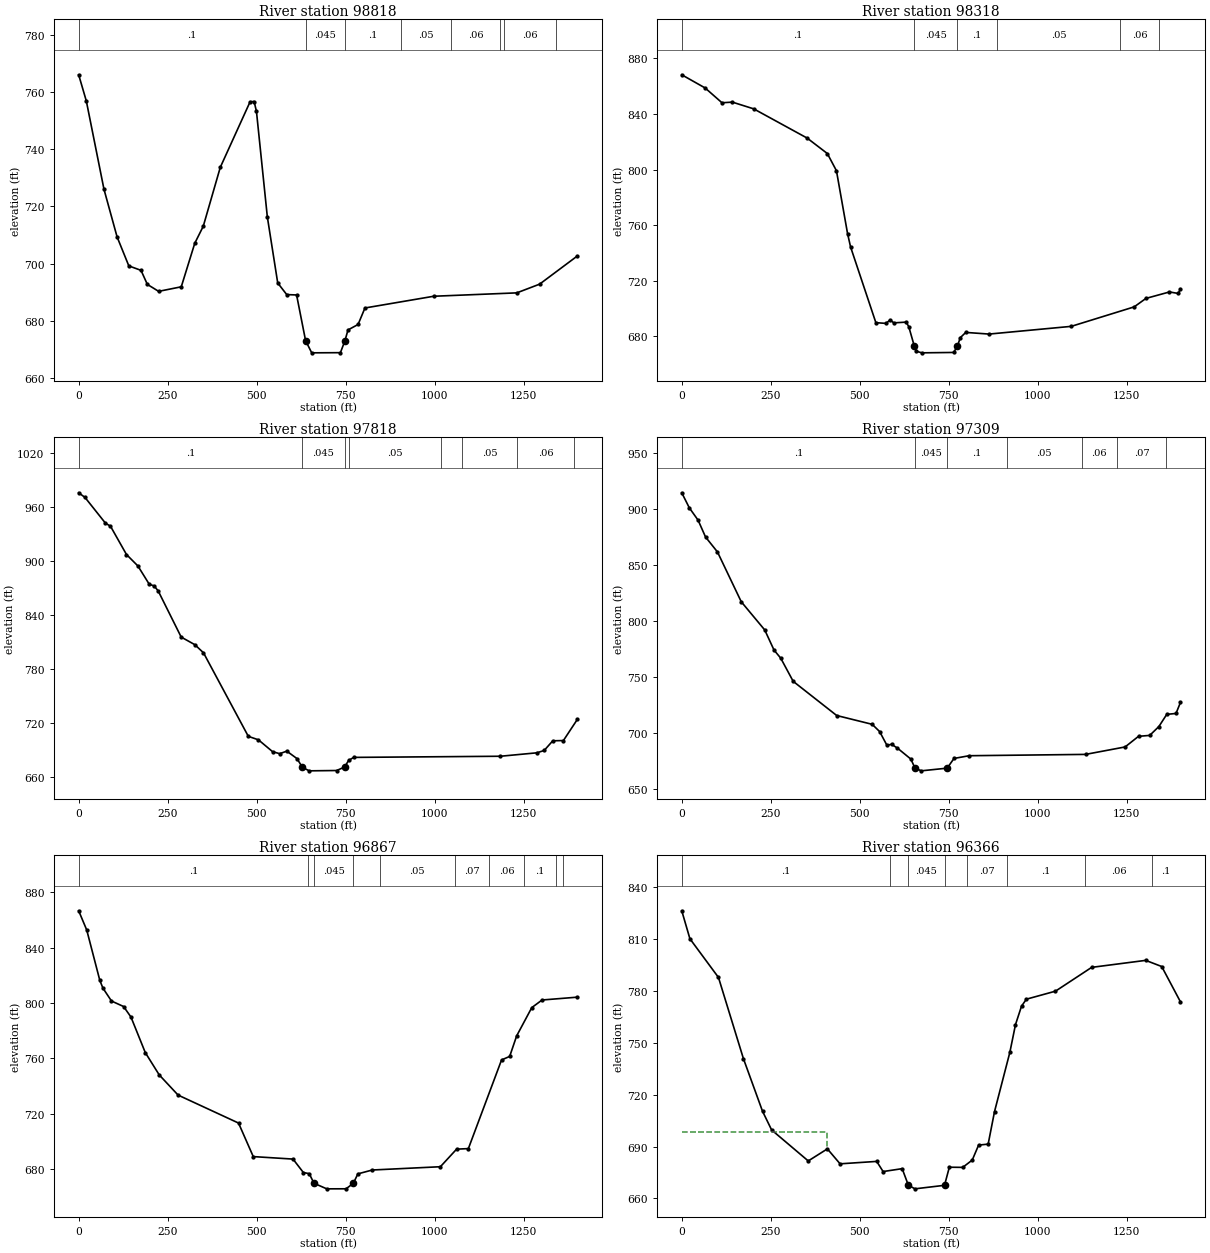
Type RM Length L Ch R = 1 ,98818   ,506,500,490.3
XS GIS Cut Line= 6
1618425.74530001391758.4700620031618558.86970568391906.154149845
1618861.20965217392241.5632559211619099.73410951392506.176243752
1619296.93581484392724.9461474271619363.62826675392798.933532253
#Sta/Elev= 30
       0  765.95    21.5   756.8    71.1  725.95   107.9  709.32   140.9  699.18
   175.1  697.63   192.9  692.72   224.6  690.29   288.2  691.88   326.1  707.09
     350  713.04   397.8  733.62   481.5  756.52   492.8  756.61   499.4  753.14
   529.9  716.33   559.1  693.22   584.4  689.16   612.1  689.03  637.38  673.07
   654.6  668.81   735.2  668.87  747.86 673.024   756.5  676.81   784.8  678.72
   804.1  684.48   997.3  688.58  1230.6  689.76  1294.6   692.8  1400.8  702.66
#Mann= 8 ,-1,0
       0      .1       0  637.38    .045       0  747.86      .1       0
  905.39     .05       0 1046.64     .06       0 1183.52     .05       0
 1193.52     .06       0 1341.17     .07       0
Bank Sta=637.38,747.86
XS Rating Curve= 0 ,0
Exp/Cntr(USF)=0,0
Exp/Cntr=0.3,0.1

Type RM Length L Ch R = 1 ,98318   ,503.4,500,500.1
XS GIS Cut Line= 6
1617993.92201668392162.3294905131618294.45750484392417.329964757
1618566.10164659392647.8153961751618623.28952435392696.338921174
 1618761.4946285392813.6034504181619062.03011668393068.603924677
#Sta/Elev= 30
       0  868.19    65.6  858.71     113  848.06   142.2  848.52   202.2  843.67
   352.2  822.66   408.9  811.55   434.5  799.17   465.7  753.95   474.2  744.33
   545.2   689.9   573.5  689.37   585.2  691.82   595.7  689.74   630.3  690.29
   637.6  687.05  653.42  672.81   658.8  669.35   674.3  668.19   763.7  668.47
  774.04 672.877   782.4  679.11   797.7  682.88   863.2  681.69    1094  687.24
  1270.8  701.25  1303.8  707.34  1369.8  711.98  1394.5  710.91  1400.8  714.16
#Mann= 6 ,-1,0
       0      .1       0  653.42    .045       0  774.04      .1       0
  885.39     .05       0 1231.95     .06       0 1341.17     .07       0
Bank Sta=653.42,774.04
XS Rating Curve= 0 ,0
Exp/Cntr(USF)=0,0
Exp/Cntr=0.3,0.1

Type RM Length L Ch R = 1 ,97818   ,530.5,509.5,491.1
XS GIS Cut Line= 6
1617650.32198209392552.6147991721617958.09466051392798.831826419
1618512.02399884393241.9743128421618588.89097109393303.467300087
1618666.36785026393365.4488034251618744.14984693393427.674072668
#Sta/Elev= 30
       0  975.98    17.7  970.84    75.2  942.18    89.4  938.75   134.3  907.28
   166.4  894.54   198.4  874.11   211.8  872.39   223.2  866.89     288   815.4
   326.4  806.92   350.6  797.92   476.5  704.95   504.9  701.07   544.8  687.86
   564.7  685.66   584.6  688.48   613.1  680.22  628.09670.7177   647.2  666.56
   724.6  666.92   746.8  670.78   758.2  678.08   772.4  681.52  1184.5  682.79
  1286.9  686.61  1307.5  689.23  1331.7  699.99  1361.5  700.26  1400.8  723.87
#Mann= 8 ,-1,0
       0      .1       0  628.09    .045       0   746.8      .1       0
  760.39     .05       0 1016.64     .06       0 1076.64     .05       0
 1231.95     .06       0 1391.17      .1       0
Bank Sta=628.09,746.8
XS Rating Curve= 0 ,0
Exp/Cntr(USF)=0,0
Exp/Cntr=0.3,0.1

Type RM Length L Ch R = 1 ,97309   ,443.4,441.8,440
XS GIS Cut Line= 6
1617272.13966759393221.9629374011617556.68568642393307.988683985
1617649.41581592393336.0230767441617894.70108651393410.179424481
1617990.42235176393439.1180149031618612.98344259393627.334173904
#Sta/Elev= 30
       0  914.44    21.3  900.96    45.9  889.95    66.8  874.93   100.3  861.57
   167.1  817.08   233.1  791.86   259.1  773.93     278  766.67     313  745.96
   435.2  715.43   534.9  707.56   555.8  701.08   576.4  688.75   589.2  689.74
   605.9  686.28   643.5   676.5     655  668.49   672.7     666   745.5668.4037
   764.7  677.09   807.4  679.51  1134.1  680.69  1245.3  687.35  1282.9  696.83
  1314.4  697.67  1340.1  705.57  1362.3  716.48  1388.2  717.26  1400.8  727.14
#Mann= 7 ,-1,0
       0      .1       0     655    .045       0   745.5      .1       0
  912.89     .05       0 1123.52     .06       0 1221.95     .07       0
 1361.17     .06       0
Bank Sta=655,745.5
XS Rating Curve= 0 ,0
Exp/Cntr(USF)=0,0
Exp/Cntr=0.3,0.1

Type RM Length L Ch R = 1 ,96867   ,488.5,500.2,510.1
XS GIS Cut Line= 6
1617130.17135519393665.6626764921617417.47393018393741.978140661
1617686.27785452393813.3789164961617927.89876235393877.559890503
1618196.70268669393948.9606663381618484.00526169394025.276130491
#Sta/Elev= 30
       0  866.68    22.7  852.76    59.5   816.3    68.2  810.77    92.2  801.47
   126.2  797.49   146.9  789.89   187.1  764.22   226.3  748.08   279.3  733.49
     449  713.29   490.4  689.05   602.1  687.25   631.1  677.55   647.6  676.72
     661669.7806   696.8  665.75   751.1  665.78   771.5  669.75   784.2  676.57
   824.7  679.36    1016  681.73  1061.5  694.43  1094.6  694.82  1187.8  758.89
  1210.6  761.44  1230.2  776.27  1272.7  796.71  1301.6  802.21  1400.8  804.26
#Mann= 10 ,-1,0
       0      .1       0  645.39    .025       0     661    .045       0
   771.5    .025       0  845.39     .05       0 1056.64     .07       0
 1153.52     .06       0 1251.95      .1       0 1341.17     .05       0
 1361.17     .06       0
Bank Sta=661,771.5
XS Rating Curve= 0 ,0
Exp/Cntr(USF)=0,0
Exp/Cntr=0.3,0.1

Type RM Length L Ch R = 1 ,96366   ,548.5,559.8,568.7
XS GIS Cut Line= 6
 1617035.8481122394007.0333765241617123.85088894394053.761301438
1617212.19946553394098.9236126931617470.74488019394228.195991943
1617549.00751894394267.3268191911618287.25932327394636.453049446
#Sta/Elev= 30
       0  826.09    22.9  809.94   103.1  787.61   173.2  740.72   226.8  710.38
   252.4  699.56   355.3  681.67     409  688.63   444.7     680   547.6   681.4
   565.5  675.54   619.1  677.21  636.34  667.72   654.9  665.56     738667.5959
   751.6  678.04   789.1  677.95   815.9  682.16   833.8  690.82   860.6  691.37
   878.5  710.17   921.5  744.33   937.4  760.38   954.3  771.01     968  775.05
  1049.7  779.68  1151.3  793.42  1303.1  797.46  1348.1  793.91  1400.8  773.49
#Mann= 8 ,-1,0
       0      .1       0  585.42    .025       0  636.34    .045       0
     738      .1       0  800.42     .07       0  912.92      .1       0
 1133.55     .06       0 1321.21      .1       0
#XS Ineff= 2 , 0
          408.34  698.61
Permanent Ineff=
       F       F
Bank Sta=636.34,738
XS Rating Curve= 0 ,0
Exp/Cntr(USF)=0,0
Exp/Cntr=0.3,0.1

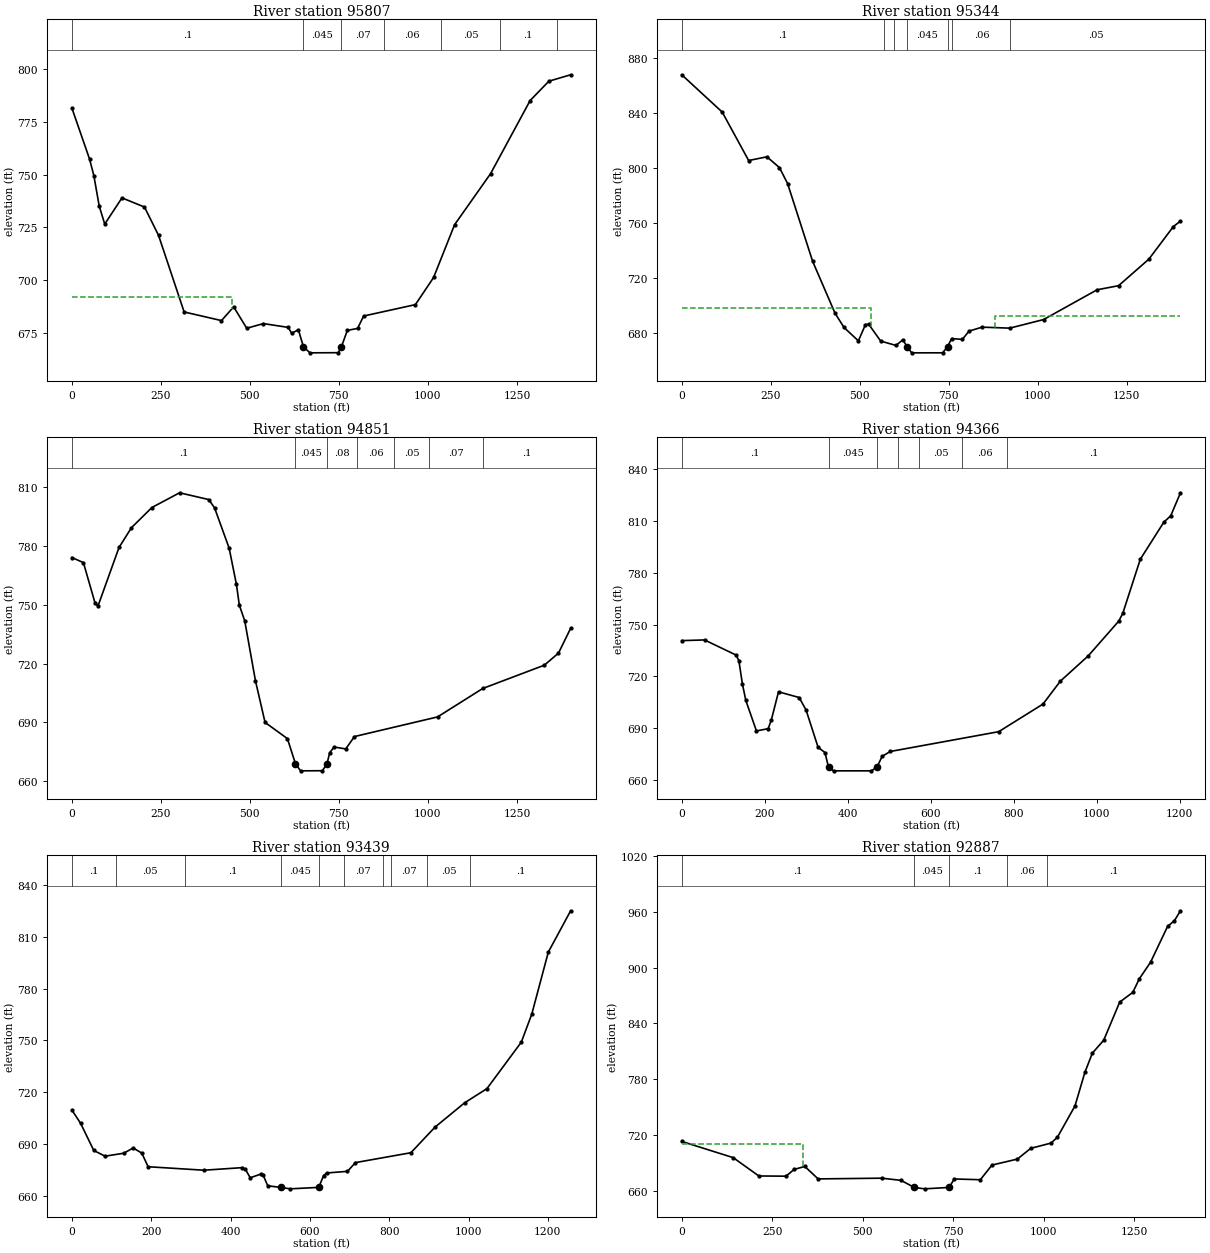
Type RM Length L Ch R = 1 ,95807   ,463.6,463.2,462.9
XS GIS Cut Line= 6
1616795.35847724394360.0348082351616952.78696814394481.479775326
1617107.43232815394600.7771089091617389.50459865394818.376083152
1617592.39887791394974.8941428231617904.47240073395215.636771576
#Sta/Elev= 30
       0  781.65    49.4  757.55    61.6  749.63    76.7  735.14    92.2  726.62
   140.6  739.05   203.8   734.7   243.3  721.27   315.2   684.9   420.1  680.81
   454.3  687.33     491  677.17   537.8  679.38   607.2  677.59   617.3  674.81
   636.1  676.46   650.4668.3033   668.8   665.5   748.1  665.57  756.91  668.34
   773.6  676.17   802.3  677.08   819.4  682.97   964.8  688.39  1015.9  701.27
  1074.8  726.31  1175.9  750.54  1287.1  785.27  1339.7  794.44  1400.8  797.48
#Mann= 7 ,-1,0
       0      .1       0   650.4    .045       0  756.91     .07       0
  875.39     .06       0 1036.64     .05       0 1201.95      .1       0
 1361.17     .05       0
#XS Ineff= 2 , 0
           448.6  691.89
Permanent Ineff=
       F       F
Bank Sta=650.4,756.91
XS Rating Curve= 0 ,0
Exp/Cntr(USF)=0,0
Exp/Cntr=0.3,0.1

Type RM Length L Ch R = 1 ,95344   ,514.2,492.2,471.1
XS GIS Cut Line= 6
1616514.06420226 394731.245697011616672.00483125394852.023670677
1617110.14207834 395187.071228941617313.69646126395342.730366427
1617390.64971943395401.5773616021617626.78474584395582.151475522
#Sta/Elev= 30
       0  867.91   113.7  840.72   187.9  805.46   239.2  808.17   274.5  800.27
   297.3  788.65   367.6  732.05   430.6  694.17   455.8  683.84   496.1   674.1
   515.7  685.81   524.6  686.39   558.8  673.94   601.8  670.76   621.1  674.97
   632.8 669.798   646.1  665.38   732.7   665.4  746.43  669.79   757.9  675.73
   788.1   675.2   807.1  681.23   843.5  684.08   921.2  683.37  1016.2  689.61
  1166.6  711.31  1226.9  714.29  1312.1  733.64  1380.6  757.29  1400.8  761.38
#Mann= 7 ,-1,0
       0      .1       0  567.89     .05       0  595.39      .1       0
   632.8    .045       0  746.43    .025       0  760.39     .06       0
  922.89     .05       0
#XS Ineff= 2 , 0
          530.27  697.71  881.09          692.53
Permanent Ineff=
       F       F
Bank Sta=632.8,746.43
XS Rating Curve= 0 ,0
Exp/Cntr(USF)=0,0
Exp/Cntr=0.3,0.1

Type RM Length L Ch R = 1 ,94851   ,483,485,487.4
XS GIS Cut Line= 6
1616180.59806702395438.6570387081616471.07911335395501.804550205
1616657.35334709395542.2992198811616742.85612884395560.886453037
1617452.07255818395715.0636381261617549.40864959395736.223372702
#Sta/Elev= 30
       0  774.01    32.3  771.44      65  750.81    73.2   749.3   132.3  779.14
   167.3  789.23   224.6   799.5   302.4  807.01   384.3  803.55   400.7  799.31
   441.6  778.79   462.1  760.32   470.2  749.78   485.4  741.78   515.6  711.17
   542.5  690.01   605.3  681.75  627.69  669.05   642.2  665.34   703.6   665.4
   716.6669.0214     724  674.52   736.3  677.48   769.1  676.51   793.6  682.81
    1027  692.81  1153.9   707.3  1326.9  719.17  1366.7  725.32  1400.8  737.97
#Mann= 7 ,-1,0
       0      .1       0  627.69    .045       0   716.6     .08       0
  800.39     .06       0  905.39     .05       0 1002.89     .07       0
 1153.52      .1       0
Bank Sta=627.69,716.6
XS Rating Curve= 0 ,0
Exp/Cntr(USF)=0,0
Exp/Cntr=0.3,0.1

Type RM Length L Ch R = 1 ,94366   ,850.6,927,997.8
XS GIS Cut Line= 6
1616311.12302026395940.4579305721616406.09199043395966.357813156
1616499.55341768395991.8475915711616674.41691311396039.537128738
1616746.77405185396059.2710131471617470.72404751396256.711563147
#Sta/Elev= 30
       0  740.76    54.9  741.16   131.2  732.37   137.7  729.08   146.1  715.76
   154.4  706.11     180  688.45   208.3  689.78   215.9  694.81   233.2  711.12
     283   707.8   299.5  700.64   328.6  678.96   345.2  675.93   353.7   667.4
   365.9  665.34   456.9  665.34   470.4 667.465     483  673.73   502.5  676.55
   763.9  688.02   870.7  704.03   912.4  717.27   979.5  731.89  1053.1  752.02
  1062.9  756.53  1105.2  787.92  1161.9  809.38  1178.5  813.08    1202   826.4
#Mann= 7 ,-1,0
       0      .1       0   353.7    .045       0   470.4     .07       0
  521.56     .08       0  571.56     .05       0  676.56     .06       0
  784.06      .1       0
Bank Sta=353.7,470.4
XS Rating Curve= 0 ,0
Exp/Cntr(USF)=0,0
Exp/Cntr=0.3,0.1

Type RM Length L Ch R = 1 ,93439   ,535.5,551.9,567.8
XS GIS Cut Line= 4
1616228.92889973 396018.00449883 1616140.7678872396157.411432689
1616077.45883229396783.4676423781615847.25435688397185.377546348
#Sta/Elev= 30
       0  709.57    21.9  701.93    55.1  686.17    83.6  682.86   130.8  684.58
   154.4  687.62   176.1  684.66   192.2  676.74   332.9  674.72   429.4  676.22
   437.5  675.23   449.5  670.34   477.7  672.58   481.7  672.13   493.7  665.68
   525.9  664.78     550  663.92   622.4  664.77   634.5  671.62   642.5  673.12
   694.8  674.07   714.9  679.14   854.6  684.86   915.3  699.67     990  713.79
  1046.4  722.05    1133  748.98  1159.4  765.22  1201.1   801.2  1257.4  825.18
#Mann= 10 ,-1,0
       0      .1       0     110     .05       0  284.94      .1       0
   525.9    .045       0   622.4      .1       0  684.94     .07       0
  784.94     .05       0  804.19     .07       0  894.19     .05       0
 1004.19      .1       0
Bank Sta=525.9,622.4
XS Rating Curve= 0 ,0
Exp/Cntr(USF)=0,0
Exp/Cntr=0.3,0.1

Type RM Length L Ch R = 1 ,92887   ,465.6,479.9,483.8
XS GIS Cut Line= 2
1615871.93872784395755.4597714251615289.09172719  397004.8123549
#Sta/Elev= 30
       0  713.45   142.1   696.1   213.1  676.42   288.1   676.2   310.7  683.46
   340.2  686.63   376.9  673.28   552.9  674.05   605.9  671.72     643  664.08
   671.3  662.62  739.24  664.14   753.1   673.2   825.4   672.4   857.5  688.12
   927.7  694.52   964.6  706.04  1020.8  711.71  1038.4  717.96    1087  751.56
  1114.3  787.51  1134.9  808.09  1166.5  822.11  1210.6  862.92  1246.7  873.33
  1264.8  887.89  1295.8  905.64  1342.9  944.04    1362  950.34  1378.6  960.87
#Mann= 5 ,-1,0
       0      .1       0     643    .045       0  739.24      .1       0
     900     .06       0    1010      .1       0
#XS Ineff= 2 , 0
          334.07  710.93
Permanent Ineff=
       F       F
Bank Sta=643,739.24
XS Rating Curve= 0 ,0
Exp/Cntr(USF)=0,0
Exp/Cntr=0.3,0.1

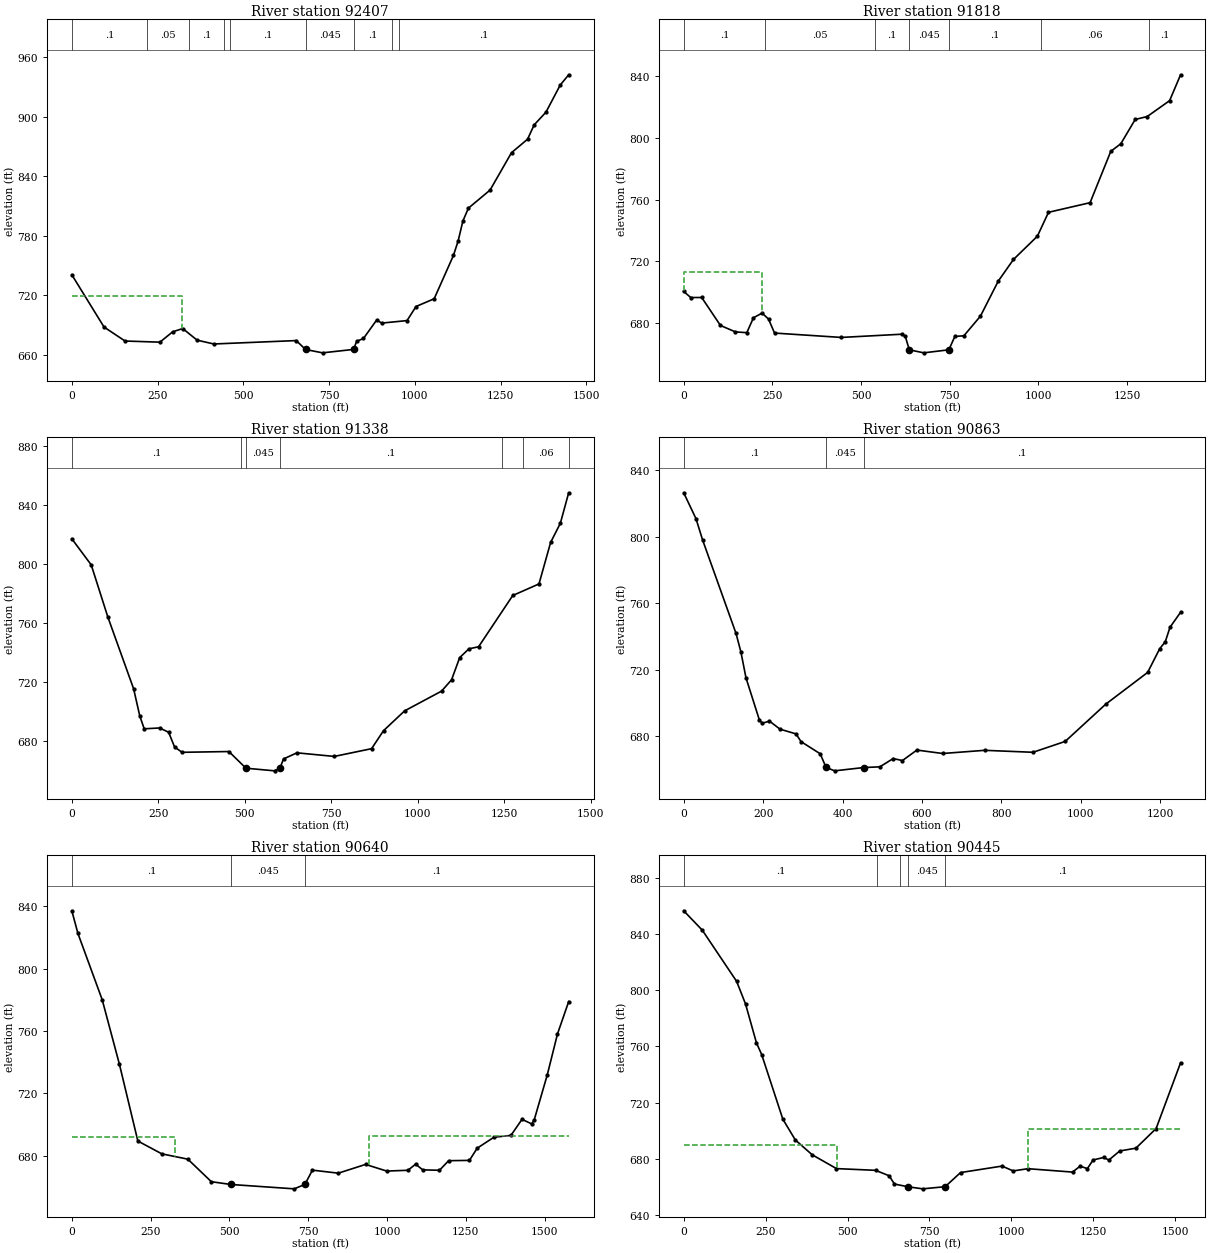
Type RM Length L Ch R = 1 ,92407   ,551.9,589.4,625.1
XS GIS Cut Line= 4
1615651.17124514395514.7901196461615445.26403064395775.729220078
1615081.98243292396268.8012253281614824.72592726396701.580910668
#Sta/Elev= 30
       0   740.5    93.9  687.82   155.1  673.73   256.8  672.58   293.9     683
   323.2  686.31   365.3  674.58   413.9  670.75   654.2  674.18   681.2  665.19
   730.9  661.82  821.17  665.27   830.2  673.38   850.1  676.33   888.8  694.99
   903.1   691.8   977.1  694.33  1003.3  708.53  1056.2  716.33  1112.4  760.03
    1126  774.57    1140  794.83  1156.1  807.72  1219.1  825.89  1281.6  863.59
  1328.3  877.13  1347.7  891.65    1382  904.42  1423.8  931.89  1448.3  942.12
#Mann= 9 ,-1,0
       0      .1       0     220     .05       0   342.4      .1       0
   442.4     .05       0   462.4      .1       0   681.2    .045       0
  821.17      .1       0   932.4     .07       0  954.84      .1       0
#XS Ineff= 2 , 0
          320.79     719
Permanent Ineff=
       F       F
Bank Sta=681.2,821.17
XS Rating Curve= 0 ,0
Exp/Cntr(USF)=0,0
Exp/Cntr=0.3,0.1

Type RM Length L Ch R = 1 ,91818   ,481.7,480.1,477.9
XS GIS Cut Line= 6
1615494.10910292395438.1769414251615403.42916617395480.546279252
1614954.35854201395637.7198494231614789.18301934395695.530429333
1614455.88316101 395812.185051681614175.30596626395910.385970756
#Sta/Elev= 30
       0   700.6    19.9  696.67    50.8  696.69   103.6   678.6     146  674.41
     178  673.93   196.8  683.59   221.1  686.59   239.2  682.74   256.2  673.67
   444.5  670.84   616.4  672.94   624.9  671.54   636.3  662.82   677.2  660.87
   747.8  662.83   764.7  671.48   790.2  671.91   836.8   684.6   887.1  707.28
     930  721.31   997.4  736.33  1028.8  751.83  1146.1  758.06  1204.5  791.29
  1232.8  796.21  1273.3  811.91  1307.2  813.83  1370.4   824.1  1401.3  840.85
#Mann= 7 ,-1,0
       0      .1       0  229.31     .05       0  538.37      .1       0
   636.3    .045       0   747.8      .1       0 1007.12     .06       0
 1311.65      .1       0
#XS Ineff= 2 , 0
          220.42  713.28
Permanent Ineff=
       F       F
Bank Sta=636.3,747.8
XS Rating Curve= 0 ,0
Exp/Cntr(USF)=0,0
Exp/Cntr=0.3,0.1

Type RM Length L Ch R = 1 ,91338   ,462.8,475.1,487.7
XS GIS Cut Line= 4
1615104.38279902 394885.300171981615011.17780151395094.571770163
1614385.12159182395347.807989812 1614007.0258472 395722.38656471
#Sta/Elev= 30
       0  817.34    56.1  799.63   104.3  764.14   178.7  715.53   196.5  697.09
   209.3   688.4     254  688.97   279.9  686.06   297.1  676.07   318.7  672.45
   454.1  672.98   503.5  661.67   586.2  659.88   601.7661.6953   612.1  667.95
   650.9   672.1   758.8  669.66   866.7  674.92   901.2  687.12   962.1  700.55
  1069.1  713.98    1098  721.66  1121.4  736.69    1148  742.66  1176.1  744.08
  1274.9  778.86  1350.7   786.7  1384.4  814.87  1412.6  827.92  1436.6  848.56
#Mann= 7 ,-1,0
       0      .1       0  489.09     .07       0   503.5    .045       0
   601.7      .1       0 1244.42     .05       0 1304.42     .06       0
 1436.65      .1       0
Bank Sta=503.5,601.7
XS Rating Curve= 0 ,0
Exp/Cntr(USF)=0,0
Exp/Cntr=0.3,0.1

Type RM Length L Ch R = 1 ,90863   ,154.9,222.6,307.4
XS GIS Cut Line= 4
1614857.44394951394724.1607519671614601.81760834394807.602651694
1613872.23039984394933.1858865571613672.97608133395070.393801487
#Sta/Elev= 30
       0   826.4    30.9  810.83    47.7  797.92   131.8  741.71   144.1  730.55
   156.8  715.05   190.7  689.54     198  687.68     216  688.97   242.4  684.13
   282.8  681.26   295.4  676.63   343.7   669.3  358.45  661.08   380.2  659.03
   453.3  661.02   493.9  661.43   527.4  666.42   550.7  665.22   587.2  671.53
   652.1  669.47   757.7  671.38   879.5   670.2   960.6  676.74  1062.8  699.18
  1168.2  718.27  1198.5  732.52  1212.6  736.72  1224.5  745.45  1251.1  754.46
#Mann= 3 ,-1,0
       0      .1       0  358.45    .045       0   453.3      .1       0
Bank Sta=358.45,453.3
XS Rating Curve= 0 ,0
Exp/Cntr(USF)=0,0
Exp/Cntr=0.3,0.1

Type RM Length L Ch R = 1 ,90640   ,235.8,195,138.1
XS GIS Cut Line= 3
1614863.65053141394711.547955183 1614597.5542305394799.108885707
1613338.10916885394491.568934329
#Sta/Elev= 30
       0  837.14    19.4  822.57    96.4  780.02   151.1  738.54   209.5  689.32
   285.7  681.07   368.1  677.67   442.7   663.2   504.9661.4194   705.7  658.62
  739.64  661.47   763.4  670.62   845.7  668.68   932.1   674.3   999.2  670.03
  1066.6  670.54  1090.9  674.48  1113.4   670.8  1166.6  670.54  1195.7  676.69
  1261.6  676.89  1286.3  684.72  1339.2  691.74  1393.3  692.93  1428.5  703.25
  1459.2   700.3  1467.5  703.11  1508.6  731.78    1541  758.04  1576.6  778.85
#Mann= 3 ,-1,0
       0      .1       0   504.9    .045       0  739.64      .1       0
#XS Ineff= 2 , 0
           328.2  691.72  941.96           692.3
Permanent Ineff=
       F       F
Bank Sta=504.9,739.64
XS Rating Curve= 0 ,0
Exp/Cntr(USF)=0,0
Exp/Cntr=0.3,0.1

Type RM Length L Ch R = 1 ,90445   ,285.8,268.1,257.7
XS GIS Cut Line= 3
1614876.64649523394634.1536037411614538.11199974394672.771728148
1613395.61309172394394.468315179
#Sta/Elev= 30
       0  856.68    56.9  842.81   161.6  806.38   188.8  790.24     222  762.61
   238.1  754.18   302.6   708.2   340.7  693.39   392.2  682.83   466.3  672.98
   585.7  671.75   626.9  667.88   643.3  661.99   685.2659.9952   729.8  658.56
     798660.0911   845.1  670.16   971.6  674.77  1005.6  671.34    1051  672.91
  1186.8   670.5  1209.9   674.7  1232.1  672.98  1249.7  679.14  1281.5  680.89
  1297.9  679.12  1330.9  685.53  1380.3  687.55    1442  701.54  1516.6  748.36
#Mann= 5 ,-1,0
       0      .1       0  590.73    .025       0  660.73      .1       0
   685.2    .045       0     798      .1       0
#XS Ineff= 2 , 0
          468.57  690.04 1051.08          701.31
Permanent Ineff=
       F       F
Bank Sta=685.2,798
XS Rating Curve= 0 ,0
Exp/Cntr(USF)=0,0
Exp/Cntr=0.3,0.1