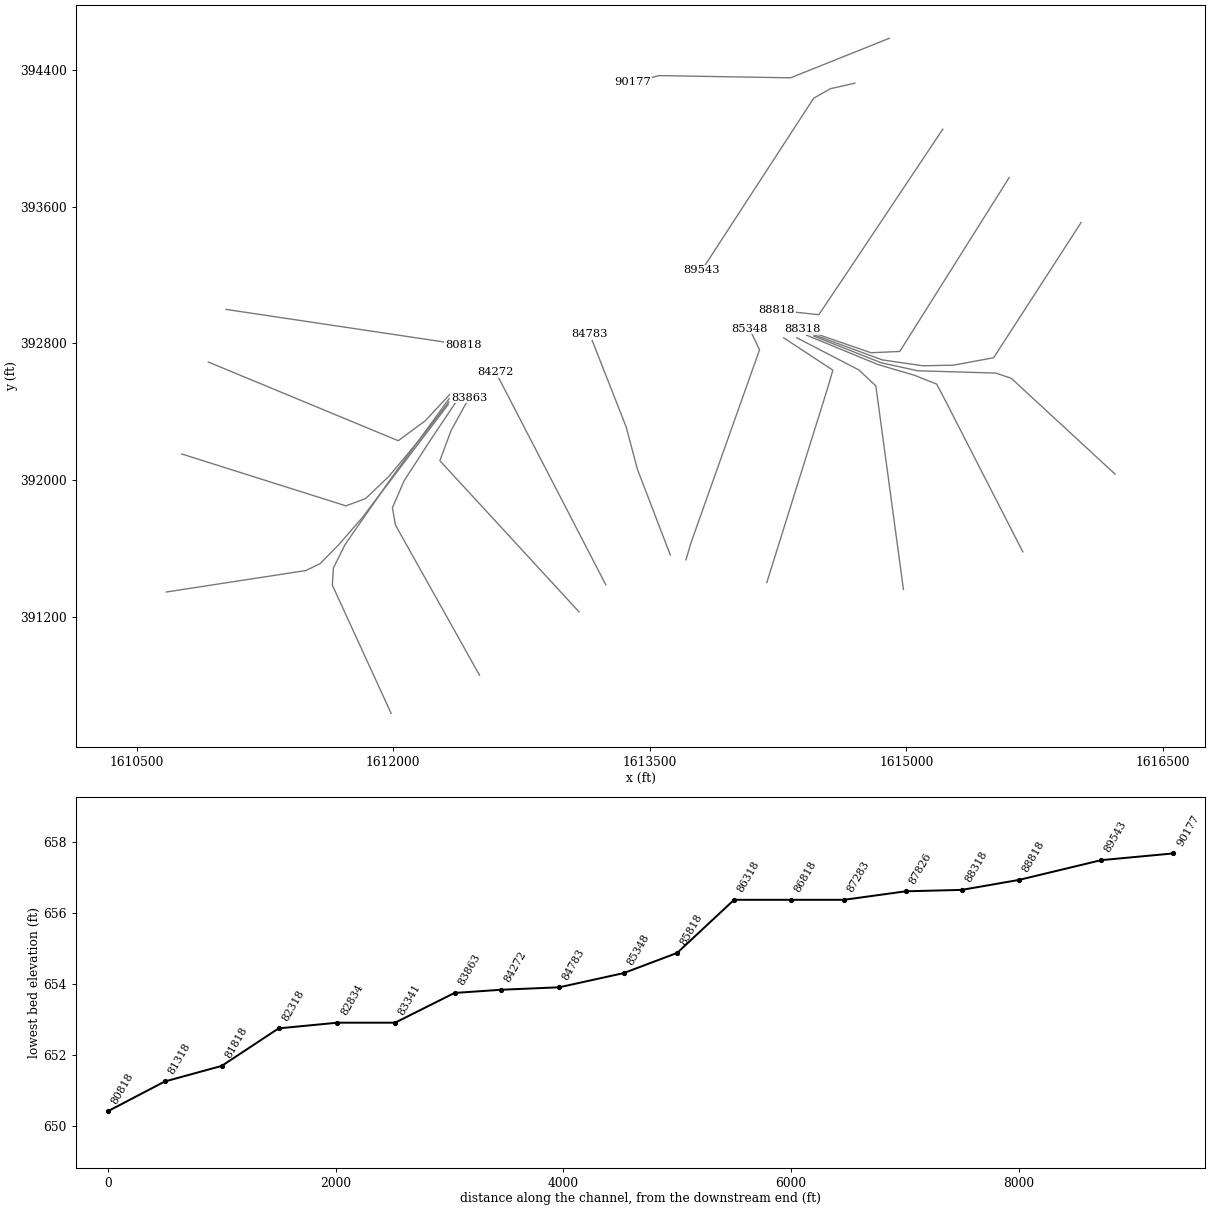
HEC-RAS study FISHINGCK.prj: FISHINGCK

--- FISHINGCK.g01 (geometry) --- (continued)

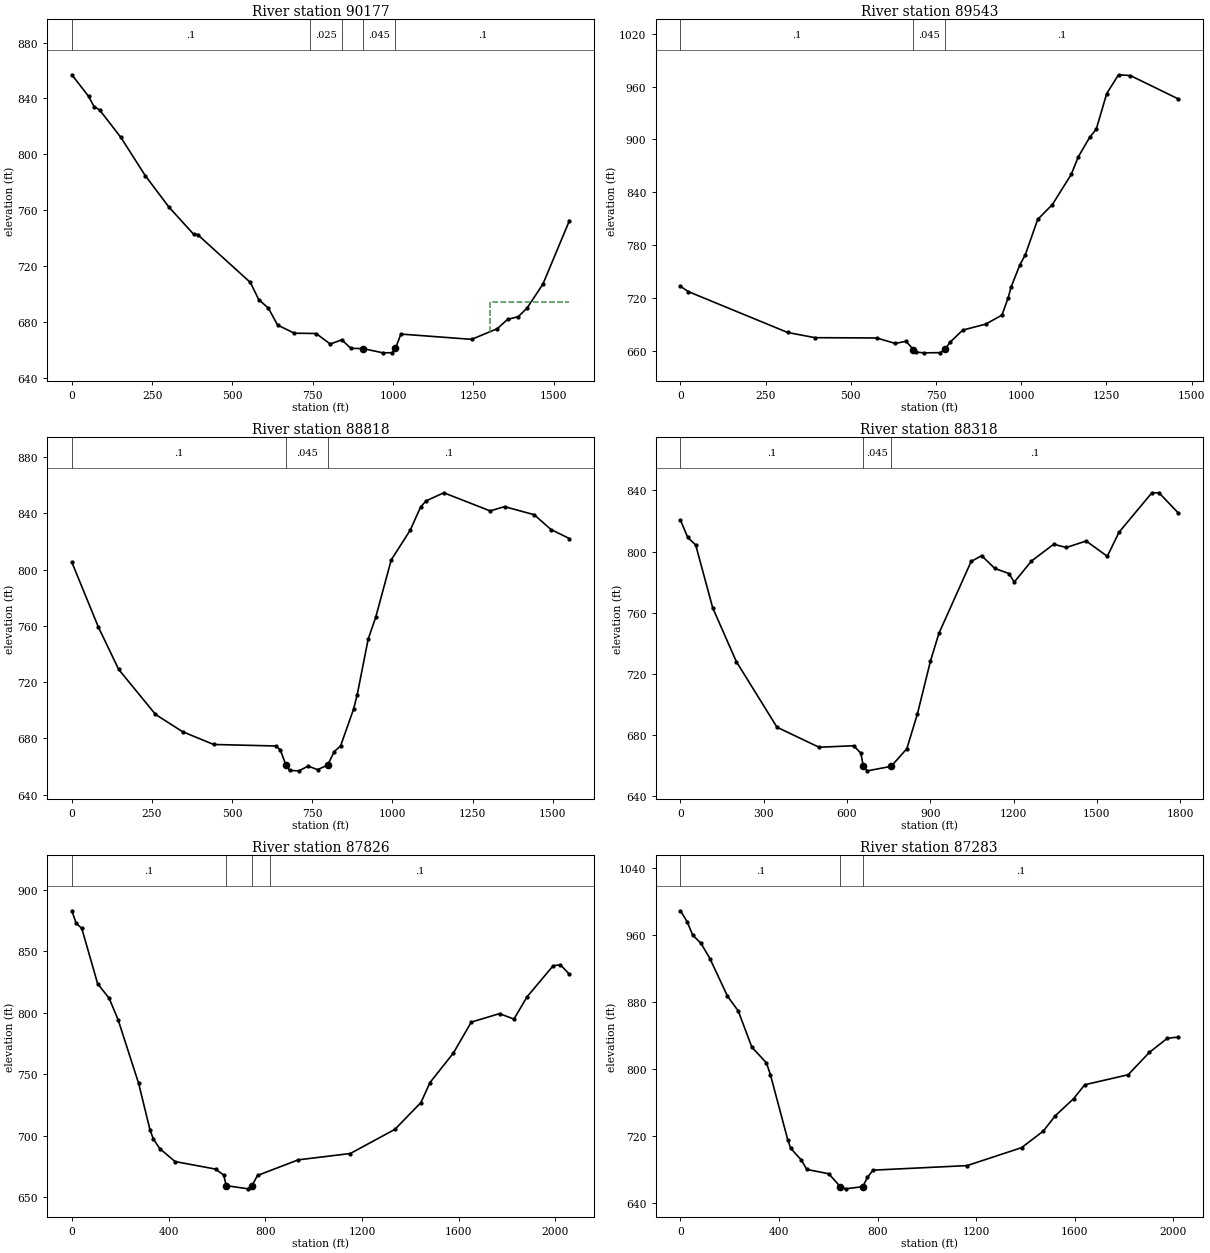
Type RM Length L Ch R = 1 ,90177   ,585.4,634.1,680.9
XS GIS Cut Line= 4
1614900.25187136394585.2898523941614323.71445602394354.240408697
   1613555.14774394367.2669632061613400.00242371394328.506851574
#Sta/Elev= 30
       0  856.88    51.9  841.51    69.1  834.08    86.3  831.72   152.6  812.02
   228.5  784.67   301.8  762.24   379.1  742.66   391.4  742.46     556  708.08
   581.9  695.86   612.1  689.69   640.7  677.59   692.7  671.77   760.7  671.53
   804.7     664   840.7  667.02   868.7  660.91   907.1660.7384   968.8  657.69
   996.8  657.78 1007.61  660.83  1024.8  671.13  1245.1  667.35  1324.8  674.99
  1356.8  681.62  1390.2   683.6  1417.7  689.78  1467.1  706.97  1549.7  752.47
#Mann= 5 ,-1,0
       0      .1       0  741.11    .025       0  841.11      .1       0
   907.1    .045       0 1007.61      .1       0
#XS Ineff= 2 , 0
                         1300.72          694.34
Permanent Ineff=
       F       F
Bank Sta=907.1,1007.61
XS Rating Curve= 0 ,0
Exp/Cntr(USF)=0,0
Exp/Cntr=0.3,0.1

Type RM Length L Ch R = 1 ,89543   ,724.7,725,723.3
XS GIS Cut Line= 6
1614698.75085837394322.7395819881614556.95192936394290.679278657
1614458.81465845394235.001896575 1613965.7713532 393476.47191757
1613912.12447887393393.9373057341613803.76544363393227.231274322
#Sta/Elev= 30
       0  733.07    23.2  727.08   314.5  680.63   394.9  674.73     576   674.4
   630.1  668.17   661.9  670.64  683.67  661.25   690.5  658.36   714.4   657.5
   762.3   657.7   776.4   661.3   790.7  669.45   828.3  683.34   895.7  690.13
   943.4   700.4   961.7  720.17   970.3  732.45   995.8  757.37  1011.8  768.87
  1048.3  809.18  1091.3  826.01  1146.7  860.33  1167.6  880.44    1201  902.54
  1220.1  911.69  1250.8  952.21  1285.5  973.54  1320.3  972.67  1460.2  946.21
#Mann= 3 ,-1,0
       0      .1       0  683.67    .045       0   776.4      .1       0
Bank Sta=683.67,776.4
XS Rating Curve= 0 ,0
Exp/Cntr(USF)=0,0
Exp/Cntr=0.3,0.1

Type RM Length L Ch R = 1 ,88818   ,498.4,500,501.5
XS GIS Cut Line= 6
1615213.46202642394053.634106845   1614654.68985393215.470756918
1614600.08300383393134.1831898391614544.55621201393051.504549429
1614488.62062834392968.3472354261614242.85668418392994.824872762
#Sta/Elev= 30
       0  805.18    82.5  759.23     146  729.05   260.9  697.05   345.2  684.77
   442.3  675.68   635.9  674.61   650.3  671.84  667.65661.1111   679.2  657.19
   708.5  656.94   736.9   660.3   766.8  657.78   797.9  661.07   818.6  670.65
   838.3  674.67   878.9  700.83   890.2  711.09   924.3  750.47   947.9   766.1
   996.4  806.93    1055  827.76    1088  844.45  1105.2  848.84  1160.3  854.56
  1304.9  841.67  1349.8  844.73  1442.4  838.95  1494.8  828.42  1552.3  822.02
#Mann= 3 ,-1,0
       0      .1       0  667.65    .045       0   797.9      .1       0
Bank Sta=667.65,797.9
XS Rating Curve= 0 ,0
Exp/Cntr(USF)=0,0
Exp/Cntr=0.3,0.1

Type RM Length L Ch R = 1 ,88318   ,494.3,491.9,490.7
XS GIS Cut Line= 6
1615601.84806067393770.9073100841615202.45647101 393135.63364625
1615014.50737184392836.6814882611614962.11410393392753.345368832
1614793.37625243 392745.796827511614395.23466025392883.549504757
#Sta/Elev= 30
       0  820.53    26.4  809.25    54.8  804.37   116.2  763.18   201.2  728.11
   347.7  685.18     499  672.09   623.8  673.08   649.6  668.26   658.6  659.64
   673.1  656.66   758.8  659.58   815.3  671.15   853.3  693.84   900.5  728.54
   930.9  746.58    1047  793.62  1084.8  797.34    1132  789.03  1183.2  785.68
    1202  780.06    1264  793.83  1344.1  804.81  1389.7  802.72  1461.1  806.96
  1537.3  796.96  1579.6  812.71  1697.9  838.48  1723.5  838.49  1792.2  825.42
#Mann= 3 ,-1,0
       0      .1       0   658.6    .045       0   758.8      .1       0
Bank Sta=658.6,758.8
XS Rating Curve= 0 ,0
Exp/Cntr(USF)=0,0
Exp/Cntr=0.3,0.1

Type RM Length L Ch R = 1 ,87826   ,625.2,543,454.6
XS GIS Cut Line= 6
 1616021.9157901393507.2300159191615510.85266508392716.682865992
 1615275.0016015392672.9905426651615095.45865351392669.552557424
1614860.04869126392703.9002577511614428.57055159392862.601383924
#Sta/Elev= 30
       0  882.86    17.8  872.71      41  868.56   106.7  823.47   154.3   811.7
   191.5  794.08   276.2  742.43   323.3  704.59   337.4  697.13   363.5   689.4
   426.9  678.82   594.3  672.69     628  667.87   638.9659.2123   729.4  656.62
  745.21  659.28     768  667.51   936.9  680.23  1151.9  685.36  1336.3     705
  1444.2  726.83  1481.6  743.09  1578.6  767.18  1652.3  792.26  1769.3  799.17
    1829  794.75  1882.9  812.78  1990.9  838.08  2020.8  838.98  2058.6  831.13
#Mann= 4 ,-1,0
       0      .1       0   638.9    .045       0  745.21    .025       0
  817.89      .1       0
Bank Sta=638.9,745.21
XS Rating Curve= 0 ,0
Exp/Cntr(USF)=0,0
Exp/Cntr=0.3,0.1

Type RM Length L Ch R = 1 ,87283   ,479.7,465.1,447
XS GIS Cut Line= 6
 1616220.3532069392035.9481739171615614.10573174392596.067788578
1615523.50191033392626.9420706551615066.64455633392640.152017987
1614853.65747197392687.0578710791614459.55961808392843.159360669
#Sta/Elev= 30
       0  989.25    27.6  975.87    49.3  960.31    83.4  950.27   119.5  932.08
   190.9  887.05   234.5  869.35   289.7  826.02   348.9  807.24   365.2  793.02
     436   714.6   447.8  704.86   490.5  690.89   512.9  679.62   602.1  674.44
   648.7659.0154   670.2  656.38  740.34  659.02   759.2  670.25   781.8  678.74
  1163.8   684.2    1385  705.68  1473.1  725.55  1521.7  743.84  1596.4  764.37
  1641.1  780.97  1817.5  792.96  1903.5  819.66  1976.6  836.61  2020.3  838.06
#Mann= 3 ,-1,0
       0      .1       0   648.7    .045       0  740.34      .1       0
Bank Sta=648.7,740.34
XS Rating Curve= 0 ,0
Exp/Cntr(USF)=0,0
Exp/Cntr=0.3,0.1

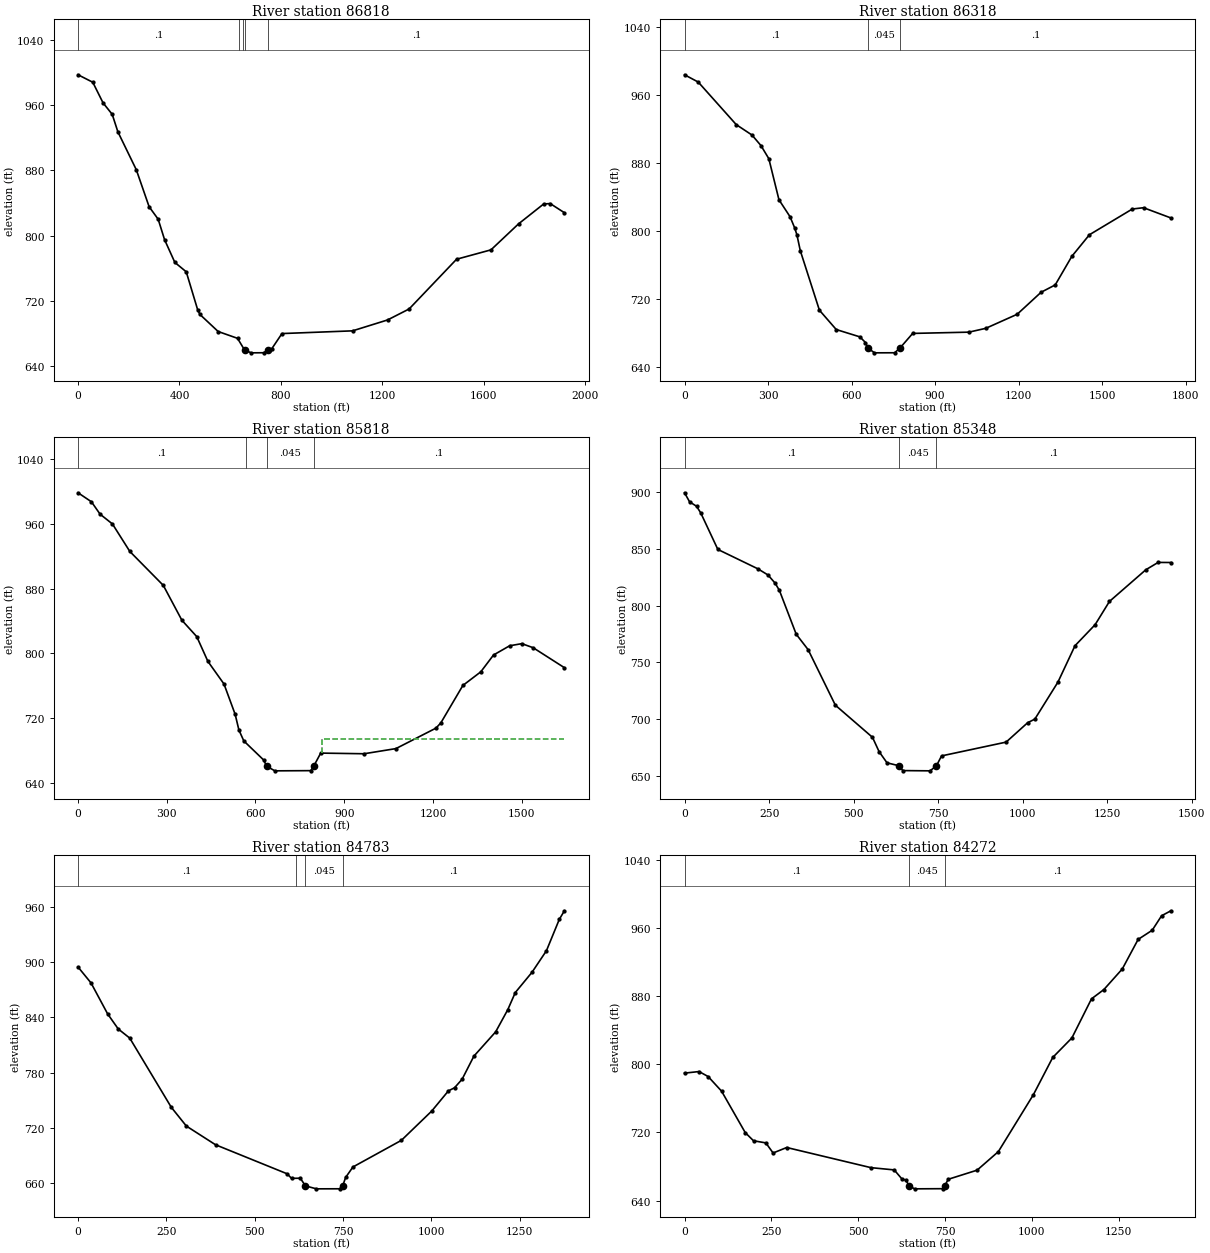
Type RM Length L Ch R = 1 ,86818   ,514.3,500,479.4
XS GIS Cut Line= 6
1615681.45190409391580.7712704241615222.94921218 392476.93023926
1615177.62843667 392562.560973511615046.77239917392614.337772846
  1614835.705236392676.2930295021614416.39898801392848.797605753
#Sta/Elev= 30
       0  996.86    58.1  987.71    98.6  962.44   134.7  948.43     157  927.05
   229.7  880.57   280.2  835.29   315.9  820.01   341.2  794.89   381.7  767.09
   426.6  755.61   471.5  709.23   480.5  703.39   552.4   682.5   628.8  674.15
  656.78659.7616   682.7  656.38   731.8  656.49   750.1  659.76   763.6  661.29
     804  679.98  1082.4  683.31  1220.3  696.64  1305.4   710.1  1492.4  770.99
  1628.1  782.48  1736.8   814.3  1835.8  838.65  1861.7  839.15  1917.6  827.96
#Mann= 5 ,-1,0
       0      .1       0  635.39    .025       0  650.39      .1       0
  656.78    .045       0   750.1      .1       0
Bank Sta=656.78,750.1
XS Rating Curve= 0 ,0
Exp/Cntr(USF)=0,0
Exp/Cntr=0.3,0.1

Type RM Length L Ch R = 1 ,86318   ,524.3,500,461.2
XS GIS Cut Line= 6
1614983.51366742391360.5512384181614906.30089533   391930.737434
1614861.01128776392265.1849278361614822.22101101392551.633173838
1614723.42987001392644.940401927  1614360.261305392833.121456012
#Sta/Elev= 30
       0  983.95    49.2  975.35   185.7  925.23   242.2  912.97   274.5  900.51
   302.7   885.1   339.1  836.71   378.9  816.74   395.6  803.51   403.6   795.4
   415.7  776.76   484.4   706.6   544.9  683.82   629.7   675.2   649.9  668.52
   657.9  662.26   682.2  656.38   754.8  656.47  774.87662.4708   819.4  679.26
  1021.2  680.75  1081.8  685.24  1194.8  701.83  1280.5  727.71  1331.4   736.4
  1391.1  770.09  1454.2  795.48  1608.3   825.8  1648.6  827.34  1746.9  815.28
#Mann= 3 ,-1,0
       0      .1       0   657.9    .045       0  774.87      .1       0
Bank Sta=657.9,774.87
XS Rating Curve= 0 ,0
Exp/Cntr(USF)=0,0
Exp/Cntr=0.3,0.1

Type RM Length L Ch R = 1 ,85818   ,472.7,470.1,473.4
XS GIS Cut Line= 6
1614184.77871634391401.3887551721614244.08371584 391591.16659084
1614408.60044718392117.6219027491614543.29013842392548.629242837
1614570.70806259392644.0119260851614283.90023726392832.657218084
#Sta/Elev= 30
       0  998.28    45.2  987.18    74.5  971.87   116.4  959.74   175.1  925.82
   288.3   883.9   351.1  840.87   401.4  820.62   439.1  790.03   493.5  762.11
   531.3   724.6   543.9  705.32   560.5  691.82   627.6  668.26   637.6  660.67
   665.4  654.88     787  655.12     797  660.71   820.5  676.79   967.2  675.98
  1074.8  682.34  1210.2  707.62  1226.8  714.15  1301.2  760.33  1361.8  777.16
  1404.8  797.92  1459.4  809.34  1500.6  811.95  1538.9  806.93  1644.5  782.27
#Mann= 4 ,-1,0
       0      .1       0  567.89    .025       0   637.6    .045       0
     797      .1       0
#XS Ineff= 2 , 0
                          826.46          694.69
Permanent Ineff=
       F       F
Bank Sta=637.6,797
XS Rating Curve= 0 ,0
Exp/Cntr(USF)=0,0
Exp/Cntr=0.3,0.1

Type RM Length L Ch R = 1 ,85348   ,528.2,565.3,593.3
XS GIS Cut Line= 6
1613712.11612513391534.3611561071613740.15871997391630.104731024
 1614043.4802918392484.9156854461614108.79446564392668.983886853
1614141.97451739392762.4902615251614083.55239014392886.704251946
#Sta/Elev= 30
       0  899.39    14.8  891.44    35.6  887.48    48.1  881.53    98.5  849.45
   216.9  832.37   246.7  826.96   267.9  819.74   280.6  813.32   330.3  774.71
   365.5  761.13   446.1  712.16   555.9  683.85   575.5  671.19   598.9  661.36
   634.6  658.77   645.6  654.53   726.3  654.31   745.2658.8395   760.2  667.48
   951.2  679.63  1014.9  696.74  1036.1  699.89  1104.4  732.48  1154.9  764.58
  1214.4  783.11  1256.8  803.61  1364.4  831.53  1400.8  838.01  1438.6  837.93
#Mann= 3 ,-1,0
       0      .1       0   634.6    .045       0   745.2      .1       0
Bank Sta=634.6,745.2
XS Rating Curve= 0 ,0
Exp/Cntr(USF)=0,0
Exp/Cntr=0.3,0.1

Type RM Length L Ch R = 1 ,84783   ,499.1,510.7,522
XS GIS Cut Line= 4
1613620.47325833391562.3081993221613428.41676965392063.232621844
1613363.02422155392309.9739577341613149.54144854392853.937141515
#Sta/Elev= 30
       0  894.71    36.7  877.46    83.8  843.78   113.8  827.44   146.3  817.54
   263.7  742.51   306.5  722.05   389.1  701.75   591.6  670.24     604   665.3
   628.9  665.45   643.4657.1276   674.4  653.91   740.6  653.97   748.9  657.22
   757.1  666.27   777.8  677.64   914.8  706.55  1000.8  738.39    1048   760.3
  1065.2  763.62  1086.7  772.92    1120  797.94  1181.7  824.39  1215.8  848.34
  1237.2  867.04  1284.4  888.98  1325.3  912.43  1361.7  946.47  1376.1  955.78
#Mann= 4 ,-1,0
       0      .1       0  616.48     .07       0   643.4    .045       0
   748.9      .1       0
Bank Sta=643.4,748.9
XS Rating Curve= 0 ,0
Exp/Cntr(USF)=0,0
Exp/Cntr=0.3,0.1

Type RM Length L Ch R = 1 ,84272   ,397.6,409.4,425.5
XS GIS Cut Line= 6
1613243.33930553 391388.165106041613106.76838445391652.201323372
1613019.19113178391821.5182419541612898.59196352392054.674927872
1612691.13371702392455.7604117961612599.78711494392632.363076952
#Sta/Elev= 30
       0  789.57    41.8  791.42      68  785.53   106.6  768.43   174.8   719.8
   198.6  710.22   234.2  707.73     255  695.89   294.3  702.32   536.9  678.69
   603.9  676.04     626  665.47   637.9  664.03   646.3  657.48   662.4  653.84
   743.5  654.02  749.39  657.51   759.5  665.05   842.6  675.74   903.8  697.48
  1004.7  764.25  1060.5  807.97  1115.7  830.88  1172.1   876.7  1207.7  887.56
  1260.8  911.75  1306.4  946.41  1346.9  957.13    1374  974.16  1400.8  979.99
#Mann= 3 ,-1,0
       0      .1       0   646.3    .045       0  749.39      .1       0
Bank Sta=646.3,749.39
XS Rating Curve= 0 ,0
Exp/Cntr(USF)=0,0
Exp/Cntr=0.3,0.1

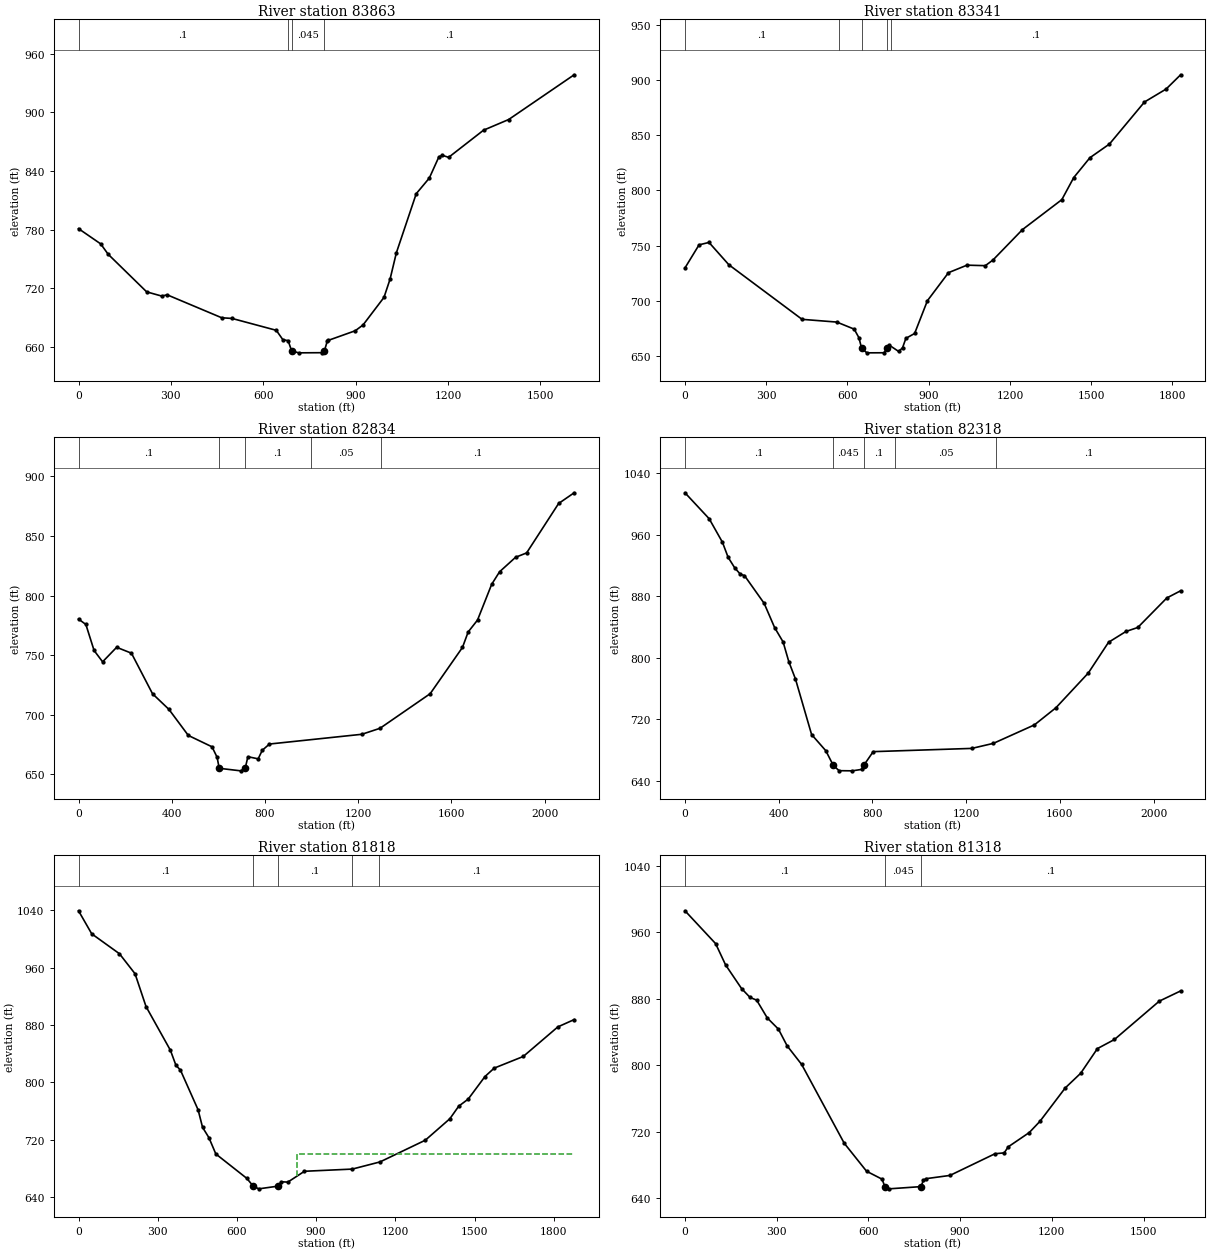
Type RM Length L Ch R = 1 ,83863   ,533.3,521.9,509.8
XS GIS Cut Line= 6
1613086.99894963391229.6360647711612885.73360414391448.403015676
1612578.94386338391781.8734773431612273.21153522392114.193022686
1612338.55490846392290.0312536841612444.44708513392483.055145848
#Sta/Elev= 30
       0  780.96      72  765.35    96.3  754.71   221.4  716.19   270.3  711.89
   287.8  713.19   465.1  689.67   498.6  688.98   642.3  676.82   663.7  667.19
   680.7  666.22     692  655.89   714.6  653.75     790   653.9  798.77     656
   807.7  665.53   810.9  666.49   898.7  676.36   924.1  682.32   992.1  710.56
  1011.9  729.35  1032.2  756.13  1096.8  816.74  1139.3  832.76  1170.4  854.49
  1181.7  856.06    1202  853.96  1315.4  881.79    1397  892.71  1609.7  938.54
#Mann= 4 ,-1,0
       0      .1       0  680.39    .025       0     692    .045       0
  798.77      .1       0
Bank Sta=692,798.77
XS Rating Curve= 0 ,0
Exp/Cntr(USF)=0,0
Exp/Cntr=0.3,0.1

Type RM Length L Ch R = 1 ,83341   ,511.7,506.7,503.3
XS GIS Cut Line= 6
1612504.91960039390859.1138492731612013.60004497391737.709533027
1611995.77166856391838.7332810971612064.42244989391996.920628777
1612216.62654181392232.520879349 1612365.9490778392455.425617269
#Sta/Elev= 30
       0  729.77      52  750.65    88.7  752.84     162  732.64   432.4  683.23
   560.8  680.75   624.9  674.36   642.4  666.61   652.4  657.02   671.8  652.91
   734.9  652.97  746.85  656.92   753.2  660.05   789.4  654.13   803.6  657.56
   815.8  666.02   848.1  670.43   895.3  700.07   973.2  725.48  1041.4  732.26
  1109.2  731.81  1137.4  736.92  1246.4  764.47  1391.7  791.55  1435.9  811.59
  1495.5  829.52  1567.6  841.89    1697  879.94  1776.8  891.65  1830.5  904.58
#Mann= 5 ,-1,0
       0      .1       0  567.89    .025       0   652.4    .045       0
  746.85    .025       0  760.39      .1       0
Bank Sta=652.4,746.85
XS Rating Curve= 0 ,0
Exp/Cntr(USF)=0,0
Exp/Cntr=0.3,0.1

Type RM Length L Ch R = 1 ,82834   ,631.4,515.9,411.6
XS GIS Cut Line= 6
1611988.40105938390635.7964559771611644.49886004391386.130585221
1611650.84760063391486.172707972 1611718.6119008391623.369940144
1611974.27379105391991.0460420671612327.00963413392476.667446149
#Sta/Elev= 30
       0  780.32    31.6  775.76    66.8  753.93   103.4  744.41   163.6   756.6
   227.1  751.66   317.6   717.6     388  704.49   471.1  682.63   572.8  673.08
   594.8  664.23  603.61  655.04     696  652.91   715.1655.0121   726.8  664.78
   770.8  662.98   788.4  670.14   819.2  675.41  1215.8  683.59  1293.6  688.62
  1508.9  717.66  1647.5  756.51  1671.9  769.49    1712  779.46  1772.8  809.48
  1806.6  819.98  1875.2  832.14  1922.7  835.83    2060  877.31  2126.7   886.3
#Mann= 5 ,-1,0
       0      .1       0  603.61    .045       0   715.1      .1       0
  995.63     .05       0 1298.75      .1       0
Bank Sta=603.61,715.1
XS Rating Curve= 0 ,0
Exp/Cntr(USF)=0,0
Exp/Cntr=0.3,0.1

Type RM Length L Ch R = 1 ,82318   ,526.8,500,472
XS GIS Cut Line= 6
1610674.03705017391345.9420156781611489.82970992391471.448326334
1611572.67173584391511.5886660071611678.68300676391618.834842592
1611816.53738984391777.193121672 1612322.9369676392444.053008422
#Sta/Elev= 30
       0 1014.49   103.3  980.72   159.9  950.14   184.2  930.51   212.5  916.73
   236.8  908.39   253.8  906.85     338  870.63   382.5  839.18   418.9  820.38
   443.2  794.78   471.6  772.22   540.4     700   601.1  678.93  633.01659.8219
   657.7  652.96   714.4  652.75   754.9  654.67   762.9  659.81   803.4  677.72
  1224.3  681.94  1316.4   688.5  1491.5  712.52  1583.3  734.81  1721.6  780.03
  1807.8  819.96  1882.1  834.03  1932.7  839.25  2056.7  877.66  2115.6     887
#Mann= 5 ,-1,0
       0      .1       0  633.01    .045       0   762.9      .1       0
  895.39     .05       0  1328.2      .1       0
Bank Sta=633.01,762.9
XS Rating Curve= 0 ,0
Exp/Cntr(USF)=0,0
Exp/Cntr=0.3,0.1

Type RM Length L Ch R = 1 ,81818   ,504.3,500,493.1
XS GIS Cut Line= 6
1610764.30885126392153.400374502  1611724.116971391849.930837095
1611839.25420792391892.741118923  1611974.388124392021.821569428
1612159.83361925392242.8686995061612325.77685693392458.496549085
#Sta/Elev= 30
       0 1039.03    50.1 1006.91     155   979.2   214.1  951.31   255.7  905.59
     348  844.73     369  823.72   385.8  817.25   452.9  761.75   469.7   737.4
   493.8     723     520  700.28   637.5  666.23  661.67655.4382   682.6  651.69
  754.95655.4144   767.5  661.51   792.7  661.07   855.6  676.16  1036.7   679.2
  1141.7  689.18  1313.2  719.42  1406.2  749.31    1440   766.9  1475.7  776.68
  1539.2  808.12  1574.2  819.85  1684.1  836.05  1815.2  877.28    1877  887.45
#Mann= 5 ,-1,0
       0      .1       0  661.67    .045       0  754.95      .1       0
 1036.64     .05       0 1139.48      .1       0
#XS Ineff= 2 , 0
                          826.23          700.83
Permanent Ineff=
       F       F
Bank Sta=661.67,754.95
XS Rating Curve= 0 ,0
Exp/Cntr(USF)=0,0
Exp/Cntr=0.3,0.1

Type RM Length L Ch R = 1 ,81318   ,488.3,500,514.5
XS GIS Cut Line= 6
1610919.53327835392691.4363719221611370.21774442392504.566010758
1611938.89574093392268.7708786731612029.82764567392231.070166677
1612187.55338009392347.4928340911612339.63673735392510.808780417
#Sta/Elev= 30
       0  985.65   100.2  946.16   132.9  920.51   185.1   892.1   212.8  881.45
   234.5  878.16   269.1  856.82   305.7   843.3   334.1  823.24   381.7  800.81
   520.9  706.08   593.9  672.43   644.6  662.88  653.78653.9251   667.5  651.25
  771.45653.9105   780.1  661.44   788.7  663.49   866.7  667.38  1013.9  693.44
  1044.2  694.52  1057.2  701.74  1126.1  718.94  1161.1  732.47  1243.8   772.6
  1294.3  790.25    1349   819.9  1404.8  830.86  1551.4  876.97  1621.2  889.26
#Mann= 3 ,-1,0
       0      .1       0  653.78    .045       0  771.45      .1       0
Bank Sta=653.78,771.45
XS Rating Curve= 0 ,0
Exp/Cntr(USF)=0,0
Exp/Cntr=0.3,0.1

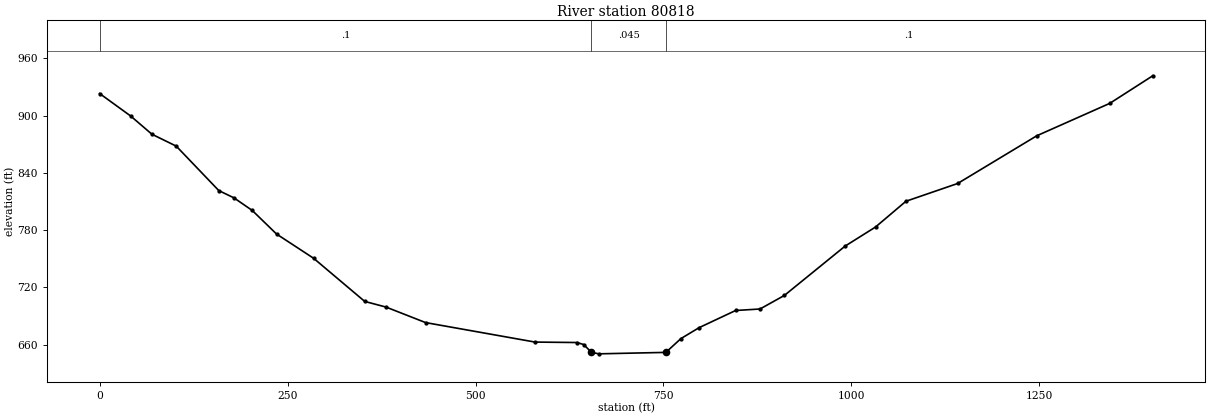
Type RM Length L Ch R = 1 ,80818   ,501.8,500,497.5
XS GIS Cut Line= 6
1611023.37854309392999.3320815861611220.01824167392969.913505256
1611666.61052434392903.0999905911611765.50993285392888.304088429
  1612018.939216392850.3891379981612408.74191409392792.072325513
#Sta/Elev= 30
       0  923.12    41.2  899.61    69.5   880.5   101.9  868.02   158.5  821.45
   178.7   813.8     203  800.62   235.3  775.94   284.6  750.53   352.6  705.33
   380.9  699.41   433.5  683.16   579.1  662.74   634.9  662.26   643.8  660.16
  654.18651.9934     664  650.41  753.14651.9317   773.2  666.39   797.5  677.89
     846  695.83   878.4  697.39   910.8  711.59   991.7  763.34  1032.1   783.3
  1072.5  810.26  1141.3  828.88  1246.5  878.85  1343.6  912.81  1400.8  941.72
#Mann= 3 ,-1,0
       0      .1       0  654.18    .045       0  753.14      .1       0
Bank Sta=654.18,753.14
XS Rating Curve= 0 ,0
Exp/Cntr(USF)=0,0
Exp/Cntr=0.3,0.1