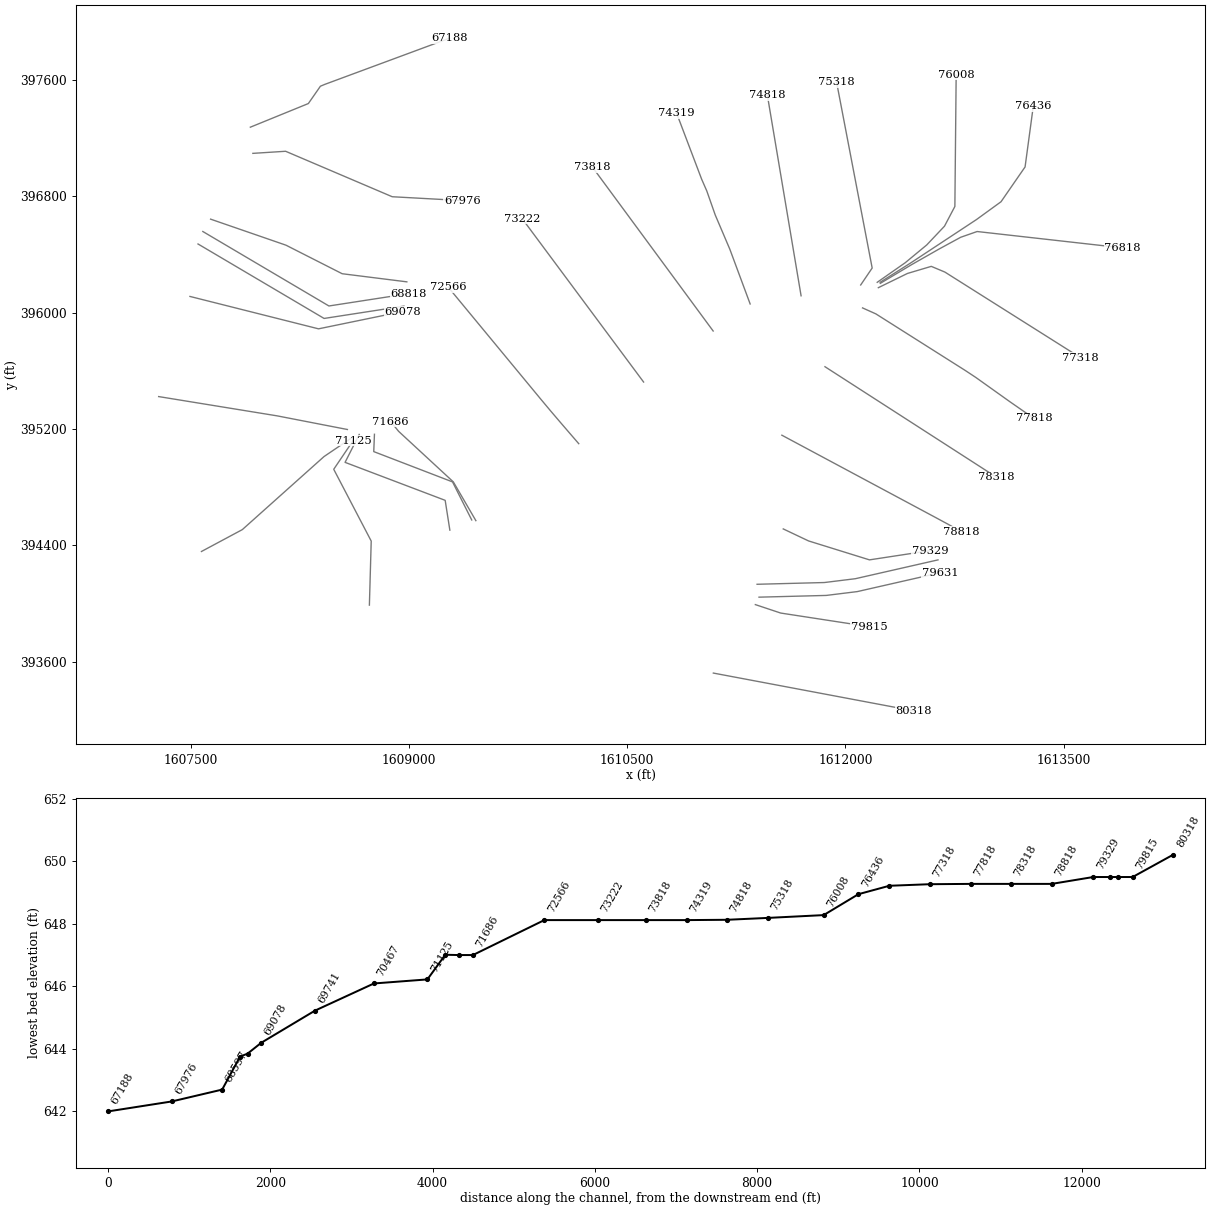
HEC-RAS study FISHINGCK.prj: FISHINGCK

--- FISHINGCK.g01 (geometry) --- (continued)

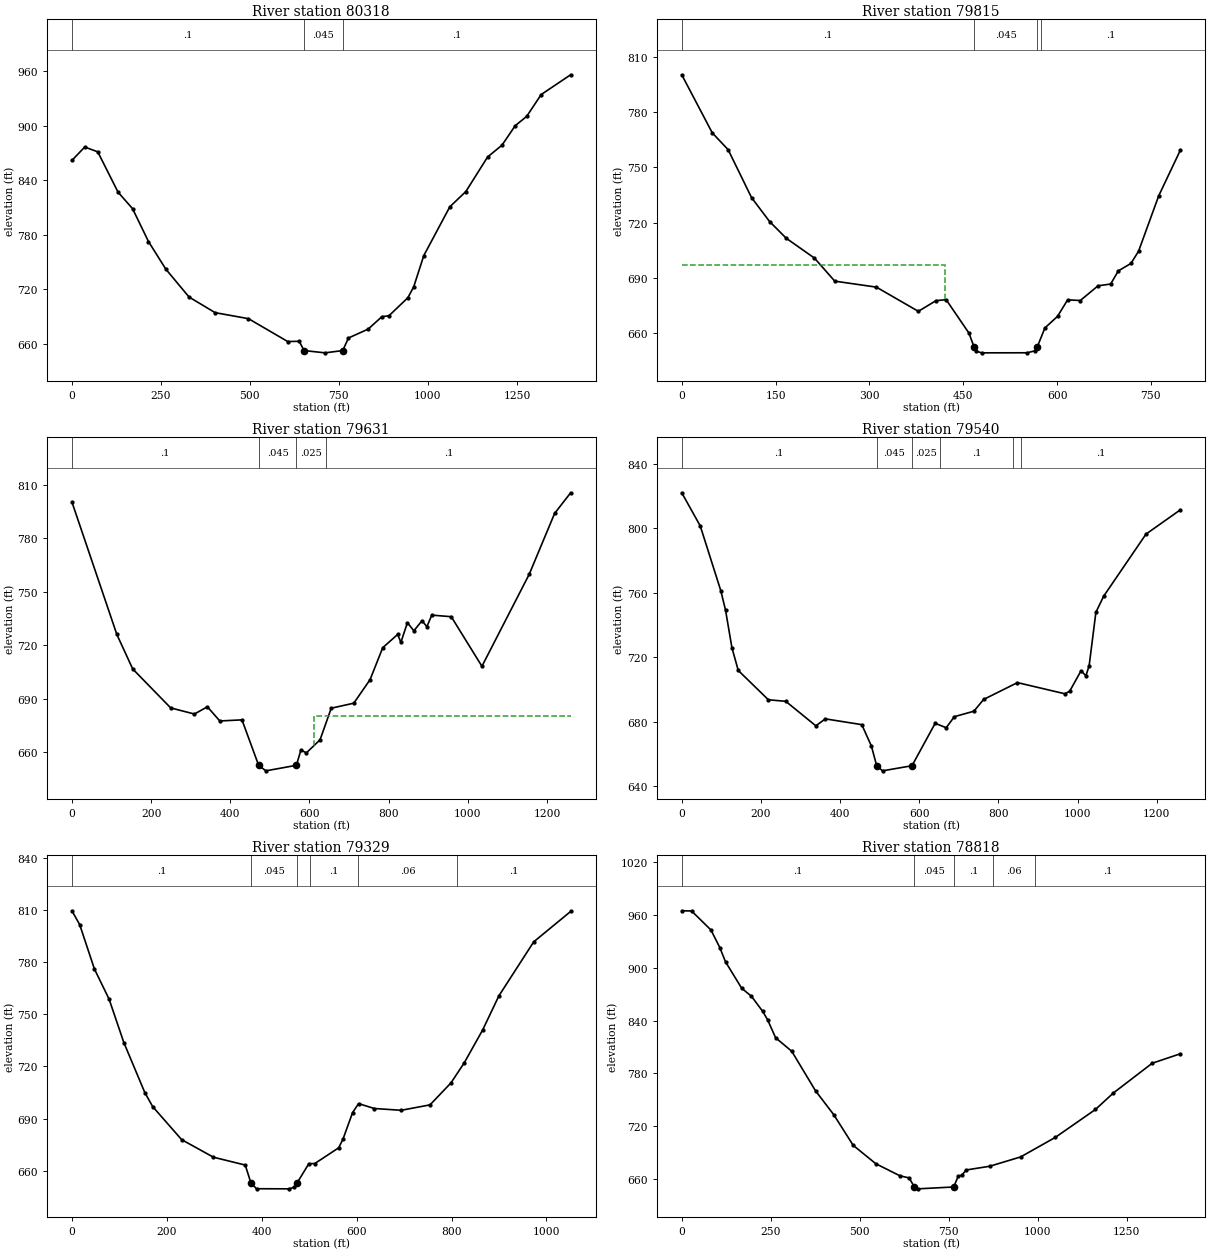
Type RM Length L Ch R = 1 ,80318   ,501.1,502.9,504.5
XS GIS Cut Line= 6
1611092.80261683393521.0577441751611288.18870901   393484.222516
1611658.23291643393414.4605164231612177.21580234 393316.61950475
1612273.94920467393298.3826645911612469.33562492 393261.54776451
#Sta/Elev= 30
       0  861.79    35.9  876.57    72.6  871.27   129.6  826.92   170.3  808.81
     215  772.66   263.9  742.19     329  711.59   402.3  694.41   495.9   687.8
     606  662.68   638.4  662.89  652.13652.7306   710.8  650.22  760.64652.7035
   776.8  666.55   832.1  676.33   870.4  689.88   890.7  691.08   943.6  710.83
   959.9   722.7   988.4  757.22  1061.5  810.84  1106.5  827.62  1167.5  865.58
  1208.2  878.69  1244.9  899.91  1277.4  910.31  1318.1  934.28  1400.8  956.02
#Mann= 3 ,-1,0
       0      .1       0  652.13    .045       0  760.64      .1       0
Bank Sta=652.13,760.64
XS Rating Curve= 0 ,0
Exp/Cntr(USF)=0,0
Exp/Cntr=0.3,0.1

Type RM Length L Ch R = 1 ,79815   ,170.6,183.7,196
XS GIS Cut Line= 3
1611381.63134238  393991.82783151611555.73124339393933.794531164
1612162.44301964393840.589533655
#Sta/Elev= 30
       0  800.12    48.8  768.65    74.1  759.57   111.6  733.57   140.5  720.59
   167.1  711.56   212.2   700.8   244.6  688.34   311.2  685.09   378.2  671.98
   406.5  677.77   422.7  678.29   459.1  660.21  467.16   652.8   471.2  650.39
   479.3   649.5   552.2  649.53   564.3  650.57   568.4  652.73   580.5  662.96
   600.7  669.24   616.9  678.21   637.2  677.85   665.5  685.81   685.7  686.77
   697.9  693.88   718.1  697.93   730.2  704.47   762.6  734.64   797.3  759.42
#Mann= 4 ,-1,0
       0      .1       0  467.16    .045       0   568.4     .08       0
  573.52      .1       0
#XS Ineff= 2 , 0
          420.17  696.95
Permanent Ineff=
       F       F
Bank Sta=467.16,568.4
XS Rating Curve= 0 ,0
Exp/Cntr(USF)=0,0
Exp/Cntr=0.3,0.1

Type RM Length L Ch R = 1 ,79631   ,91.5,91.4,90.4
XS GIS Cut Line= 4
1611406.61460283394043.0479221461611869.05542007394055.028254198
1612082.30533061394081.3849847151612650.17306991394210.772570885
#Sta/Elev= 30
       0  800.24   113.5  725.97   153.6  706.62   249.6  684.77   309.6  681.35
   342.2  685.42   373.6  677.46   429.6  678.08  471.63652.6498   489.9   649.5
  567.15652.6057   578.5  661.19   592.2  659.56   626.9  666.92   655.1  684.61
   712.1  687.44   753.2  700.62   785.2  718.54   822.9  725.96   831.1  721.54
   847.5  732.57   863.9  728.01   884.4  733.68   896.8  730.32   909.1  736.81
   958.3  735.92  1035.8  708.12  1155.2  759.68  1219.5  793.86  1259.9   805.4
#Mann= 4 ,-1,0
       0      .1       0  471.63    .045       0  567.15    .025       0
   642.6      .1       0
#XS Ineff= 2 , 0
                          611.43          680.16
Permanent Ineff=
       F       F
Bank Sta=471.63,567.15
XS Rating Curve= 0 ,0
Exp/Cntr(USF)=0,0
Exp/Cntr=0.3,0.1

Type RM Length L Ch R = 1 ,79540   ,231.4,210.7,193.2
XS GIS Cut Line= 4
1611393.43623757394131.7023793361611855.87705481394143.682711389
1612069.12696535394170.0394419051612636.99470465394299.427028075
#Sta/Elev= 30
       0  822.09    46.7  801.52    98.7  761.26   110.7  749.12   126.7  725.95
   142.7  711.81   218.8  693.62   262.8  692.64   338.7  677.45   362.8  681.76
   454.8  678.17     479  664.93  492.46652.6959   507.2   649.5  581.62 652.669
   640.2     679     668  676.25   688.7  683.13     738  686.51   762.6  693.82
   848.1  704.26   967.7  697.34     980  698.92  1008.7  711.61    1021  708.49
  1029.2  714.81  1046.2   747.9    1066  757.96  1172.8  796.44  1259.9  811.56
#Mann= 6 ,-1,0
       0      .1       0  492.46    .045       0  581.62    .025       0
   652.6      .1       0  837.47     .06       0  857.47      .1       0
Bank Sta=492.46,581.62
XS Rating Curve= 0 ,0
Exp/Cntr(USF)=0,0
Exp/Cntr=0.3,0.1

Type RM Length L Ch R = 1 ,79329   ,521,511.3,502
XS GIS Cut Line= 4
1611573.31709198394512.3689496681611747.41699299 394429.71546131
1612165.96018935394299.580181768  1612580.986216394362.889236681
#Sta/Elev= 30
       0  809.69    16.4  801.71    47.4  776.17    78.4  758.74   109.4  733.78
   153.6  704.97   170.1  696.91   231.2  677.84   298.2  667.72   365.2   663.2
  377.36  652.77   389.1  649.56   457.4   649.5     469  650.42   474.1  652.73
   499.2  663.99   511.8  664.08   562.1  673.13   571.3  678.22   591.4   693.4
     604   698.6   637.3  695.78   693.9  694.75   754.6  697.88   798.8  710.55
   826.9  722.19   865.5  741.03   899.8  760.73   973.1   791.8  1050.9  809.29
#Mann= 6 ,-1,0
       0      .1       0  377.36    .045       0   474.1    .025       0
  502.72      .1       0  602.72     .06       0  811.03      .1       0
Bank Sta=377.36,474.1
XS Rating Curve= 0 ,0
Exp/Cntr(USF)=0,0
Exp/Cntr=0.3,0.1

Type RM Length L Ch R = 1 ,78818   ,504,500,496.3
XS GIS Cut Line= 6
1611563.73671433395156.9452204261612291.30021983 394767.17500259
1612451.06860109394681.5849506711612623.23229876394589.353507832
1612710.53100868394542.2000588331612797.50196335394493.608620584
#Sta/Elev= 30
       0  964.38    27.7  964.15    82.1  942.56     107  922.58   122.9  906.54
   168.3  876.61   195.6  867.56   227.3  850.41   240.9  841.03   263.6  820.51
     309  805.14   375.8  760.31     427  733.27   481.4  698.63     545  677.76
     613  664.02   638.8  661.65  653.19651.4747     663  649.28  763.91651.3848
   776.4  663.54   786.6  664.83   799.1  670.67   864.9  674.87     952  685.46
  1049.6  707.67  1162.1  739.26  1212.1  757.82  1321.3   791.6  1400.8  802.39
#Mann= 5 ,-1,0
       0      .1       0  653.19    .045       0  763.91      .1       0
  875.39     .06       0  992.89      .1       0
Bank Sta=653.19,763.91
XS Rating Curve= 0 ,0
Exp/Cntr(USF)=0,0
Exp/Cntr=0.3,0.1

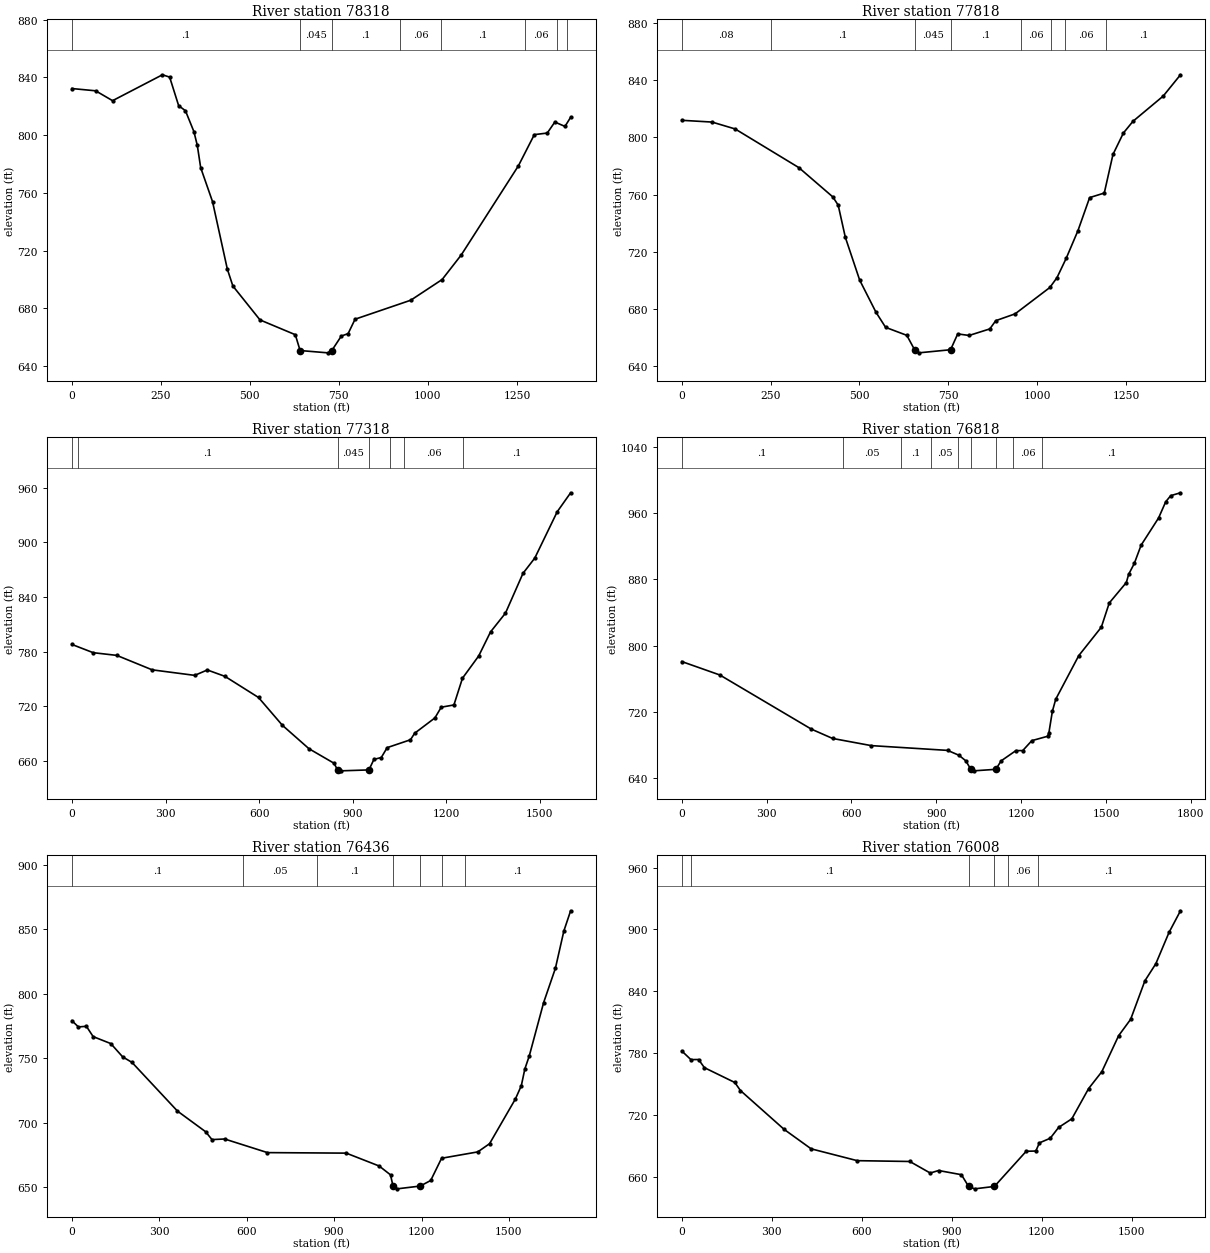
Type RM Length L Ch R = 1 ,78318   ,499.7,500,501.1
XS GIS Cut Line= 6
1611860.10816884395627.9364044221611943.82847384395573.964727595
1612270.17296551395363.5799777511612343.71546935395316.169639513
1612787.59614326395030.0127315071613037.44341259394868.943827927
#Sta/Elev= 30
       0  832.32    66.6  830.75   114.2  823.91   254.2  841.85   274.5  840.24
   299.8  820.46   318.9  816.94   342.7  802.45   352.2  792.92   361.7   777.5
     395  753.97   436.5  707.29   452.1  695.56   528.3  672.08   627.5  661.83
   640.9650.8757   718.6  649.28  730.02 650.884   756.7   660.9   775.8   662.6
   795.3  672.57   951.8  685.73  1039.8  700.04  1093.4  717.01  1253.9  778.72
  1298.8   800.4  1335.1  801.49  1356.4  809.11  1384.9  806.09  1400.8  812.41
#Mann= 8 ,-1,0
       0      .1       0   640.9    .045       0  730.02      .1       0
  922.89     .06       0 1036.64      .1       0 1271.95     .06       0
 1361.17      .1       0 1391.17     .06       0
Bank Sta=640.9,730.02
XS Rating Curve= 0 ,0
Exp/Cntr(USF)=0,0
Exp/Cntr=0.3,0.1

Type RM Length L Ch R = 1 ,77818   ,499.7,500,499.7
XS GIS Cut Line= 6
1612118.40063126396032.3155169191612210.18522459395991.070848763
1612823.33885393395602.7399325071612896.36626692395554.510698259
1613132.09676659395386.4073599281613296.16599226395272.583112508
#Sta/Elev= 30
       0  811.96    85.2  810.73   150.2  805.91   329.6  778.83   424.9  758.39
   440.1  752.62   460.2   730.1   500.6  700.13   546.4  677.69   573.5  667.11
   633.2  661.52  654.97651.4676   666.8  649.28   756.3  651.45   776.4  662.52
   808.4  661.44   866.7  666.02   883.4  671.78     938  676.57  1035.6     695
  1055.6  701.84  1081.6  715.42  1114.7  734.79  1147.5  757.88  1188.7  761.07
  1213.2  788.09  1242.5  803.07  1269.5  811.27  1354.5  828.91  1403.1  843.81
#Mann= 8 ,-1,0
       0     .08       0  249.84      .1       0  654.97    .045       0
   756.3      .1       0  953.92     .06       0 1037.77      .1       0
 1077.77     .06       0 1194.81      .1       0
Bank Sta=654.97,756.3
XS Rating Curve= 0 ,0
Exp/Cntr(USF)=0,0
Exp/Cntr=0.3,0.1

Type RM Length L Ch R = 1 ,77318   ,480.2,500,522.3
XS GIS Cut Line= 6
1612226.95028292396171.4851860851612427.28419983396269.410515174
1612590.72120893396318.0386987631612684.20035267396278.872438505
1612982.76340385396090.306214586 1613617.2099696395689.602291584
#Sta/Elev= 30
       0  788.05    68.1  779.01   143.8  776.04   257.2  760.17   393.5   754.1
     434  760.03   490.4  753.02     598  729.82   674.5   699.3   759.7  673.58
   840.1   657.6   851.3  650.31   861.8  649.27  951.89650.2803   967.9   661.8
   991.5  663.91  1010.4  674.75  1085.1  683.39  1098.5  690.55  1163.4  707.38
  1183.7  719.14  1224.3  721.62  1251.7  750.97  1303.8  775.44  1341.6  801.77
  1389.6  822.47  1445.7  866.13  1483.5  882.87  1555.4  933.76  1598.4  954.58
#Mann= 7 ,-1,0
       0     .08       0      20      .1       0   851.3    .045       0
  951.89    .025       0 1017.98      .1       0 1062.98     .06       0
 1254.23      .1       0
Bank Sta=851.3,951.89
XS Rating Curve= 0 ,0
Exp/Cntr(USF)=0,0
Exp/Cntr=0.3,0.1

Type RM Length L Ch R = 1 ,76818   ,331.8,381.9,430
XS GIS Cut Line= 6
1612240.57853651396201.4109792561612454.54070701396329.262101501
1612645.23422326396437.7412152591612793.22605325396518.277799591
1612906.00338675396557.6845449211613906.33340709396445.144743755
#Sta/Elev= 30
       0  780.91   134.6  764.72   458.1  699.49   533.1  688.26   669.8  679.62
   939.9  673.86   980.1  667.98  1004.3  661.25 1022.06651.0145  1032.4  649.22
  1110.5  651.05    1129  661.19  1181.4  673.59  1205.5  673.61  1237.7  685.61
  1294.1  690.93  1298.1  695.26  1310.2  720.85  1322.2  735.52  1403.6  788.04
  1483.3  822.27  1511.4  851.48  1571.8  876.14  1579.9  885.94    1600  899.17
  1624.1  921.18  1685.8  953.92  1711.1   973.5  1728.8   980.8  1763.2  984.26
#Mann= 9 ,-1,0
       0      .1       0  568.64     .05       0  776.59      .1       0
  880.34     .05       0  977.84    .025       0 1022.06    .045       0
  1110.5      .1       0 1172.84     .06       0 1275.34      .1       0
Bank Sta=1022.06,1110.5
XS Rating Curve= 0 ,0
Exp/Cntr(USF)=0,0
Exp/Cntr=0.3,0.1

Type RM Length L Ch R = 1 ,76436   ,398.1,428.2,452.5
XS GIS Cut Line= 6
1612239.49159643396208.5930515081612452.36715493396343.626246005
1612901.33705124396639.8351237711613070.28191951396762.560294955
1613235.51855283397001.8685225231613292.08126965397420.368278392
#Sta/Elev= 30
       0  779.21    22.3  774.37    49.7  774.87    72.9  766.87   133.4  761.48
   174.3  751.16   206.2   746.9   362.4  709.16   458.9   693.2   480.8   687.1
   524.2  687.56   671.3  677.01   941.7  676.61  1054.7  666.63  1093.6  659.78
  1102.2  651.08  1116.5  648.95  1195.6  651.11  1231.6  655.43  1268.9  672.64
  1393.2  677.57  1433.6  683.92  1522.4   718.6  1542.6  728.85  1554.7   741.8
  1569.9   751.9  1619.2  793.23  1659.6   819.8  1688.7  848.77  1711.9  864.35
#Mann= 7 ,-1,0
       0      .1       0   587.1     .05       0  839.98      .1       0
  1102.2    .045       0  1195.6      .1       0 1268.79     .07       0
  1349.6      .1       0
Bank Sta=1102.2,1195.6
XS Rating Curve= 0 ,0
Exp/Cntr(USF)=0,0
Exp/Cntr=0.3,0.1

Type RM Length L Ch R = 1 ,76008   ,681,689.9,700.2
XS GIS Cut Line= 6
1612219.19439292396208.3423958421612411.77274792396343.124934673
1612559.69830509396465.4675377611612681.71779493396594.577368801
1612752.96902493396730.1055945941612761.83493876 397634.69282639
#Sta/Elev= 30
       0  782.11    30.4   773.7    56.1  773.78    75.5  765.87   176.9  751.48
   195.7  743.65   341.4  705.95   431.2  687.11   584.9  675.62   760.2  674.83
   828.2  663.62   856.2  666.06   932.2     662   956.2  650.59   976.2  648.28
 1042.18  650.61  1148.2  684.76  1180.2  684.96  1192.2  692.89  1228.2  697.36
  1256.2  707.87  1300.2  716.23  1356.2  745.59  1400.2  761.95  1456.2  796.89
  1496.3  812.81  1543.8  850.18  1580.3  866.77  1624.3  897.17  1662.4  918.13
#Mann= 6 ,-1,0
       0     .08       0      30      .1       0   956.2    .045       0
 1042.18      .1       0 1087.78     .06       0 1186.36      .1       0
Bank Sta=956.2,1042.18
XS Rating Curve= 0 ,0
Exp/Cntr(USF)=0,0
Exp/Cntr=0.3,0.1

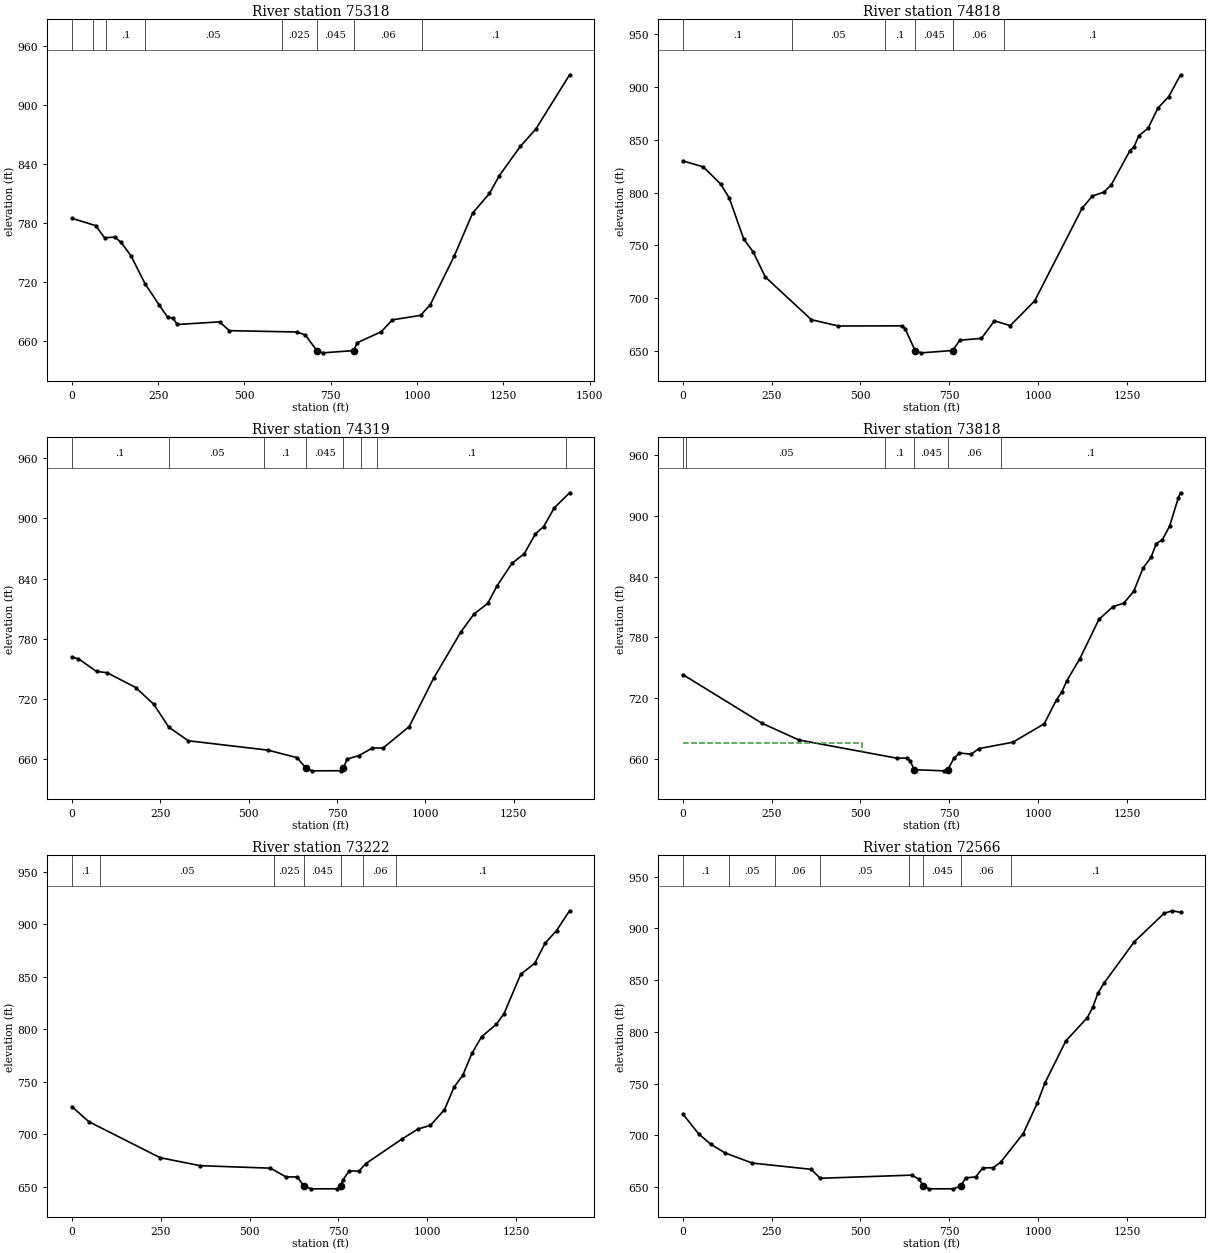
Type RM Length L Ch R = 1 ,75318   ,501.2,500,498.8
XS GIS Cut Line= 6
1612105.57388526396190.0904638321612184.53206067396306.621070668
1612111.53778408396687.9795599281612031.64030609397105.401625335
1611977.29855126397389.3105063441611939.92001709397584.593580335
#Sta/Elev= 30
       0  785.06    68.7  777.67    94.8  765.24   124.6  765.94   142.7  760.55
   171.2  746.98   211.9  718.59   252.7  696.93   277.1  684.65   293.4  683.15
   305.6  677.05   427.8  679.69   456.3  670.75   651.8  669.41   676.2  666.36
  709.81650.4473   727.3  648.19   816.2  650.47   826.9  658.51   896.1  669.65
   928.7  681.77  1010.2  686.31  1038.4  697.25  1107.9  746.82  1160.9  790.31
  1209.7  810.33  1238.2  828.39  1299.3   858.3  1344.1  875.91  1441.9   931.1
#Mann= 8 ,-1,0
       0      .1       0      60     .08       0     100      .1       0
  210.76     .05       0  609.04    .025       0  709.81    .045       0
   816.2     .06       0 1014.04      .1       0
Bank Sta=709.81,816.2
XS Rating Curve= 0 ,0
Exp/Cntr(USF)=0,0
Exp/Cntr=0.3,0.1

Type RM Length L Ch R = 1 ,74818   ,491.4,499.5,509.7
XS GIS Cut Line= 6
1611695.90508518396115.6627911781611630.59222367 396504.35427101
1611588.12872593396757.0614427631611544.62979718397015.932316095
1611513.04160576  397203.92176951611463.78153367397497.077679262
#Sta/Elev= 30
       0  830.09    57.7  824.36   106.3  808.21   130.7  794.89   171.2  756.26
   198.8   743.3   232.1  720.05   361.9  679.53   438.1  673.57   617.4   673.7
   625.4  671.19  653.65 650.345   670.8  648.13   759.4  650.32   779.7  660.13
   840.5  661.84     877  678.44   921.6  673.91   990.3  697.39  1124.4  785.48
  1152.8  796.71  1184.7  800.39  1205.6  807.19  1258.3  839.69  1270.4  843.58
  1282.6  853.56  1309.7  861.09  1337.1  880.05  1367.8  891.04  1400.8  911.65
#Mann= 7 ,-1,0
       0      .1       0  307.27     .05       0  567.89      .1       0
  653.65    .045       0   759.4      .1       0  760.39     .06       0
  905.39      .1       0
Bank Sta=653.65,759.4
XS Rating Curve= 0 ,0
Exp/Cntr(USF)=0,0
Exp/Cntr=0.3,0.1

Type RM Length L Ch R = 1 ,74319   ,487.2,500.5,517.8
XS GIS Cut Line= 6
1611345.78078543396059.4631004181611206.36702226396435.339973345
1611105.70777476396671.6869415941611047.71248393396836.800784588
 1611012.6088796396916.9072516711610839.62825443397373.171102926
#Sta/Elev= 30
       0  761.48    18.3  759.98    69.7   747.3    99.7  746.04   180.7  731.25
   231.7  714.51     274  691.84   329.3  678.13   554.7  668.77   637.1  661.29
     663   650.6     680  648.12   760.6  648.23  767.87650.5711   778.8  659.88
   811.4  663.23   850.5   670.9   880.6  670.93   954.5  692.31  1023.2  740.29
  1100.3  786.52  1137.5  804.48  1176.6  815.15  1202.2  832.22    1245  855.07
  1280.2   864.9  1311.2  884.44  1334.8  891.81  1364.8  910.47  1408.2  925.55
#Mann= 8 ,-1,0
       0      .1       0  273.73     .05       0  544.96      .1       0
     663    .045       0  767.87      .1       0  817.83     .06       0
  862.83      .1       0 1398.68     .08       0
Bank Sta=663,767.87
XS Rating Curve= 0 ,0
Exp/Cntr(USF)=0,0
Exp/Cntr=0.3,0.1

Type RM Length L Ch R = 1 ,73818   ,595.9,596.1,596.5
XS GIS Cut Line= 6
1611091.55688442395873.4375538381610750.42928584 396336.80178459
1610705.96480784396397.1996296791610494.75755309396684.089147761
1610437.32394092396762.102771252 1610261.0864325397001.492056251
#Sta/Elev= 30
       0   743.3   222.4  695.24   326.7  678.62   602.6  660.63   631.2  660.74
   639.8  657.93  651.25649.2761     734  648.12   745.6  649.25   762.8  660.47
   778.7  665.79   811.5  664.56   833.3  670.08   928.7  676.38  1017.1   694.6
  1051.9  718.45  1066.1  725.67  1080.4  736.94  1117.6  759.08  1171.1  797.81
  1210.8  810.47  1241.1   813.8  1269.2  825.66  1295.3  848.51  1317.8  859.19
  1332.1  872.44  1349.9  876.78  1369.8  889.74  1394.6  917.95  1400.8  922.98
#Mann= 6 ,-1,0
       0      .1       0      10     .05       0  567.89      .1       0
  651.25    .045       0   745.6     .06       0  895.39      .1       0
#XS Ineff= 2 , 0
          504.83   675.9
Permanent Ineff=
       F       F
Bank Sta=651.25,745.6
XS Rating Curve= 0 ,0
Exp/Cntr(USF)=0,0
Exp/Cntr=0.3,0.1

Type RM Length L Ch R = 1 ,73222   ,653.9,655.9,659.2
XS GIS Cut Line= 6
 1610613.3127682395522.5860578941610270.26522595395984.530672051
1610121.21565528396185.2399163021609896.70921454396487.557881213
1609837.55513337396567.2145460471609778.16811304396647.184530474
#Sta/Elev= 30
       0  726.46    47.3  712.18   248.1  677.82   361.2  670.17   558.9  667.81
   602.7  659.43   634.1  659.47   652.8  650.96   672.9  648.12   746.7  648.17
  756.42  650.97   762.8  656.53   779.9  664.91   808.5  665.22   827.2  672.15
   929.1  695.56   974.3  705.12  1008.9  708.52  1048.7  723.48  1075.5  744.92
  1100.2  756.26  1125.9  777.19  1153.3  793.09  1194.5  804.76  1216.4  815.08
  1263.3  852.49  1302.8  862.94  1331.7  881.97    1364  894.07  1400.8  912.93
#Mann= 7 ,-1,0
       0      .1       0      80     .05       0  567.89    .025       0
   652.8    .045       0  756.42     .07       0  820.39     .06       0
  912.89      .1       0
Bank Sta=652.8,756.42
XS Rating Curve= 0 ,0
Exp/Cntr(USF)=0,0
Exp/Cntr=0.3,0.1

Type RM Length L Ch R = 1 ,72566   ,874.6,880,887.4
XS GIS Cut Line= 6
1610167.57860487395098.6933786361610102.47604478395174.114487642
 1610037.7947437395249.3764762221609973.95497637395324.320880138
1609911.79958887395398.6301147281609270.68866637396174.711239719
#Sta/Elev= 30
       0  720.62    44.7  701.29    78.8  691.23   118.6  682.92   195.3  673.05
   361.3     667   386.8  658.34   645.4   661.4   665.2  657.23   676.9650.9919
   692.4  648.12   761.8  648.16  783.03     651   795.9  658.77   824.4  659.64
   844.2  668.32     874  668.58   894.7  674.01   957.9  701.49   997.7  731.06
  1019.3  750.69  1078.3  791.37  1138.6  813.76  1153.7  823.78  1168.1  837.12
  1185.2  847.04  1270.4  887.03  1354.6  914.65  1377.3  917.12  1400.8  915.61
#Mann= 8 ,-1,0
       0      .1       0  129.63     .05       0  258.87     .06       0
  387.32     .05       0  635.45      .1       0   676.9    .045       0
  783.03     .06       0  922.95      .1       0
Bank Sta=676.9,783.03
XS Rating Curve= 0 ,0
Exp/Cntr(USF)=0,0
Exp/Cntr=0.3,0.1

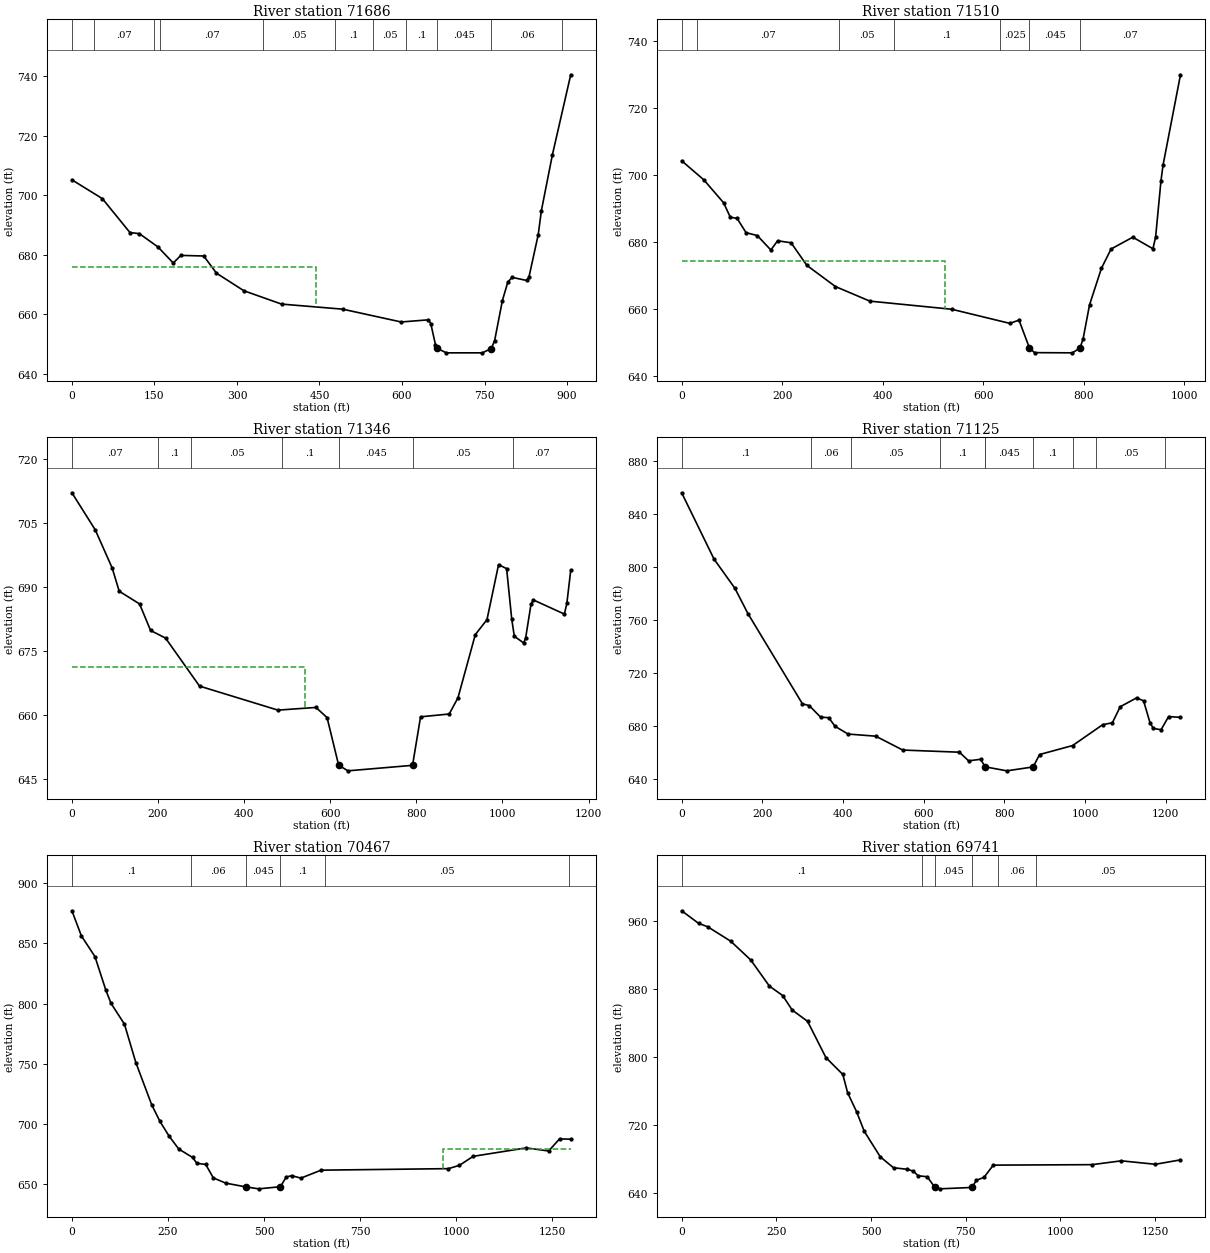
Type RM Length L Ch R = 1 ,71686   ,152.5,176,189.1
XS GIS Cut Line= 4
1609460.49239621394569.3099723061609305.77420664394835.528847027
1608929.56669677395183.4196157931608875.03338867395250.391627706
#Sta/Elev= 30
       0  705.13    55.3  698.82   105.5  687.42   122.6  687.05   156.4  682.58
   184.2  677.19     198  679.74   239.6  679.54   262.8  673.76   312.6  667.86
     381  663.38     492  661.68   598.5  657.37     648  658.09   652.3  656.85
   660.8  649.79   664.3  648.47   680.6     647     746     647   762.4  648.45
   768.4  651.13   782.5  664.57   792.5  670.87   800.5  672.34   826.9  671.31
   830.7  672.39   847.6  686.66   853.4   694.8   873.5  713.63   906.7  740.43
#Mann= 11 ,-1,0
       0     .06       0      40     .07       0     150     .05       0
     160     .07       0  347.91     .05       0  477.91      .1       0
  547.91     .05       0  607.91      .1       0   664.3    .045       0
   762.4     .06       0  890.32      .1       0
#XS Ineff= 2 , 0
          443.59  675.75
Permanent Ineff=
       F       F
Bank Sta=664.3,762.4
XS Rating Curve= 0 ,0
Exp/Cntr(USF)=0,0
Exp/Cntr=0.3,0.1

Type RM Length L Ch R = 1 ,71510   ,140.4,164,163.6
XS GIS Cut Line= 4
1609431.95618017394574.0938068561609300.15870393394835.691923937
1608758.60551596395044.1040904081608763.37893522395163.333866553
#Sta/Elev= 30
       0  704.23    44.1  698.55    83.4  691.72    96.8  687.41   110.2  687.07
   128.1  682.82   150.5  681.94   177.4  677.65   190.9  680.39   217.7   679.8
   249.1  673.06     306  666.75   374.4  662.41   537.3  659.99     653  655.78
   671.2  656.75     692648.4377   702.1  647.06   777.3     647   792.4 648.399
   798.7  651.13   811.6  661.33   835.2  672.19   854.4  677.94   897.6  681.46
   937.7  678.02     943  681.45   953.7  698.27   957.7  702.85   992.5  729.86
#Mann= 7 ,-1,0
       0     .06       0      30     .07       0  312.92     .05       0
  422.92      .1       0  632.92    .025       0     692    .045       0
   792.4     .07       0
#XS Ineff= 2 , 0
          523.05  674.33
Permanent Ineff=
       F       F
Bank Sta=692,792.4
XS Rating Curve= 0 ,0
Exp/Cntr(USF)=0,0
Exp/Cntr=0.3,0.1

Type RM Length L Ch R = 1 ,71346   ,307.1,220.7,193.3
XS GIS Cut Line= 4
1609281.64466443394504.0491062161609249.50033017394708.981711184
1608561.39840398394970.1514234161608658.76131605395162.028340071
#Sta/Elev= 30
       0  712.18    54.3  703.47    93.6  694.53   109.8  689.11   157.2  686.12
   182.7  679.91   217.5  678.12   296.4  666.87   478.5  661.24   566.9  661.87
   592.7  659.48   619.5648.3457     641  647.01   791.2   648.3   809.8  659.67
   876.4  660.33   896.7  664.13     937  678.94   964.1  682.45     991  695.34
  1009.7   694.4  1021.6  682.57  1027.6  678.55  1049.3  676.98  1053.8  678.08
  1066.3  686.01  1071.7  687.07  1143.9  683.75  1149.6  686.26  1158.6  693.97
#Mann= 7 ,-1,0
       0     .07       0     200      .1       0  277.44     .05       0
  487.44      .1       0   619.5    .045       0   791.2     .05       0
 1023.44     .07       0
#XS Ineff= 2 , 0
          542.01  671.27
Permanent Ineff=
       F       F
Bank Sta=619.5,791.2
XS Rating Curve= 0 ,0
Exp/Cntr(USF)=0,0
Exp/Cntr=0.3,0.1

Type RM Length L Ch R = 1 ,71125   ,695.3,658.5,568.3
XS GIS Cut Line= 4
1608728.59107871393988.4002571231608741.17517049394428.828461602
1608483.51011119394922.5718533561608617.07064493395120.379518626
#Sta/Elev= 30
       0  856.21    80.2  806.12   131.9   784.1   164.2  764.96   299.2  696.86
   316.3  695.45   344.3  686.75   364.3  686.37   380.3  679.82   412.3     674
   480.9   672.4   547.9  661.92   688.4  660.29     711  653.78   740.6  654.93
   752.5  649.23   805.7  646.22   871.1  649.17     887  658.54   968.9  665.32
  1043.3  681.04  1067.5  682.54  1086.8  694.62  1127.3   701.3  1144.7  699.12
  1160.7  682.56  1168.8  678.26  1188.1  677.27  1206.8  687.22  1236.2  686.59
#Mann= 10 ,-1,0
       0      .1       0     320     .06       0     420     .05       0
  640.61      .1       0  750.61    .025       0   752.5    .045       0
   871.1      .1       0  970.61     .06       0 1027.54     .05       0
 1197.54     .07       0
Bank Sta=752.5,871.1
XS Rating Curve= 0 ,0
Exp/Cntr(USF)=0,0
Exp/Cntr=0.3,0.1

Type RM Length L Ch R = 1 ,70467   ,744.8,726.3,661.4
XS GIS Cut Line= 4
1607574.35203676394357.2057915671607855.31538112394507.716600676
1608417.06811058395010.2412293351608603.88703995395136.792992553
#Sta/Elev= 30
       0  877.08    24.7  856.17    59.9  839.07    88.2  811.22   101.8  800.16
   136.7   782.9   166.3  751.04   207.6  715.91   228.9  702.23   252.7  689.97
   278.1  679.15     314  672.17   325.2  667.29   348.2  666.36     368  655.17
   400.3  650.84     452  647.73   486.2  646.09  542.57  647.85   557.8  655.94
     572  657.03   595.9  654.99   648.5   661.6   979.9  662.87  1008.3  665.59
  1044.3   673.1  1182.4   680.1  1240.6  677.53  1269.1  687.61  1298.1  687.32
#Mann= 6 ,-1,0
       0      .1       0     310     .06       0     452    .045       0
  542.57      .1       0  658.74     .05       0 1292.46     .07       0
#XS Ineff= 2 , 0
                          966.26          679.44
Permanent Ineff=
       F       F
Bank Sta=452,542.57
XS Rating Curve= 0 ,0
Exp/Cntr(USF)=0,0
Exp/Cntr=0.3,0.1

Type RM Length L Ch R = 1 ,69741   ,668.1,662.4,657.3
XS GIS Cut Line= 6
1607280.14544869 395422.521724791607378.46086885395406.516507447
1607476.39046303395390.5746102041607761.69697902 395344.12883696
1608094.81179835395289.9005989581608577.43284597395196.132680378
#Sta/Elev= 30
       0  971.86    44.5  957.14    68.9  953.03   129.7  936.06   182.3  914.11
   231.7  883.32   266.6  872.32   291.8  855.26   332.3  842.06   380.9  799.36
   425.5  779.58   438.1   758.2     462  735.61   482.2  712.71   524.5  682.76
   559.3  670.01   595.7  668.17   611.9  665.92   624.1  660.62   648.4  659.42
   668.7  646.81   680.8  645.22  766.26  646.83   778.1  655.22   798.3  658.71
   822.7  673.07  1083.6  673.63  1160.9  678.13  1250.7  674.06    1317  679.24
#Mann= 6 ,-1,0
       0      .1       0  635.39     .06       0   668.7    .045       0
  766.26     .08       0  835.39     .06       0  935.39     .05       0
Bank Sta=668.7,766.26
XS Rating Curve= 0 ,0
Exp/Cntr(USF)=0,0
Exp/Cntr=0.3,0.1

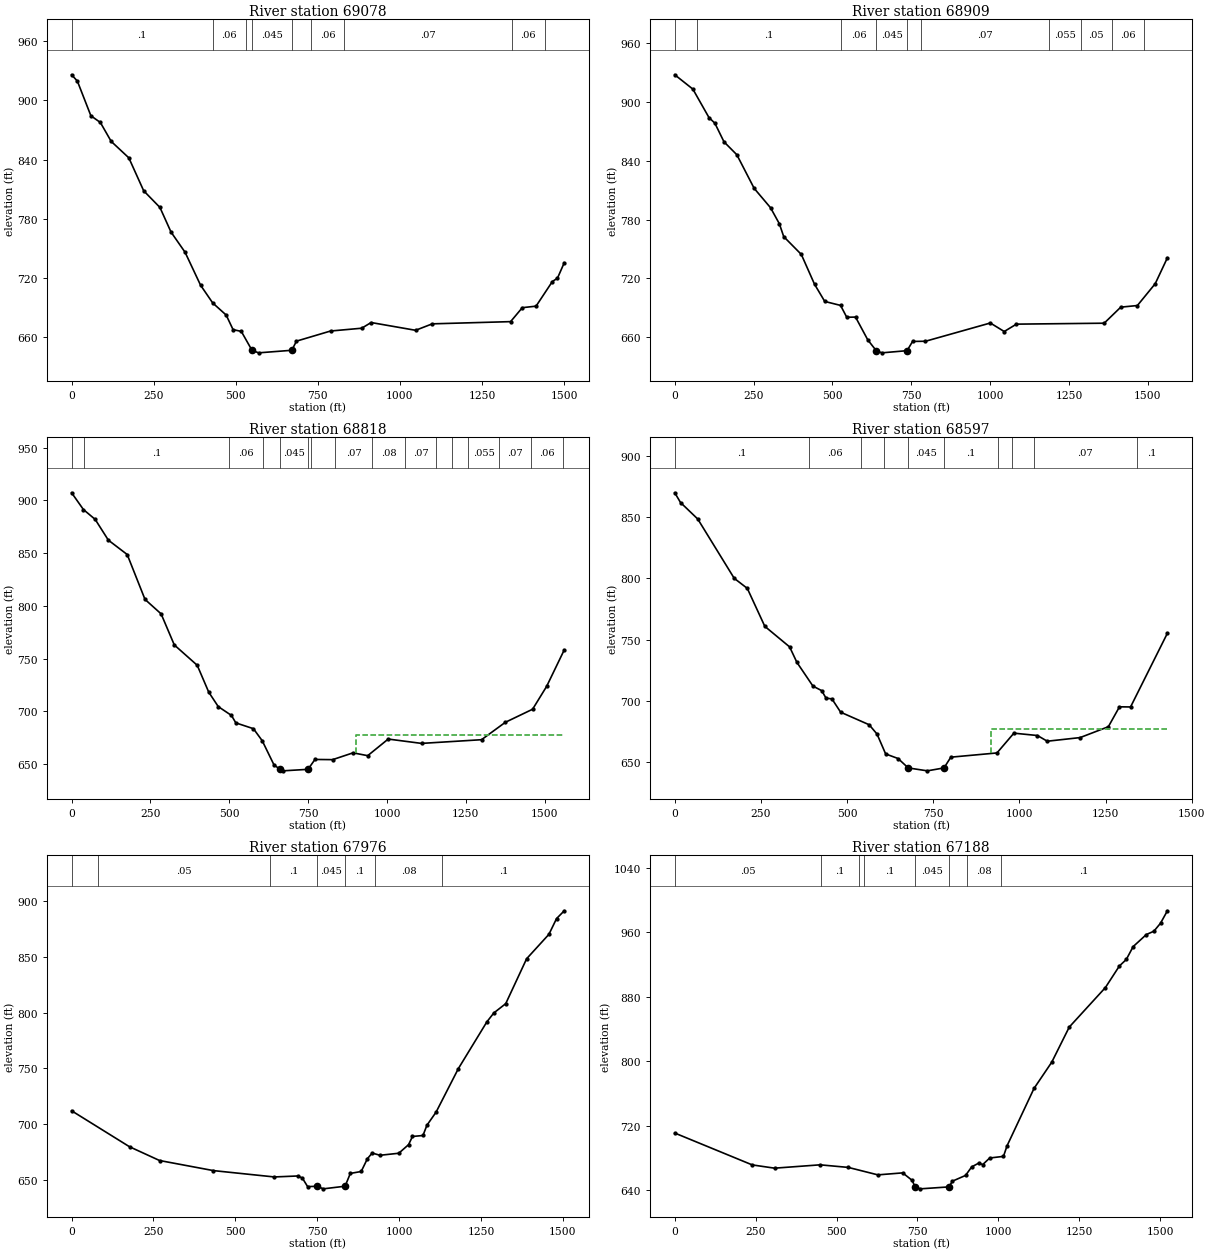
Type RM Length L Ch R = 1 ,69078   ,185.1,169.2,155.1
XS GIS Cut Line= 3
1607495.15119227  396111.23065381608378.98363384395888.445037837
1608956.30008015396007.343614133
#Sta/Elev= 30
       0  925.95    17.5  919.57    58.7  884.43    87.6  877.61   120.6  858.44
   174.3  841.79   219.6  808.39   269.1  791.52   302.8  766.61   345.7  746.09
   392.9  712.71     430  694.69   470.9  682.48   491.9  667.72     517  665.91
   549.6  646.73   569.7  644.19  670.82  646.78     685  656.04   788.9   666.3
   883.8  669.14   912.5   674.9    1048  667.03  1098.8  673.57  1337.4  675.81
  1373.1  689.95    1415  691.49  1464.5  716.37  1480.3   719.9  1500.9  735.49
#Mann= 9 ,-1,0
       0      .1       0     430     .06       0     530      .1       0
   549.6    .045       0  670.82      .1       0     730     .06       0
     830     .07       0 1341.48     .06       0 1441.48      .1       0
Bank Sta=549.6,670.82
XS Rating Curve= 0 ,0
Exp/Cntr(USF)=0,0
Exp/Cntr=0.3,0.1

Type RM Length L Ch R = 1 ,68909   ,90.9,90.9,90.7
XS GIS Cut Line= 6
1607550.66108734396471.974348228 1607889.9878365 396271.46425056
1608046.03115959396179.257742073 1608336.5935706396007.561235066
1608417.30535143395959.8680889861608966.28588075396044.753745984
#Sta/Elev= 30
       0  927.94    57.4  913.29   108.5  884.21   127.1   878.5   156.1  859.43
   196.8  846.25   251.8  811.88   303.7   792.1   331.6  775.75   345.5  762.58
   401.3  744.37   443.1  713.98   475.6  696.35   525.7   692.3   545.3   680.2
   573.2  680.37   612.2  656.98   639.2  645.96   656.8  643.84   736.6  646.06
   754.1  655.49     795  655.68  1000.6  674.33  1044.7  665.63  1083.3  673.16
  1361.6  674.12  1414.2  690.52  1466.9  692.18  1523.5  714.49  1562.1  740.98
#Mann= 10 ,-1,0
       0     .06       0      70      .1       0  527.89     .06       0
   639.2    .045       0   736.6     .08       0  780.39     .07       0
 1186.64    .055       0 1286.64     .05       0 1386.64     .06       0
 1486.64      .1       0
Bank Sta=639.2,736.6
XS Rating Curve= 0 ,0
Exp/Cntr(USF)=0,0
Exp/Cntr=0.3,0.1

Type RM Length L Ch R = 1 ,68818   ,218.2,221.5,225.8
XS GIS Cut Line= 6
1607583.80044851396557.7406471671607923.12719767396357.230549499
1608079.17052075396265.0240410121608369.73293176396093.327534005
1608450.44471259396045.6343879251608999.42524192396130.520044923
#Sta/Elev= 30
       0  907.21    37.5   891.3    74.7  882.01   116.5  862.33   176.3   848.7
   232.7  806.19   283.8  792.47   325.6  763.05   398.3  743.77   434.8  718.31
     465  704.61   506.8  696.26   520.7  689.19   576.5  683.69   604.4  672.28
   641.5  649.51   660.1  645.25   669.9  643.75   749.6645.1791   771.6  654.54
   827.6  654.35   892.4   660.8   938.9  658.12  1003.9  673.86  1109.5  669.75
  1299.8  673.25  1375.2  689.72  1461.7  702.12  1506.2  723.75  1562.1  758.34
#Mann= 16 ,-1,0
       0     .06       0      40      .1       0  497.89     .06       0
  605.39      .1       0   660.1    .045       0   749.6      .1       0
  760.39     .08       0  835.39     .07       0  952.89     .08       0
 1056.64     .07       0 1156.64    .055       0 1206.64     .07       0
 1256.64    .055       0 1356.64     .07       0 1456.64     .06       0
 1556.64      .1       0
#XS Ineff= 2 , 0
                             901          677.39
Permanent Ineff=
       F       F
Bank Sta=660.1,749.6
XS Rating Curve= 0 ,0
Exp/Cntr(USF)=0,0
Exp/Cntr=0.3,0.1

Type RM Length L Ch R = 1 ,68597   ,618.3,620.8,621.1
XS GIS Cut Line= 4
1607637.11331091396642.7623789451608155.36800279396463.676390553
1608541.55323775396267.4183203251608986.10957808396211.603520324
#Sta/Elev= 30
       0  869.93    16.7  861.97    66.7  848.49   172.5  800.04   210.5   791.8
   261.3  760.78   333.3  743.98   354.4  731.35     401  711.94   426.4  708.22
   439.1  702.03     456  701.53   481.4  690.61   564.1  680.36   586.9  672.77
     612   656.5   647.9  652.77   677.6645.0576   733.1  642.69  781.35  645.09
   801.1  653.86     935  657.31   984.1  673.48  1052.6  671.55  1080.9   666.9
  1176.2  669.86  1258.2  678.73  1290.5  695.01  1322.7   694.9  1429.6  755.16
#Mann= 10 ,-1,0
       0      .1       0     390     .06       0     540     .05       0
  608.32      .1       0   677.6    .045       0  781.35      .1       0
  938.32     .05       0  978.32     .06       0 1041.52     .07       0
 1341.52      .1       0
#XS Ineff= 2 , 0
                          917.81          677.21
Permanent Ineff=
       F       F
Bank Sta=677.6,781.35
XS Rating Curve= 0 ,0
Exp/Cntr(USF)=0,0
Exp/Cntr=0.3,0.1

Type RM Length L Ch R = 1 ,67976   ,752,787.2,820.3
XS GIS Cut Line= 4
1607927.71146463397095.2205122481608152.77717239397109.549841127
1608885.52086351396796.9125329181609366.79867142396770.516451065
#Sta/Elev= 30
       0  712.12   176.8  679.95   268.5  667.64   433.1  658.61     619  652.94
   690.1  653.81   704.4  652.02   720.6  644.32   750.1  644.58   768.4  642.31
  835.03  644.65     851   656.1   884.2  657.82   903.2  669.28   917.7  674.32
   941.6  672.32   998.9  674.14  1028.8  681.81  1040.8  689.14  1072.8  690.01
  1084.9  699.18  1112.9  710.93    1181  749.91    1268  791.66  1289.2  799.61
  1325.5  807.92  1389.3  848.07  1457.4  869.93  1480.7  883.99  1504.2  890.97
#Mann= 7 ,-1,0
       0     .06       0      80     .05       0  605.52      .1       0
   750.1    .045       0  835.03      .1       0  925.52     .08       0
 1132.17      .1       0
Bank Sta=750.1,835.03
XS Rating Curve= 0 ,0
Exp/Cntr(USF)=0,0
Exp/Cntr=0.3,0.1

Type RM Length L Ch R = 1 ,67188   ,367.9,370.4,373
XS GIS Cut Line= 6
1607910.32137469397275.234083685 1608309.0958265397437.819014745
1608391.96231645 397557.03620525 1608423.2106705397570.057003898
1608909.66770284397750.2265910631609279.27293475397887.117393402
#Sta/Elev= 30
       0  711.18   239.5  671.66   308.6  667.62   449.1  671.77   536.3  668.56
   627.7  659.32   704.5  661.78   733.7  652.48   742.9  644.28   758.6  641.99
  847.41  644.39   858.1  651.49   898.7  658.62   917.8  669.24   939.1  673.81
   951.9  672.12   973.4  680.23  1015.9  682.24    1027  695.34  1110.3  766.49
  1165.2  799.08  1219.3  842.61  1330.9  891.55  1374.2  918.34  1395.5   926.4
  1416.8  942.41  1457.6  957.35  1480.8  961.46  1501.3  971.36  1522.6   986.8
#Mann= 8 ,-1,0
       0     .05       0  450.64      .1       0  570.64     .05       0
  585.83      .1       0   742.9    .045       0  847.41    .025       0
  902.19     .08       0 1007.19      .1       0
Bank Sta=742.9,847.41
XS Rating Curve= 0 ,0
Exp/Cntr(USF)=0,0
Exp/Cntr=0.3,0.1