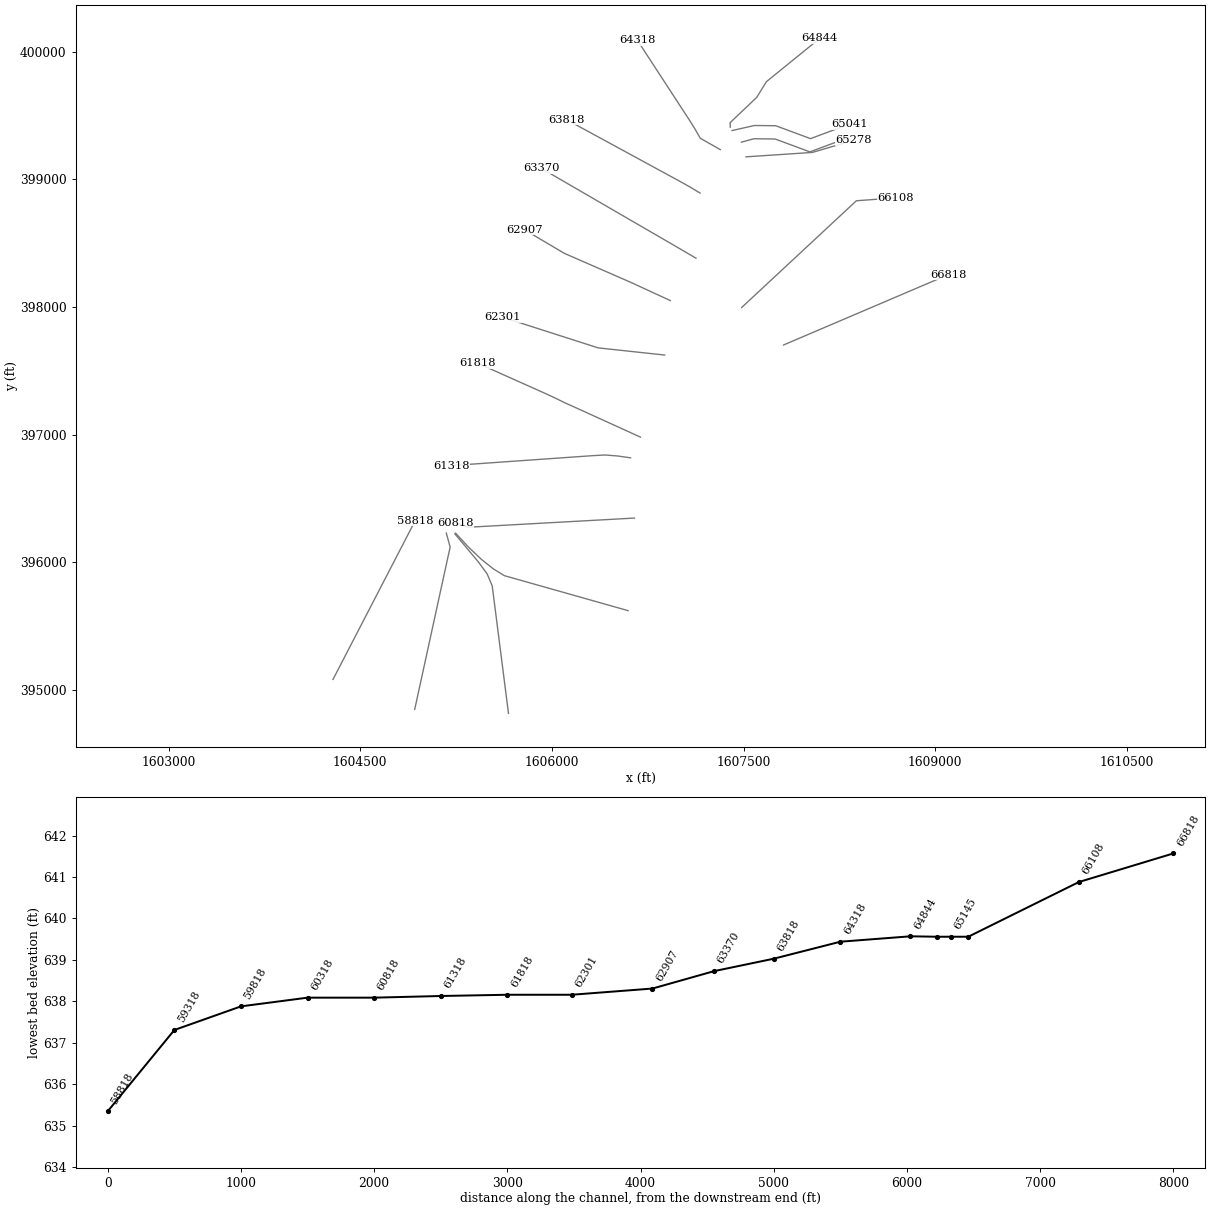
HEC-RAS study FISHINGCK.prj: FISHINGCK

--- FISHINGCK.g01 (geometry) --- (continued)

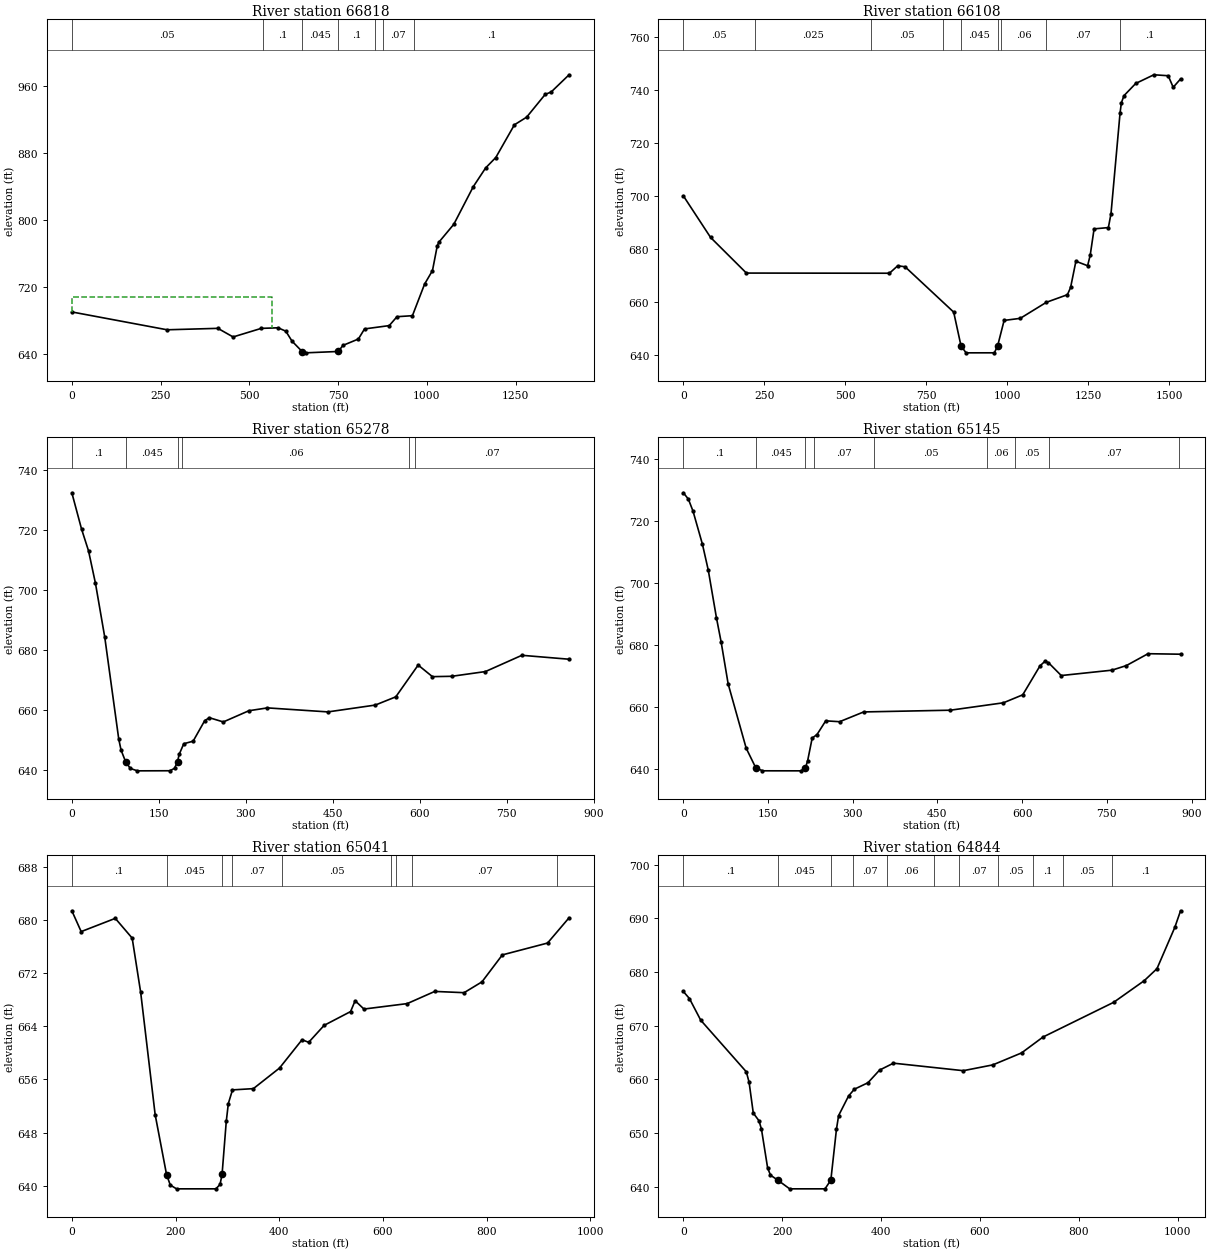
Type RM Length L Ch R = 1 ,66818   ,690.5,709.6,729.1
XS GIS Cut Line= 6
1607813.77997543397702.5631606731608503.84421209397997.347019926
1608572.81454659398026.8102155921608828.58011118398136.068855345
1608919.10388026398174.7393816711609101.94767468398252.847165093
#Sta/Elev= 30
       0  690.31   268.4  669.05   411.4  670.77   454.3  660.51   533.6  670.73
     581  671.42   602.8  667.39   620.2  655.57  648.74643.1489   658.5  641.57
   750.7   643.2   763.7  650.42   807.2  658.04   824.6  670.08   894.2  674.04
     916  684.65   959.5  685.84   993.8  723.54    1016  739.63  1029.1  768.35
  1033.4  773.14  1076.1  794.83  1130.9  839.62  1165.8  862.02  1194.4  874.42
  1246.8   913.4  1281.3  922.52  1333.5  949.62  1350.4  952.52  1400.8  973.03
#Mann= 7 ,-1,0
       0     .05       0  537.89      .1       0  648.74    .045       0
   750.7      .1       0  855.39     .06       0  875.39     .07       0
  962.89      .1       0
#XS Ineff= 2 , 0
          564.82  707.75
Permanent Ineff=
       F       F
Bank Sta=648.74,750.7
XS Rating Curve= 0 ,0
Exp/Cntr(USF)=0,0
Exp/Cntr=0.3,0.1

Type RM Length L Ch R = 1 ,66108   ,851.7,830.5,791.3
XS GIS Cut Line= 3
 1607485.7277409397996.0183255721608383.07791993 398831.76388714
1608690.19488403398854.833796135
#Sta/Elev= 30
       0  700.11    84.1  684.41   194.6  670.97     636  670.91   661.5  673.72
   684.1  673.35   834.2  656.24   856.8   643.5   872.4  640.88   959.8  640.89
     970   643.6   989.8  653.11  1039.6  653.89    1120  659.93  1185.1  662.81
  1194.9  665.53  1211.3  675.43  1247.4  673.74  1255.4  677.69  1267.4  687.64
  1311.5  688.13  1319.6  693.39  1347.6  731.44  1351.6   735.2  1359.7   737.9
  1395.8  742.49  1451.8  745.77  1496.1  745.41  1511.5  741.05  1534.2  744.19
#Mann= 9 ,-1,0
       0     .05       0     220    .025       0     580     .05       0
     800      .1       0   856.8    .045       0     970      .1       0
     980     .06       0    1120     .07       0 1346.26      .1       0
Bank Sta=856.8,970
XS Rating Curve= 0 ,0
Exp/Cntr(USF)=0,0
Exp/Cntr=0.3,0.1

Type RM Length L Ch R = 1 ,65278   ,135.5,132.5,128.4
XS GIS Cut Line= 3
1607519.40965388399175.9323778681608039.58176544399210.548889511
1608362.17848492399305.706607923
#Sta/Elev= 30
       0  732.41    16.7  720.33    28.8  713.01    40.8  702.12    56.8  684.17
    80.9  650.18    84.9  646.48    92.9  642.54   100.9  640.37     113  639.56
   169.1  639.59   177.1   640.4   182.3  642.61   185.1  645.05   193.1  648.61
   209.2  649.46   229.2  656.32   237.2   657.3   261.3  655.89   305.4  659.63
   337.4  660.58   441.7  659.24   523.4  661.52   558.8  664.27   597.4  674.88
     622  671.01   655.4  671.13   713.4  672.71   776.3  678.14   857.7  676.83
#Mann= 6 ,-1,0
       0      .1       0    92.9    .045       0   182.3      .1       0
     190     .06       0  581.32     .05       0  591.32     .07       0
Bank Sta=92.9,182.3
XS Rating Curve= 0 ,0
Exp/Cntr(USF)=0,0
Exp/Cntr=0.3,0.1

Type RM Length L Ch R = 1 ,65145   ,106,104.5,103.9
XS GIS Cut Line= 5
1607483.54763459399290.7727248211607580.69312816399317.544310276
1607747.60311432399315.6034964831608019.31704528399214.681179271
1608322.08399691399327.248379239
#Sta/Elev= 30
       0  729.25     8.9  727.22    17.2  723.31    33.8  712.68    44.2  704.28
    58.7  688.88      67  681.08    79.4  667.59   111.3  646.87   128.2  640.58
   140.2  639.57   208.2  639.56   216.2  640.46   220.2  642.85   228.2  650.13
   236.8  651.28   252.2  655.69   276.8  655.41   319.4  658.56     473  659.12
   566.9  661.51   601.1  664.08   631.7  673.43   640.5   674.9   646.7  674.44
   669.3   670.3     759  672.03   784.6  673.51     823  677.34   880.6  677.18
#Mann= 9 ,-1,0
       0      .1       0   128.2    .045       0   216.2      .1       0
  230.77     .07       0  337.69     .05       0  537.69     .06       0
  587.54     .05       0  647.54     .07       0  877.54     .06       0
Bank Sta=128.2,216.2
XS Rating Curve= 0 ,0
Exp/Cntr(USF)=0,0
Exp/Cntr=0.3,0.1

Type RM Length L Ch R = 1 ,65041   ,153.8,197.4,235.2
XS GIS Cut Line= 5
1607410.58274006 399381.872583431607585.54516264399421.377848177
 1607752.4551488399419.4370343851608024.16907976399318.514717172
 1608326.9360314 399431.08191714
#Sta/Elev= 30
       0  681.35      18  678.22    83.8  680.21   116.4  677.24   132.8  669.08
   160.7  650.72   182.7  641.71   189.9  640.13   201.9  639.56   277.9  639.56
   285.9  640.22   289.8641.7313   297.9  649.69   301.9  652.38   309.9  654.43
   350.2  654.62   400.6  657.71   444.1  661.97   456.9  661.58   486.7  664.13
   537.7   666.2   546.5  667.83   563.5  666.58     647   667.4   700.1  669.23
   756.7  669.04   791.2  670.67   830.5  674.72   917.7   676.5   959.2   680.3
#Mann= 9 ,-1,0
       0      .1       0   182.7    .045       0   289.8    .025       0
  309.37     .07       0  406.29     .05       0  616.29     .07       0
  626.29     .05       0  656.14     .07       0  936.14     .05       0
Bank Sta=182.7,289.8
XS Rating Curve= 0 ,0
Exp/Cntr(USF)=0,0
Exp/Cntr=0.3,0.1

Type RM Length L Ch R = 1 ,64844   ,454.6,525.5,586.7
XS GIS Cut Line= 5
1607396.52670071399408.1303691961607395.07153583399443.340969867
1607603.51659913399641.4983117411607679.10959508399764.383932911
1608097.16112399400104.000617449
#Sta/Elev= 30
       0  676.35    12.3  675.04    35.2     671   127.4  661.38     133  659.44
   141.5  653.69   153.1  652.25   158.1  650.65   170.5  643.47   176.3  642.12
   191.2  641.18   215.1  639.57   286.6  639.57  298.36   641.2   309.8  650.74
   314.1  653.23   334.2  656.87   345.8  658.13   373.4  659.34   396.9   661.7
     425  662.99   566.3  661.59     626  662.67   684.1   664.9   727.5  667.86
   870.4  674.33   932.2  678.36     958   680.6   994.1   688.3  1005.7  691.39
#Mann= 11 ,-1,0
       0      .1       0   191.2    .045       0  298.36     .05       0
  342.84     .07       0  412.84     .06       0  507.12     .05       0
  557.12     .07       0  637.12     .05       0  707.12      .1       0
  767.12     .05       0  867.12      .1       0
Bank Sta=191.2,298.36
XS Rating Curve= 0 ,0
Exp/Cntr(USF)=0,0
Exp/Cntr=0.3,0.1

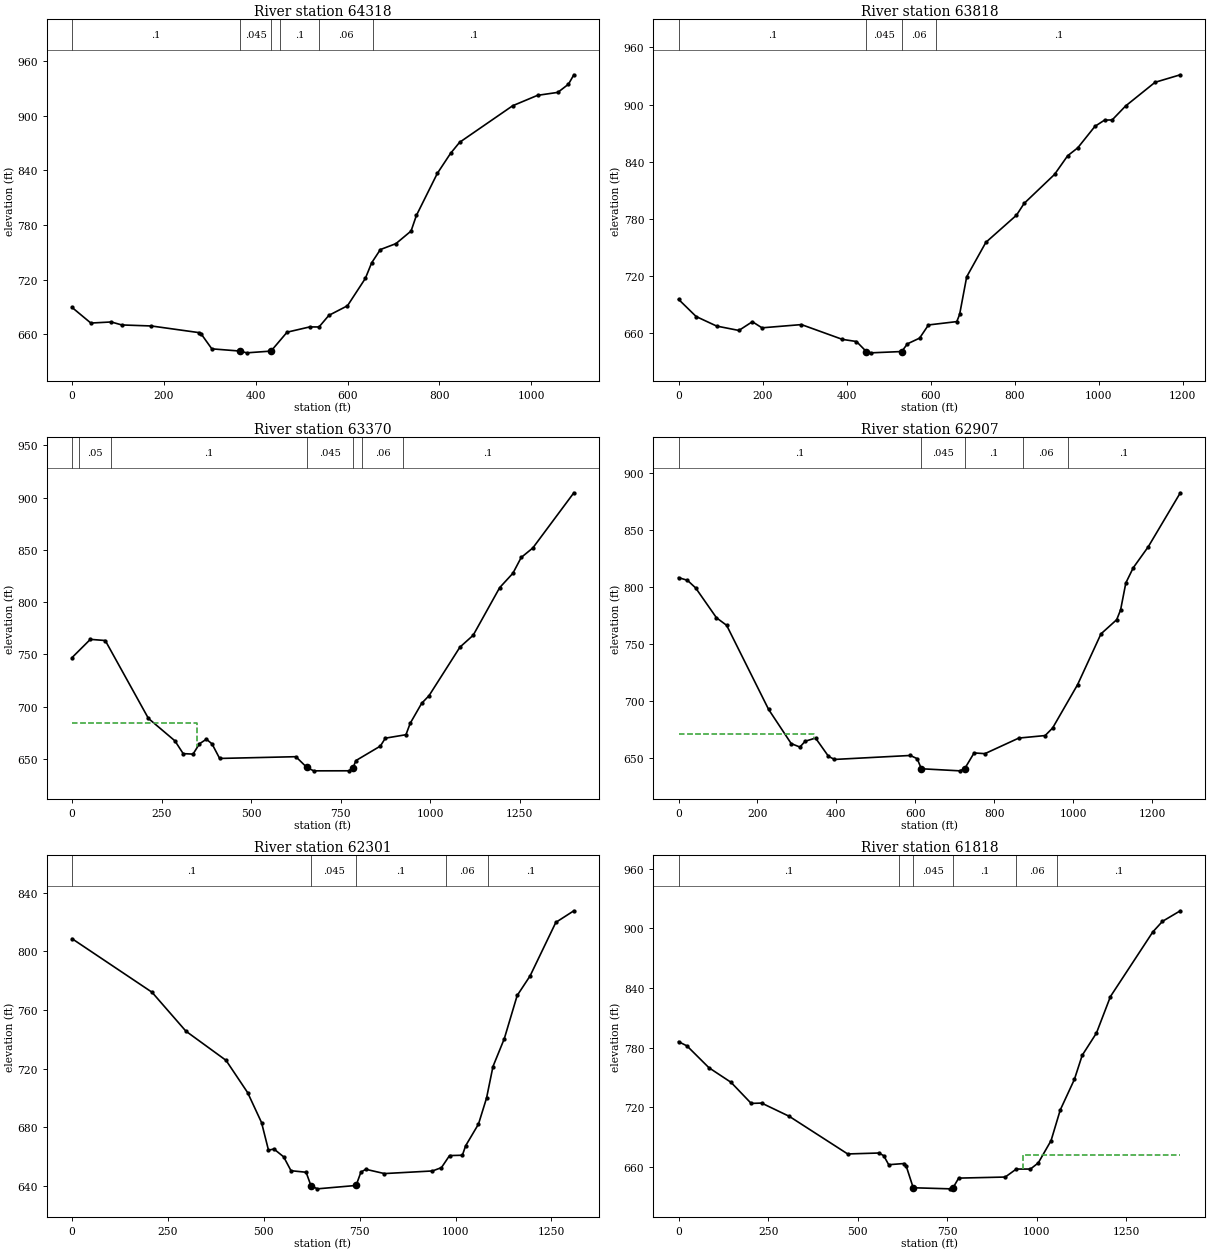
Type RM Length L Ch R = 1 ,64318   ,482.7,500,518.8
XS GIS Cut Line= 6
1607318.26797607399232.3332293261607161.83836593399321.323374584
1607118.35945025399397.4265688361607078.40086876399460.906100675
1606884.00427592399759.4425770941606668.93219951400089.731614679
#Sta/Elev= 30
       0  689.32    40.9  672.18    85.3  673.38   108.3   670.1   172.8  668.97
     276   661.7   280.7  660.57   304.4  643.84   366.2 641.366   380.4  639.44
   433.3641.3557   468.3  662.14   517.6  667.93   537.9  667.89   559.4  680.65
   599.9  691.19   638.9  721.33   652.5  738.34   671.5  752.96   705.4  759.47
   738.4  773.33     750  790.45   795.6  836.69   824.3  858.62   844.1  870.84
   959.8  911.07  1013.9  922.49  1058.1  925.74  1081.2  934.72    1093  945.09
#Mann= 6 ,-1,0
       0      .1       0   366.2    .045       0   433.3     .06       0
  452.63      .1       0  537.63     .06       0  655.13      .1       0
Bank Sta=366.2,433.3
XS Rating Curve= 0 ,0
Exp/Cntr(USF)=0,0
Exp/Cntr=0.3,0.1

Type RM Length L Ch R = 1 ,63818   ,449.9,448.1,447.9
XS GIS Cut Line= 6
 1607160.0302348398892.3095914591607082.35820992398939.040674582
1606997.81474385398986.353244007 1606374.7933521399325.554009169
1606288.33880059399372.6234688461606113.71447793399467.697097585
#Sta/Elev= 30
       0  695.27    41.9  677.19    90.6  667.18   143.6  662.56   175.7  671.75
   198.6  665.32   292.5  668.72   389.9  653.18   423.4  650.94     447640.3609
   458.2  639.03   531.2  640.41   544.7  648.49   573.7   654.5   594.8  668.34
   662.2  671.86   668.9  679.33   685.8  718.97   731.4  755.15   804.3  783.71
   822.5  796.09   894.8  826.53   926.1  846.19   950.1  854.48     991  877.08
  1013.8   883.6    1032  883.82  1063.9  898.45    1134  923.35  1194.2  931.27
#Mann= 4 ,-1,0
       0      .1       0     447    .045       0   531.2     .06       0
  613.78      .1       0
Bank Sta=447,531.2
XS Rating Curve= 0 ,0
Exp/Cntr(USF)=0,0
Exp/Cntr=0.3,0.1

Type RM Length L Ch R = 1 ,63370   ,455.2,462.9,469.5
XS GIS Cut Line= 6
 1607128.0474422398382.1484310351607042.16867695398432.618146362
1606956.43918962398482.5662091991606871.31140712398531.994916113
1606174.07526878398936.8412192781605917.00327637399086.108965369
#Sta/Elev= 30
       0  747.04      51  764.46    92.7  763.34   213.1  688.87   287.1  667.41
   310.2  655.19   337.7  654.73   355.6   664.6     375  668.99   390.7  664.49
     412  650.58   624.7  652.25  655.46  641.98   674.6  638.73   772.8  638.77
   784.7641.8987   792.2  648.51   860.6   662.4   874.5  669.97   932.1  673.28
   943.9  684.17     976  703.32   996.5  710.61  1082.7  756.99  1119.7  768.36
  1193.7  813.91  1230.6  827.65  1253.8  842.76  1286.2  851.84  1400.8  904.62
#Mann= 7 ,-1,0
       0     .06       0      20     .05       0  109.61      .1       0
  655.46    .045       0   784.7      .1       0  810.39     .06       0
  922.89      .1       0
#XS Ineff= 2 , 0
          349.68  684.91
Permanent Ineff=
       F       F
Bank Sta=655.46,784.7
XS Rating Curve= 0 ,0
Exp/Cntr(USF)=0,0
Exp/Cntr=0.3,0.1

Type RM Length L Ch R = 1 ,62907   ,601.1,606.3,610.9
XS GIS Cut Line= 4
 1606927.4577469398050.1994260651606615.19812652398194.057649482
1606098.47813101398419.8512609651605785.26163837398605.078013138
#Sta/Elev= 30
       0  808.37    22.4  806.03    43.3  799.31    96.2  772.99   121.9  766.39
   228.3  692.33   285.5  662.31   307.6  659.22   320.8  664.34   347.2  667.17
     380  651.08   395.2  648.34   587.3  651.84   604.7  649.03   615.4  640.14
   712.6  638.31  725.06  640.17     749  654.08   776.4  653.43   862.3  667.15
     929  669.36   947.9  675.98  1011.2  714.13  1070.5  758.84  1110.3  771.32
  1120.2  779.91  1133.5  803.68  1152.3  817.04  1190.3  835.49  1271.6  883.03
#Mann= 5 ,-1,0
       0      .1       0   615.4    .045       0  725.06      .1       0
   873.8     .06       0   987.7      .1       0
#XS Ineff= 2 , 0
          343.03  670.99
Permanent Ineff=
       F       F
Bank Sta=615.4,725.06
XS Rating Curve= 0 ,0
Exp/Cntr(USF)=0,0
Exp/Cntr=0.3,0.1

Type RM Length L Ch R = 1 ,62301   ,489.9,483,474
XS GIS Cut Line= 3
1606883.28977663397623.5664516881606362.51501914 397679.67677767
1605615.38938287397919.502194495
#Sta/Elev= 30
       0  808.62   208.4  772.15   296.9   745.6   401.5  725.72   457.8  703.75
   494.1  683.32   512.2   664.5   526.4  665.31   551.8  659.95   570.9  650.51
   610.3  649.47   622.9  640.32   639.7  638.16   740.6  640.46   753.2  649.53
   765.8  651.49   814.5  648.56   939.8  650.35   963.2  652.62   984.3  660.82
  1017.8  661.06  1026.2  667.46  1059.8   682.3  1080.8  700.01  1097.6  721.53
  1127.1  740.48  1160.7  769.92  1194.3  783.24  1261.5  819.75  1308.5  827.65
#Mann= 5 ,-1,0
       0      .1       0   622.9    .045       0   740.6      .1       0
  973.79     .06       0 1083.79      .1       0
Bank Sta=622.9,740.6
XS Rating Curve= 0 ,0
Exp/Cntr(USF)=0,0
Exp/Cntr=0.3,0.1

Type RM Length L Ch R = 1 ,61818   ,472.3,499.6,525.7
XS GIS Cut Line= 6
1606693.57486676396980.8100109991606170.11725226397219.173051342
1606101.62591942397249.7149850131606011.85707009397293.784122586
1605943.62328267397325.0215929151605417.92617135397560.239954501
#Sta/Elev= 30
       0  786.15    23.6  781.89      85  759.92   146.5   745.3   202.9  724.07
     232  724.41   309.2  711.07   472.3  673.24   559.7  674.19     573  671.45
   586.8  662.43   629.9  663.62   635.3  661.52  655.27 639.243   758.7  638.16
   766.4   639.2   782.2  648.95   912.2  650.02   943.1  658.05   982.6  658.06
  1004.5  664.25  1040.2  686.69  1065.8  717.46  1105.3   748.2  1127.1  772.44
  1166.9  794.82    1206  831.57  1324.3  896.52  1351.2  907.15  1401.1  917.79
#Mann= 6 ,-1,0
       0      .1       0  615.18    .025       0  655.27    .045       0
   766.4      .1       0  942.79     .06       0 1056.62      .1       0
#XS Ineff= 2 , 0
                          961.41          672.37
Permanent Ineff=
       F       F
Bank Sta=655.27,766.4
XS Rating Curve= 0 ,0
Exp/Cntr(USF)=0,0
Exp/Cntr=0.3,0.1

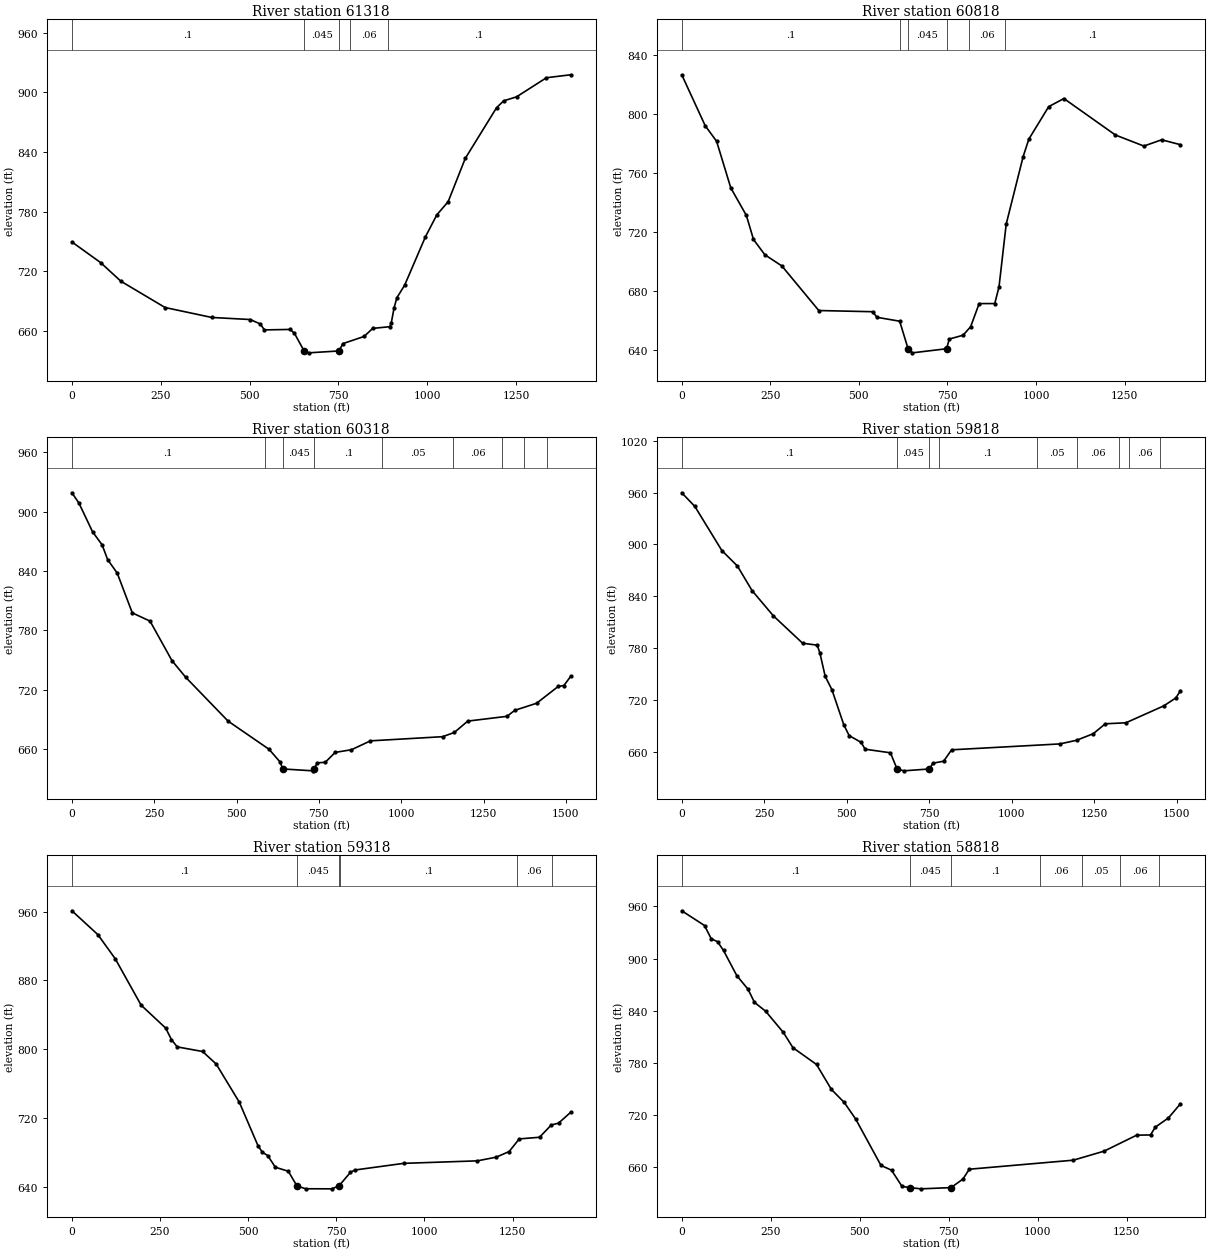
Type RM Length L Ch R = 1 ,61318   ,501,500,499.3
XS GIS Cut Line= 6
 1606616.0897855396818.7420936671606515.22712635396833.070477083
1606415.21879618396840.8175088321606316.91912401396835.400853008
1606220.28250626396828.6059190931605216.12112875396758.001401499
#Sta/Elev= 30
       0  749.65    80.8  728.89   137.8  710.18   262.3  683.71   393.7  673.72
   501.9  671.63     530  667.24     542  661.19   614.2  661.67   626.3  657.89
   653.8  639.98   666.3  638.13  752.28640.0371   762.6  647.37   822.7  654.62
   846.8  662.71   894.9  664.43   898.9  667.78   906.9   683.2   914.9  693.55
   936.8   706.2   995.1  754.69  1027.3  776.89  1059.3  790.18  1107.4  833.67
  1195.6  884.72  1215.7  891.61  1251.8  895.61    1336  914.84  1404.1  917.81
#Mann= 5 ,-1,0
       0      .1       0   653.8    .045       0  752.28    .025       0
  783.76     .06       0  888.76      .1       0
Bank Sta=653.8,752.28
XS Rating Curve= 0 ,0
Exp/Cntr(USF)=0,0
Exp/Cntr=0.3,0.1

Type RM Length L Ch R = 1 ,60818   ,519.3,500,486.8
XS GIS Cut Line= 6
1606646.28198235396346.8132475021605996.88170634396310.933726087
1605897.03413701396305.417332917 1605641.1744125396291.280878261
1605347.09166734396275.0328792481605245.55807775 396307.10958676
#Sta/Elev= 30
       0  826.42    66.3  791.86    98.3  781.42   138.4  749.82   182.4  731.14
   202.5  714.86   234.5  704.53   282.6  696.93   386.8  666.74     539  665.94
     551  662.16   615.1  659.52  638.64640.9794   651.2  638.09   747.3  640.86
   755.3  647.44   793.9  650.01   815.4  655.77   839.4  671.44   883.5  671.47
   895.5  682.79   915.8  725.32   963.6     771   979.7  782.84  1035.7  804.83
  1078.6  810.33    1224  785.63  1304.3  778.15  1354.6  782.38  1407.7  779.06
#Mann= 6 ,-1,0
       0      .1       0  615.39    .025       0  638.64    .045       0
   747.3      .1       0  810.39     .06       0  912.89      .1       0
Bank Sta=638.64,747.3
XS Rating Curve= 0 ,0
Exp/Cntr(USF)=0,0
Exp/Cntr=0.3,0.1

Type RM Length L Ch R = 1 ,60318   ,561.4,500,448.8
XS GIS Cut Line= 6
1606596.49238376 395621.858004511605627.89622384395895.986393258
1605541.15591176395949.6979000121605448.27387968396023.875573173
1605349.76685885396117.4301760941605246.89567351396228.308235168
#Sta/Elev= 30
       0   919.2    21.2  908.86    62.7  879.75    91.8  866.51   108.5   851.6
   137.6     838   183.3   797.8   237.3  789.43   303.9   749.5   345.4  732.73
   474.3  688.35   598.7  659.88   632.3  646.98   640.5640.0035     732  638.09
   736.2  639.94   744.5  646.13   769.5  646.75   799.5  656.73     849  659.44
   906.6  668.41  1125.7  672.61  1161.2  676.85  1202.1  688.37  1321.4   693.2
  1344.7  699.23  1411.3  706.42  1476.8  723.38  1494.1  724.35  1514.6  733.52
#Mann= 9 ,-1,0
       0      .1       0  585.39    .025       0   640.5    .045       0
   736.2      .1       0  942.89     .05       0 1158.66     .06       0
 1307.53      .1       0 1373.38     .06       0 1443.38      .1       0
Bank Sta=640.5,736.2
XS Rating Curve= 0 ,0
Exp/Cntr(USF)=0,0
Exp/Cntr=0.3,0.1

Type RM Length L Ch R = 1 ,59818   ,518.7,500,481.5
XS GIS Cut Line= 6
1605660.69241808394817.2293644251605533.42429993395815.792327926
1605493.92011385395909.6008673461605424.65581667 396003.82705684
1605337.95815542396107.4059179281605240.99115776396223.296106085
#Sta/Elev= 30
       0  959.74    39.6  943.99   121.5  892.91   168.7  874.95     213  846.56
   277.5  817.37   366.2  785.63   410.6  783.34   418.7  774.25   434.8  747.19
     455  731.89   491.2  691.12   507.4  678.65   543.5  670.89   555.8  662.92
   632.4  658.77   652.5  640.09   672.7  637.88  750.48640.0464   761.4  646.75
   793.7  649.03   817.9  662.22  1146.2  669.04  1196.5  673.24  1247.2  680.85
  1283.7  692.33  1346.3  693.52    1461  713.08  1497.5  722.25  1511.6  730.64
#Mann= 9 ,-1,0
       0      .1       0   652.5    .045       0  750.48    .025       0
  780.39      .1       0 1076.64     .05       0 1198.43     .06       0
 1325.37      .1       0 1355.37     .06       0 1450.45      .1       0
Bank Sta=652.5,750.48
XS Rating Curve= 0 ,0
Exp/Cntr(USF)=0,0
Exp/Cntr=0.3,0.1

Type RM Length L Ch R = 1 ,59318   ,516,500,485
XS GIS Cut Line= 6
1604926.77164184394848.6226743461605010.80526643395233.714095756
1605049.44035976395410.8049489261605086.69290993395581.796404839
1605204.12673017 396119.894081921605174.07560918396229.540516168
#Sta/Elev= 30
       0  961.14    73.6  933.37   122.7   905.4   196.4  851.21     266  824.52
   282.4  811.11   298.8  802.62   370.7  797.26   409.3  782.66   474.9  738.22
   528.1  687.32   540.3  680.03   555.6  675.97   577.2  662.46     614  657.77
  638.35640.6898   663.1  637.41   736.8  637.31   757.3  640.61   790.1  656.45
   802.3  659.22   941.5     667  1150.2   669.9  1203.6  674.19  1240.4  680.72
  1269.1  695.46  1326.7  697.38  1359.9  711.65  1380.6  713.83  1414.9   726.4
#Mann= 6 ,-1,0
       0      .1       0  638.35    .045       0   757.3    .025       0
  760.41      .1       0 1261.96     .06       0 1361.18      .1       0
Bank Sta=638.35,757.3
XS Rating Curve= 0 ,0
Exp/Cntr(USF)=0,0
Exp/Cntr=0.3,0.1

Type RM Length L Ch R = 1 ,58818   ,510,500,496
XS GIS Cut Line= 6
 1604287.3998891395083.2009453331604378.77011317395259.791471422
1604586.28314959395660.8487401751604706.91315767395893.989678085
1604885.34587167396238.843319088 1604931.1207145396327.311974168
#Sta/Elev= 30
       0  954.91    63.9  937.97    82.6   922.9   100.6   919.3   117.3  909.28
   154.6  880.39   186.2  864.73   204.2  849.65   235.7  839.43   285.2  815.18
   312.3  797.54   378.5  778.29   420.4  749.54   456.4  734.61   488.3   715.7
   559.5   662.3   589.2  656.78   618.5  638.23  639.68 636.802   671.8  635.35
  756.25636.7605   789.7  646.56   807.7  657.91  1099.7  668.27    1186  678.63
  1277.8  697.03  1316.6  697.28  1330.1  706.23  1366.8  716.77  1400.8  733.13
#Mann= 7 ,-1,0
       0      .1       0  639.68    .045       0  756.25      .1       0
 1006.64     .06       0 1123.52     .05       0 1231.95     .06       0
 1341.17      .1       0
Bank Sta=639.68,756.25
XS Rating Curve= 0 ,0
Exp/Cntr(USF)=0,0
Exp/Cntr=0.3,0.1