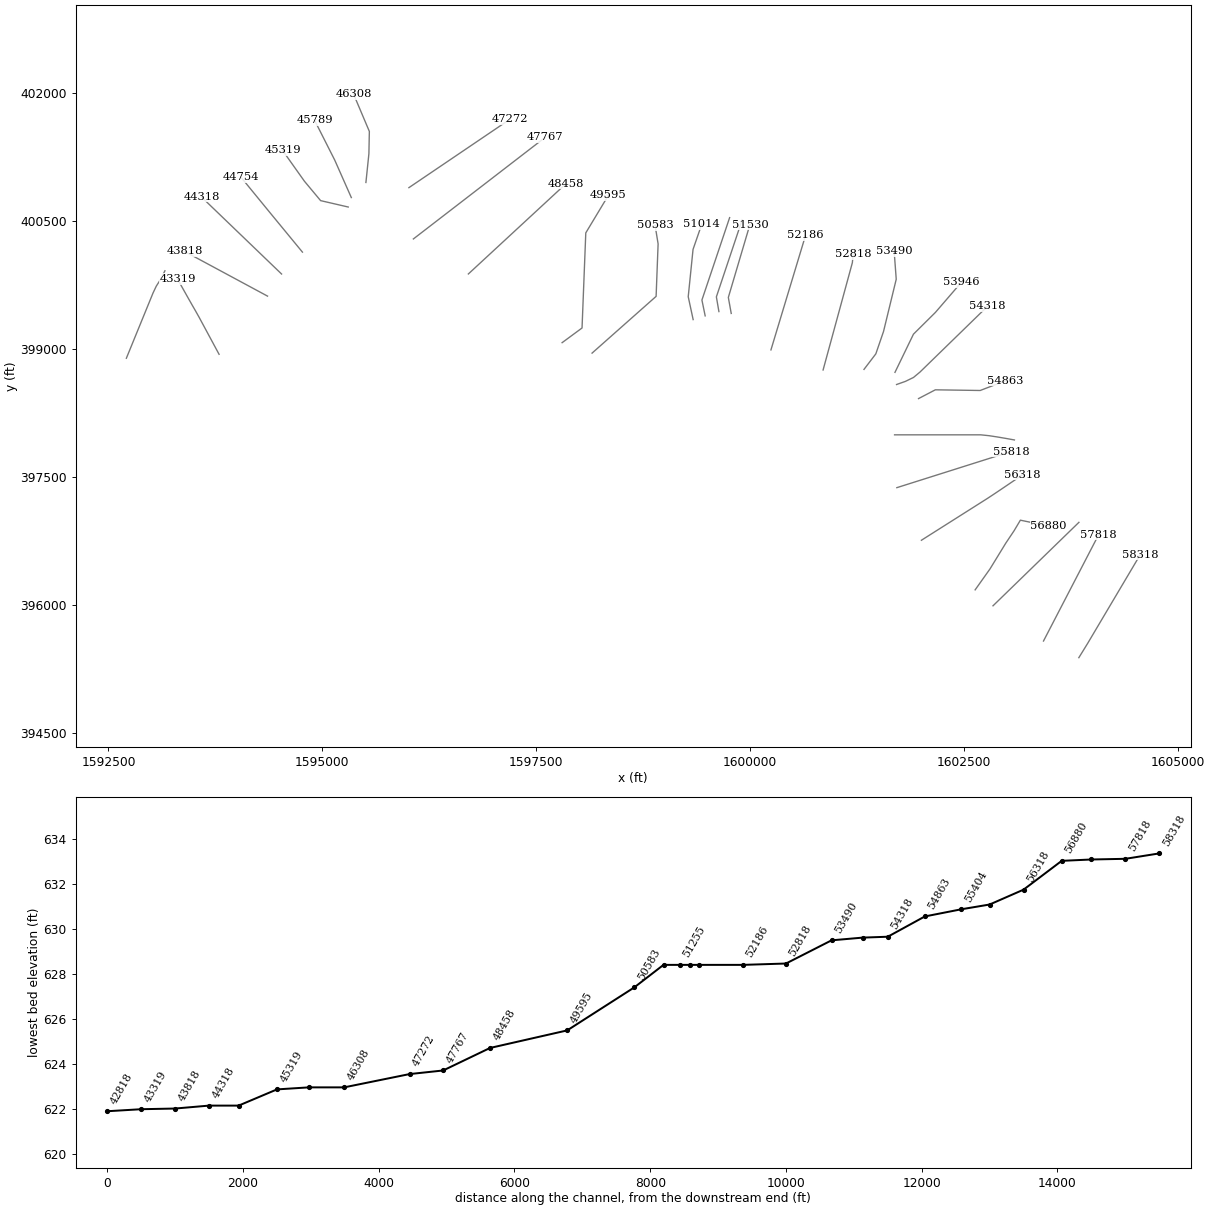
HEC-RAS study FISHINGCK.prj: FISHINGCK

--- FISHINGCK.g01 (geometry) --- (continued)

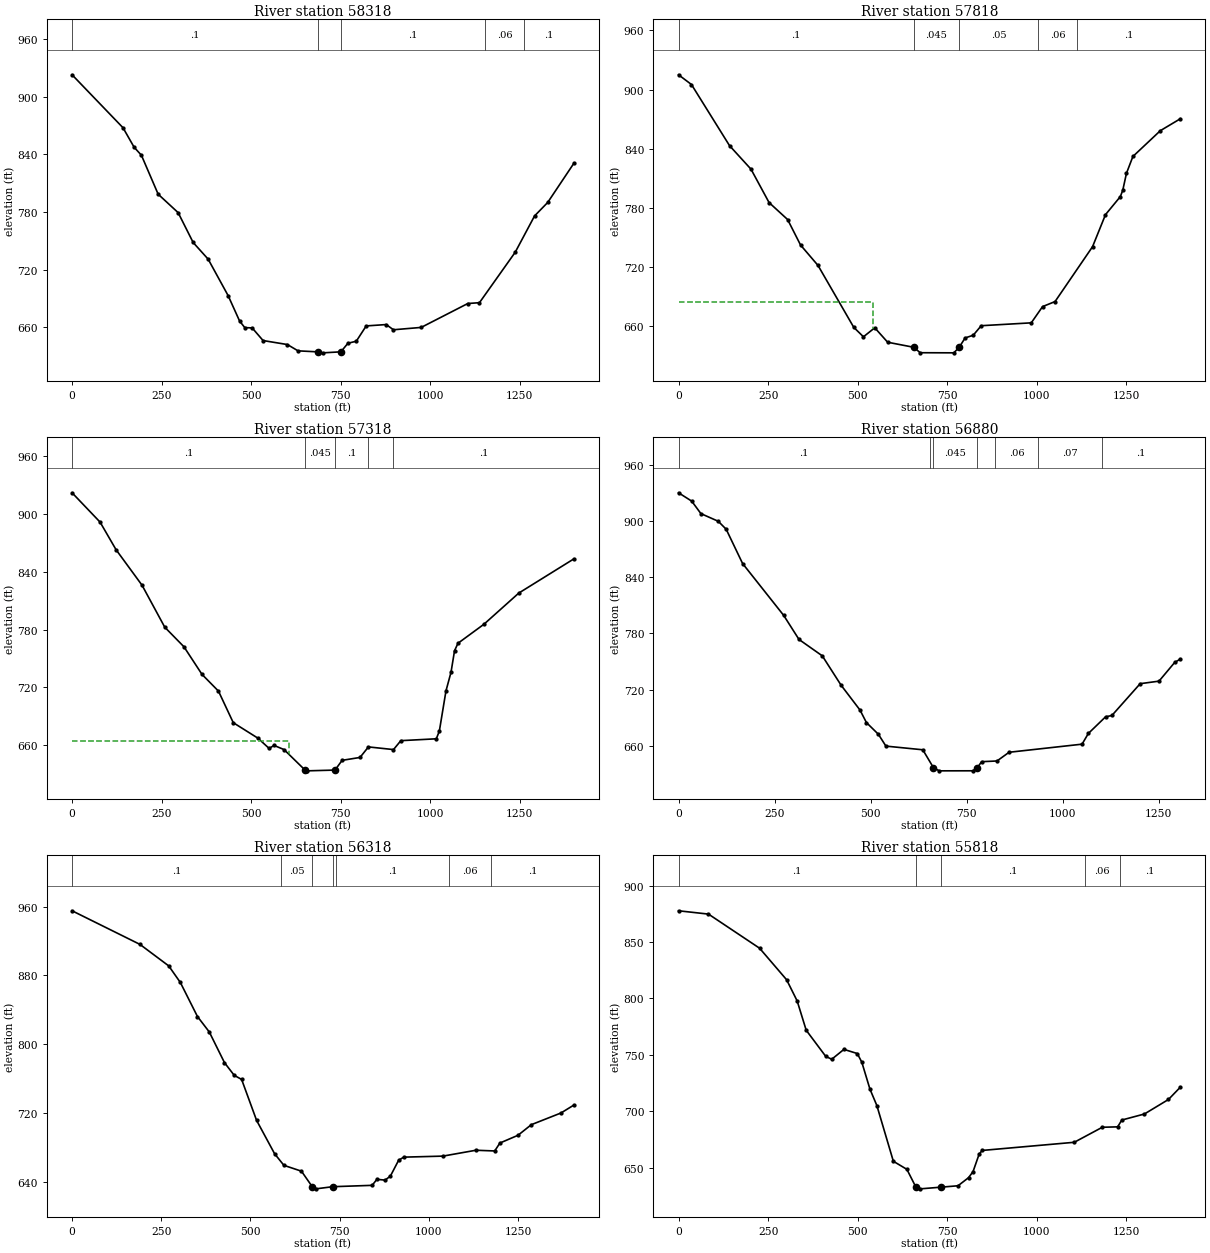
Type RM Length L Ch R = 1 ,58318   ,501.5,500,502.6
XS GIS Cut Line= 6
1603838.90734775395387.4198250921603891.36918509395472.421623588
1603943.34349059395557.0398926731604042.82262234395725.119937092
  1604135.136086395881.0999400911604555.52435283396591.412167758
#Sta/Elev= 30
       0     923   142.3  867.79   173.2  847.55   193.6   839.2   240.4  798.59
   296.2  779.38   338.1   748.3   379.9  730.98   435.7  692.99   467.7  666.54
   482.1   659.7     503  659.28   533.3  646.16   601.2     642   630.9  635.44
   686.7  634.37   700.6  633.36   750.5  634.41   770.3  643.36   793.6  645.45
   821.3   661.4   877.2  662.82   897.3  657.39   974.8  659.84    1105  684.74
  1137.5   685.6  1237.4  738.18  1291.4  775.98  1328.1  790.02  1401.1   830.8
#Mann= 5 ,-1,0
       0      .1       0   686.7    .045       0   750.5      .1       0
 1153.88     .06       0 1262.32      .1       0
Bank Sta=686.7,750.5
XS Rating Curve= 0 ,0
Exp/Cntr(USF)=0,0
Exp/Cntr=0.3,0.1

Type RM Length L Ch R = 1 ,57818   ,515.1,500,485.9
XS GIS Cut Line= 6
1603425.90259634395582.1107086691603562.57522325395846.094432667
1603650.21776451396015.3772305851603724.92988542396159.683700502
1603888.72089642396476.048225254 1604069.9334605396826.060976669
#Sta/Elev= 30
       0  915.09    36.1  905.21   142.4   843.2   202.3  819.36   252.7  785.52
   304.5   768.3   340.6  742.46   389.3  721.76   489.2  658.96   516.2  649.39
   547.8  658.52   583.8  643.87   656.4  638.77   674.7  633.24   768.5  633.12
  783.29638.6292     800  648.24   822.6  650.95     845  660.63   984.7  663.54
  1016.2     680  1051.1  685.12  1155.8  740.78  1191.9  773.27  1233.4  791.58
  1240.2  798.11  1250.4  815.16  1268.4  832.24    1345   858.4  1400.8  870.48
#Mann= 5 ,-1,0
       0      .1       0   656.4    .045       0  783.29     .05       0
 1002.89     .06       0 1113.52      .1       0
#XS Ineff= 2 , 0
          544.07  684.39
Permanent Ineff=
       F       F
Bank Sta=656.4,783.29
XS Rating Curve= 0 ,0
Exp/Cntr(USF)=0,0
Exp/Cntr=0.3,0.1

Type RM Length L Ch R = 1 ,57318   ,424.1,437.7,447.5
XS GIS Cut Line= 6
1602836.10948458395994.672875673 1602978.5891865396133.353372589
1603302.17810626396448.3120602521603490.28468542396631.402245253
1603557.46598151396696.7915501741603839.90603343396971.699464917
#Sta/Elev= 30
       0  922.15    78.2  891.65   122.8  862.97   195.4     826   258.7  782.45
   312.4  762.02   362.8  733.33   408.7  715.97     450  683.15     519  667.01
   550.1  656.39   563.8  659.52   591.7   655.2  650.44633.8678   656.4  633.09
     734  633.88   753.9  644.01   803.8  647.01   827.3  657.96   897.3  655.19
   917.8  664.46  1016.8   666.4  1025.3  674.42  1043.8  716.21  1057.9  735.63
  1067.7  757.94  1077.3  765.71  1149.8  785.49  1247.1  817.89  1400.8  853.43
#Mann= 5 ,-1,0
       0      .1       0  650.44    .045       0     734      .1       0
  825.39     .06       0  895.39      .1       0
#XS Ineff= 2 , 0
          606.15  664.12
Permanent Ineff=
       F       F
Bank Sta=650.44,734
XS Rating Curve= 0 ,0
Exp/Cntr(USF)=0,0
Exp/Cntr=0.3,0.1

Type RM Length L Ch R = 1 ,56880   ,577.5,562.3,548.5
XS GIS Cut Line= 6
1602627.35946625396181.4216010051602800.74429008396426.059235089
1602985.33250358396727.9913739941603082.51931708396873.525531747
1603155.90464433396996.873975135 1603482.4521461396928.775631962
#Sta/Elev= 30
       0  930.57    34.3  921.63    58.2  908.28   103.4  900.07     124  891.54
   166.7  854.88   273.8  799.29   313.5  773.62   374.1  756.08     423  724.69
   472.3  698.06   488.9  684.71   520.1  672.16   539.7  659.49   635.7  655.56
  663.24  636.52   678.4  633.03   765.8  633.08   777.4  636.28   788.7  642.82
   828.8  643.58   860.2   652.9  1050.2  661.57  1066.5  673.02  1111.4  690.85
  1127.8  692.25  1201.4  726.29  1250.4  729.01  1291.2  749.02  1305.9  752.64
#Mann= 7 ,-1,0
       0      .1       0  653.79    .025       0  663.24    .045       0
   777.4      .1       0  823.79     .06       0  936.28     .07       0
 1102.32      .1       0
Bank Sta=663.24,777.4
XS Rating Curve= 0 ,0
Exp/Cntr(USF)=0,0
Exp/Cntr=0.3,0.1

Type RM Length L Ch R = 1 ,56318   ,508.3,500,491.5
XS GIS Cut Line= 6
1601999.42349392396761.8977191751602770.20508884 397251.04536292
1602848.46739951397302.6866638361602929.05942993397356.825335085
 1603095.0361321397469.3598869291603177.94311851397528.990345091
#Sta/Elev= 30
       0  955.07   190.3  915.98   270.9  890.98   303.5  871.69   351.4  832.13
   384.6  814.16   427.2  778.45   454.5  763.73   475.2  758.98   517.2  711.32
   567.6  672.59   593.7  659.08   642.9  652.28  673.24634.1949   683.5  631.75
   730.4  634.23     841  635.82   854.5  642.83   877.3  641.88   892.2  646.58
   915.3  665.01   929.6   668.6  1039.4   669.8  1131.8  676.62  1184.6   675.8
  1199.1  685.01  1249.8  694.01  1287.2  706.35  1370.4  719.97  1406.4  729.15
#Mann= 7 ,-1,0
       0      .1       0  585.39     .05       0  673.24    .045       0
   730.4     .05       0  740.39      .1       0 1056.66     .06       0
 1173.74      .1       0
Bank Sta=673.24,730.4
XS Rating Curve= 0 ,0
Exp/Cntr(USF)=0,0
Exp/Cntr=0.3,0.1

Type RM Length L Ch R = 1 ,55818   ,425.6,414.5,399.9
XS GIS Cut Line= 6
1601712.39322808397377.5126296731601995.77553535 397467.29722701
1602499.23515834 397626.810031341602858.21081834397740.545696259
1602952.79560292397770.5138121691603047.75309017397800.599053845
#Sta/Elev= 30
       0  877.68    83.6  874.73   226.3  844.47   301.7  816.52   331.2  797.69
   356.4  771.74   410.9  748.58   427.7  746.01   461.7  754.76     499  751.09
   511.6  743.43   534.3  719.56   553.6  704.98   599.7  655.53   637.5  648.37
  662.72632.5352   675.3  631.09     734  632.61   780.2  633.81   809.5  640.96
   822.1  646.34   838.9  661.63   847.3  665.13  1104.7  672.37    1183   685.7
  1225.8  686.06  1237.5  692.11  1300.5  697.46  1367.6  710.32  1400.8  721.24
#Mann= 5 ,-1,0
       0      .1       0  662.72    .045       0     734      .1       0
 1133.52     .06       0 1231.95      .1       0
Bank Sta=662.72,734
XS Rating Curve= 0 ,0
Exp/Cntr(USF)=0,0
Exp/Cntr=0.3,0.1

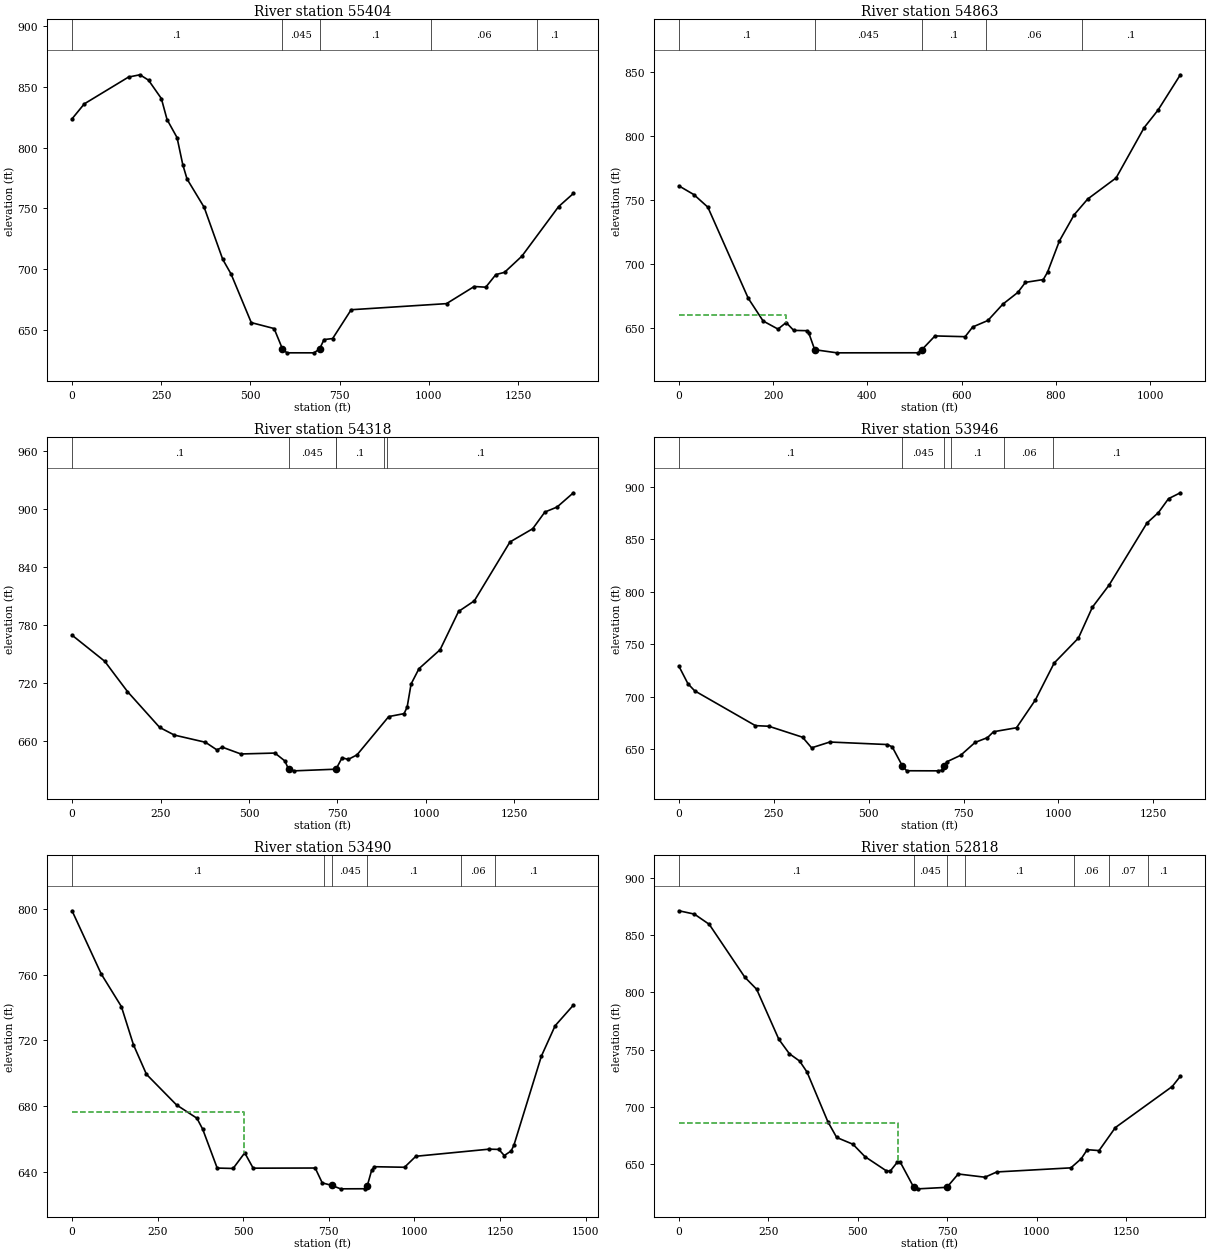
Type RM Length L Ch R = 1 ,55404   ,528.9,540.2,530.8
XS GIS Cut Line= 6
 1601685.7818977397995.8704414571602692.42260094397995.870441457
 1602789.2974072397985.8750546181602887.72700036397970.730071788
1602986.82555545397953.8275465421603086.22233828397935.948645299
#Sta/Elev= 30
       0   823.8    34.3  836.11   158.3  858.21   190.3  860.09   214.3  855.66
   250.3  840.51   266.3  823.16   294.3  808.31   310.3  786.05   322.3  774.17
   370.3  750.82   422.3  707.96   445.7  695.84   502.3   655.8   566.3   650.9
   589.7  634.13   602.3   630.9   678.3  630.88  693.79  634.16   706.3  641.82
   730.3  642.65   782.3  666.41  1049.5  671.44  1127.1  685.56  1159.5  684.99
  1187.8  695.39  1212.1  697.24  1260.8  710.59  1363.6  751.41  1405.1  762.26
#Mann= 5 ,-1,0
       0      .1       0   589.7    .045       0  693.79      .1       0
 1006.64     .06       0 1303.62      .1       0
Bank Sta=589.7,693.79
XS Rating Curve= 0 ,0
Exp/Cntr(USF)=0,0
Exp/Cntr=0.3,0.1

Type RM Length L Ch R = 1 ,54863   ,432.3,545.3,567.2
XS GIS Cut Line= 4
1601965.84981499 398420.197169921602162.31329389398522.850070138
1602686.19572329398514.9364382741602983.66123445398629.606134279
#Sta/Elev= 30
       0   760.9    31.6  754.12    61.2  744.34     147  673.18   178.6  655.43
   210.2   649.1   227.5  654.23   243.5  648.09   271.5  647.85   275.5  646.11
   288.1  633.02   335.5  630.56   507.5  630.61   515.8633.0712   543.5  643.77
   607.5  643.17   623.5  650.75   655.8  655.82   687.5  668.56   719.5  677.78
   735.5  685.59   773.4  687.78   782.4  693.51   807.7  717.99     839  738.38
   867.7  750.68     928  767.15   987.7  806.51    1017  820.11  1064.4   847.7
#Mann= 5 ,-1,0
       0      .1       0   288.1    .045       0   515.8      .1       0
  651.67     .06       0  855.61      .1       0
#XS Ineff= 2 , 0
          226.98  660.24
Permanent Ineff=
       F       F
Bank Sta=288.1,515.8
XS Rating Curve= 0 ,0
Exp/Cntr(USF)=0,0
Exp/Cntr=0.3,0.1

Type RM Length L Ch R = 1 ,54318   ,375.1,372.1,373.5
XS GIS Cut Line= 6
1601709.04841851398584.8573278341601812.43961592398621.505876586
1601906.46075334398667.2032917591601982.37398735398730.351459429
1602423.10440509399160.1747467521602772.41440201399500.795456588
#Sta/Elev= 30
       0  769.64    92.4  742.69   156.6  711.46   247.6  674.44   289.2  666.54
   376.9  659.13   409.1  651.32     425  654.01     477  647.06   573.2     648
   601.4  639.85  611.66631.3486   628.3  629.66   745.7  631.37     763  643.16
   780.2  641.42   805.1  646.13   894.7  685.63   938.1  688.69   946.8  695.45
   957.9  719.25   980.3  735.11  1039.9  754.62    1092  794.08  1136.7   805.1
  1237.3  865.79  1301.5  879.45  1335.9  896.67  1370.3  901.82  1416.5  916.55
#Mann= 6 ,-1,0
       0      .1       0  611.66    .045       0   745.7    .025       0
   746.1      .1       0   881.1     .06       0   891.1      .1       0
Bank Sta=611.66,745.7
XS Rating Curve= 0 ,0
Exp/Cntr(USF)=0,0
Exp/Cntr=0.3,0.1

Type RM Length L Ch R = 1 ,53946   ,426.8,456.2,485.6
XS GIS Cut Line= 4
1601690.57563637398727.2785705011601906.52065417399174.264260744
1602162.49245026399428.2820736631602465.41644059 399780.19339031
#Sta/Elev= 30
       0  729.02    23.6  712.49    41.4  705.74   201.3  672.64   236.8  672.05
   325.6  661.62   349.5  651.52   397.5  657.04   549.4  654.64   562.1  652.36
   588.8  634.25   600.1   629.7     683  629.62   692.7  630.15  699.67  634.36
   705.6  638.17   742.4  644.43   780.4  656.66   813.1  661.24     829  666.83
   889.6  670.63   939.2  697.03   988.8  732.18  1052.7  755.94  1089.6  785.36
  1133.5  806.33  1233.5  865.47  1263.8  875.45  1290.2   888.6  1321.4  894.22
#Mann= 6 ,-1,0
       0      .1       0   588.8    .045       0  699.67    .025       0
  716.42      .1       0  856.42     .06       0  987.04      .1       0
Bank Sta=588.8,699.67
XS Rating Curve= 0 ,0
Exp/Cntr(USF)=0,0
Exp/Cntr=0.3,0.1

Type RM Length L Ch R = 1 ,53490   ,665,671.7,664.6
XS GIS Cut Line= 5
 1601328.5144406 398761.86898516 1601466.8744395398943.694245941
1601556.75766561399205.5279915651601705.26038701399817.124725746
1601680.90563057400145.731110706
#Sta/Elev= 30
       0  798.83    85.2  760.36   144.1   740.5   179.3  717.26   217.3  699.25
   305.1  680.61   364.7   672.5   381.6   665.8   423.9  642.15   470.4  641.91
   504.3  651.41     529  642.08   710.1  642.18   730.7  633.13     759  631.58
   784.2   629.5   854.2  629.55  862.45  631.52   874.8  640.68     883  642.97
     971  642.64  1004.1  649.33  1218.3  653.67  1246.4   653.5  1262.4  649.78
  1282.5  652.59  1290.5   656.1  1370.7   710.3  1410.8   728.8  1464.2  741.39
#Mann= 6 ,-1,0
       0      .1       0  735.31    .025       0     759    .045       0
  862.45      .1       0 1134.68     .06       0 1234.68      .1       0
#XS Ineff= 2 , 0
          501.85  676.26
Permanent Ineff=
       F       F
Bank Sta=759,862.45
XS Rating Curve= 0 ,0
Exp/Cntr(USF)=0,0
Exp/Cntr=0.3,0.1

Type RM Length L Ch R = 1 ,52818   ,633.6,632.4,631
XS GIS Cut Line= 6
1600850.62854743398755.0049534291600876.80270767398851.114013165
1601047.80859926399479.0258150851601115.14376642399726.270727426
1601192.53731242400010.4519175891601202.52416909400110.969433084
#Sta/Elev= 30
       0  871.33      43  868.42    84.5  859.52     184  813.34   217.2  802.77
   279.3  759.04   308.7  746.48   337.4  740.07   358.1  730.45   416.3  687.12
     441  673.35   486.6   667.4   519.8  656.67   579.2  644.34   590.3  643.77
     611   651.9   619.3  651.51   656.6  629.79     669  628.47  749.22629.7869
     781  641.44   855.6  638.62   888.8  643.22    1096   646.8  1125.1  654.81
  1141.7  662.68  1174.8  661.88  1220.4  681.98  1379.5  717.85  1402.2  726.81
#Mann= 7 ,-1,0
       0      .1       0   656.6    .045       0  749.22    .025       0
  800.39      .1       0 1103.52     .06       0 1201.95     .07       0
 1311.17      .1       0
#XS Ineff= 2 , 0
          612.05  685.77
Permanent Ineff=
       F       F
Bank Sta=656.6,749.22
XS Rating Curve= 0 ,0
Exp/Cntr(USF)=0,0
Exp/Cntr=0.3,0.1

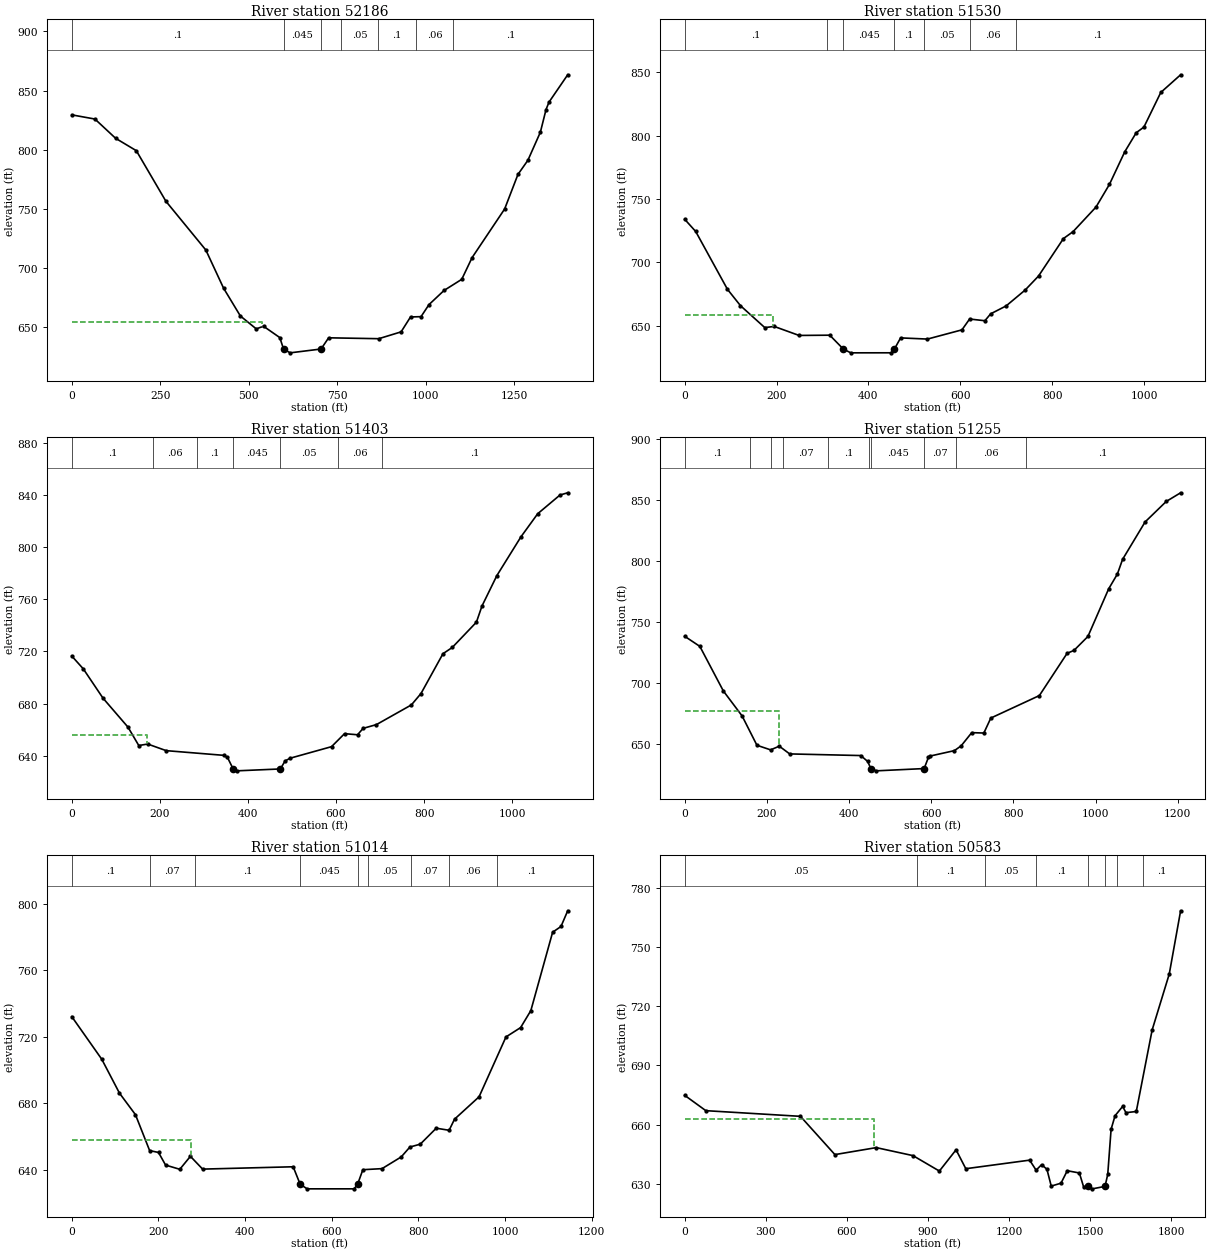
Type RM Length L Ch R = 1 ,52186   ,655,655.4,655.6
XS GIS Cut Line= 6
 1600241.2783398398989.9680264831600270.04403031399085.333321312
 1600327.1246248399274.568179065 1600429.1027673 399612.64755539
1600457.98131847399708.3868652231600645.80607405400331.066722223
#Sta/Elev= 30
       0  829.51    65.4  825.97   123.8  809.71   182.3  799.24   265.9  756.49
   378.7  715.28   428.8  683.03   476.2  659.56   521.1  648.66   541.6  650.88
   587.6  641.29   598.2631.6115   616.9  628.41  704.15  631.65   725.5  641.11
   867.1  640.36   930.2  646.13   956.8  658.73   986.5  658.99    1009  669.17
  1051.4   681.1  1101.5  690.53  1130.7  708.87  1222.7  749.99  1260.3   779.2
  1288.3  791.09  1323.6  814.88  1339.6  834.02    1348  840.28  1400.8  863.38
#Mann= 7 ,-1,0
       0      .1       0   598.2    .045       0  704.15      .1       0
  760.39     .05       0  865.39      .1       0  972.89     .06       0
 1076.64      .1       0
#XS Ineff= 2 , 0
          537.62   654.4
Permanent Ineff=
       F       F
Bank Sta=598.2,704.15
XS Rating Curve= 0 ,0
Exp/Cntr(USF)=0,0
Exp/Cntr=0.3,0.1

Type RM Length L Ch R = 1 ,51530   ,129.3,127.5,125.6
XS GIS Cut Line= 3
1599777.21005259399416.9316981011599743.46127801 399604.14055953
1599995.54983033400457.106570638
#Sta/Elev= 30
       0  733.96      24   724.3    93.1  678.61   121.5  665.66   174.4  648.35
   194.8  649.28     249  642.16   315.8  642.36   345.6  631.33   361.7  628.41
   449.2  628.44  456.54  631.38   470.1  640.22   528.5  639.29   603.6  646.57
   620.3  655.13   653.6  653.78   666.1  659.23   699.8  665.48   741.2  678.02
   770.4  689.12   824.6  718.73   845.5  724.16   895.5  743.62   924.7   761.5
   958.1   787.3   983.1  802.37   999.8  806.81  1036.5  834.16  1079.7  848.14
#Mann= 7 ,-1,0
       0      .1       0  310.23    .025       0   345.6    .045       0
  456.54      .1       0  520.23     .05       0  620.23     .06       0
  720.23      .1       0
#XS Ineff= 2 , 0
          193.34  658.39
Permanent Ineff=
       F       F
Bank Sta=345.6,456.54
XS Rating Curve= 0 ,0
Exp/Cntr(USF)=0,0
Exp/Cntr=0.3,0.1

Type RM Length L Ch R = 1 ,51403   ,149,147.9,148
XS GIS Cut Line= 3
1599633.28838522399438.686253262 1599603.6001399399610.803271384
1599904.98865401400513.105070111
#Sta/Elev= 30
       0  716.49    26.2  706.62    70.9  684.17   127.7   661.9   152.1  647.84
   172.4  648.97   214.4   643.9   345.2   640.3   353.5  638.69   366.4  629.88
   374.7  628.41   473.6  629.86   484.3     636   495.7  638.09   589.8  646.96
   619.3  656.93   648.8  656.08   661.5     661   691.7  663.88   771.1  678.99
   792.9  687.73   842.8  718.27   863.9  723.06   918.7  742.44   931.4  754.89
   965.1  778.16  1019.9  807.97  1057.9  825.66  1108.5  840.01    1126  841.73
#Mann= 7 ,-1,0
       0      .1       0  184.66     .06       0  284.66      .1       0
   366.4    .045       0   473.6     .05       0  604.66     .06       0
  704.66      .1       0
#XS Ineff= 2 , 0
           171.8  656.03
Permanent Ineff=
       F       F
Bank Sta=366.4,473.6
XS Rating Curve= 0 ,0
Exp/Cntr(USF)=0,0
Exp/Cntr=0.3,0.1

Type RM Length L Ch R = 1 ,51255   ,222.2,241.2,251.4
XS GIS Cut Line= 3
 1599472.7934257 399388.358916451599434.77599347399573.872989352
1599758.56237336400538.396882222
#Sta/Elev= 30
       0  738.38    36.9  730.12    94.1  693.67   139.7  673.28   175.8  649.31
   209.1  645.55   230.2  648.56   255.5  642.24   428.5   640.9   445.3  636.08
   453.1630.1721   466.4  628.41   582.7630.2689     593  639.32   597.2   640.5
   656.3  644.92   672.7  648.83   698.5  659.62     728  659.31   744.9  671.54
   863.1  689.93   930.6  724.46   947.3  726.84   981.2  738.22  1031.8  777.21
  1052.9  789.22  1065.6  801.26  1120.4  831.84  1171.8  848.56  1206.8  855.66
#Mann= 10 ,-1,0
       0      .1       0     160     .07       0  209.37      .1       0
  239.37     .07       0  349.37      .1       0  449.37    .025       0
   453.1    .045       0   582.7     .07       0  659.37     .06       0
  829.37      .1       0
#XS Ineff= 2 , 0
          229.03     677
Permanent Ineff=
       F       F
Bank Sta=453.1,582.7
XS Rating Curve= 0 ,0
Exp/Cntr(USF)=0,0
Exp/Cntr=0.3,0.1

Type RM Length L Ch R = 1 ,51014   ,457.3,430.1,431.5
XS GIS Cut Line= 4
1599332.36910483399344.8610187671599274.74477133399612.561856242
 1599331.0194868400166.516086723 1599433.6618799400463.238721652
#Sta/Elev= 30
       0  732.13    69.2  706.47   110.1  686.03     147  673.06   179.7  651.44
   200.2  650.32   216.5  642.72   249.3  640.18   273.8  647.99     302  640.29
     511   641.7   527.1  631.19   543.2  628.41   651.7  628.41  659.64  631.14
   671.8  639.93   716.1  640.58   760.3  647.62   780.4  653.59   804.3  655.31
   841.2  664.93   870.9  663.67   883.4  670.36     940  683.83  1002.1  719.89
  1035.9  725.52  1059.5  735.74  1109.8  782.96  1129.1  786.41  1144.6  795.87
#Mann= 9 ,-1,0
       0      .1       0     180     .07       0  283.83      .1       0
   527.1    .045       0  659.64    .025       0  683.83     .05       0
  783.83     .07       0  870.64     .06       0  980.64      .1       0
#XS Ineff= 2 , 0
          275.48   658.1
Permanent Ineff=
       F       F
Bank Sta=527.1,659.64
XS Rating Curve= 0 ,0
Exp/Cntr(USF)=0,0
Exp/Cntr=0.3,0.1

Type RM Length L Ch R = 1 ,50583   ,980.5,988.7,981.3
XS GIS Cut Line= 4
 1598151.3188736398952.5320237391598899.51123416399616.743928021
1598922.85812623400230.7563345991598887.46526355400448.261373451
#Sta/Elev= 30
       0  674.79    78.3  667.02   428.4  664.15   555.9  644.76   708.9   648.3
   844.9  644.24   942.5  636.42  1004.3  647.19  1040.3  637.61  1276.5  641.95
  1300.5  636.88  1320.9  639.66  1340.5  637.34  1356.5  628.81  1392.6  630.27
  1415.8  636.59  1460.6  635.45  1476.6  628.27  1492.6  628.65  1508.6  627.41
 1555.55  628.65  1565.6  634.76    1578  657.59  1592.7  664.48  1620.8  669.17
    1633  666.01  1671.2   666.6  1729.9   707.9  1793.2  736.24  1835.3  768.31
#Mann= 8 ,-1,0
       0     .05       0     860      .1       0 1110.48     .05       0
 1300.48      .1       0  1492.6    .045       0 1555.55     .05       0
 1600.48     .06       0 1694.94      .1       0
#XS Ineff= 2 , 0
          699.88     663
Permanent Ineff=
       F       F
Bank Sta=1492.6,1555.55
XS Rating Curve= 0 ,0
Exp/Cntr(USF)=0,0
Exp/Cntr=0.3,0.1

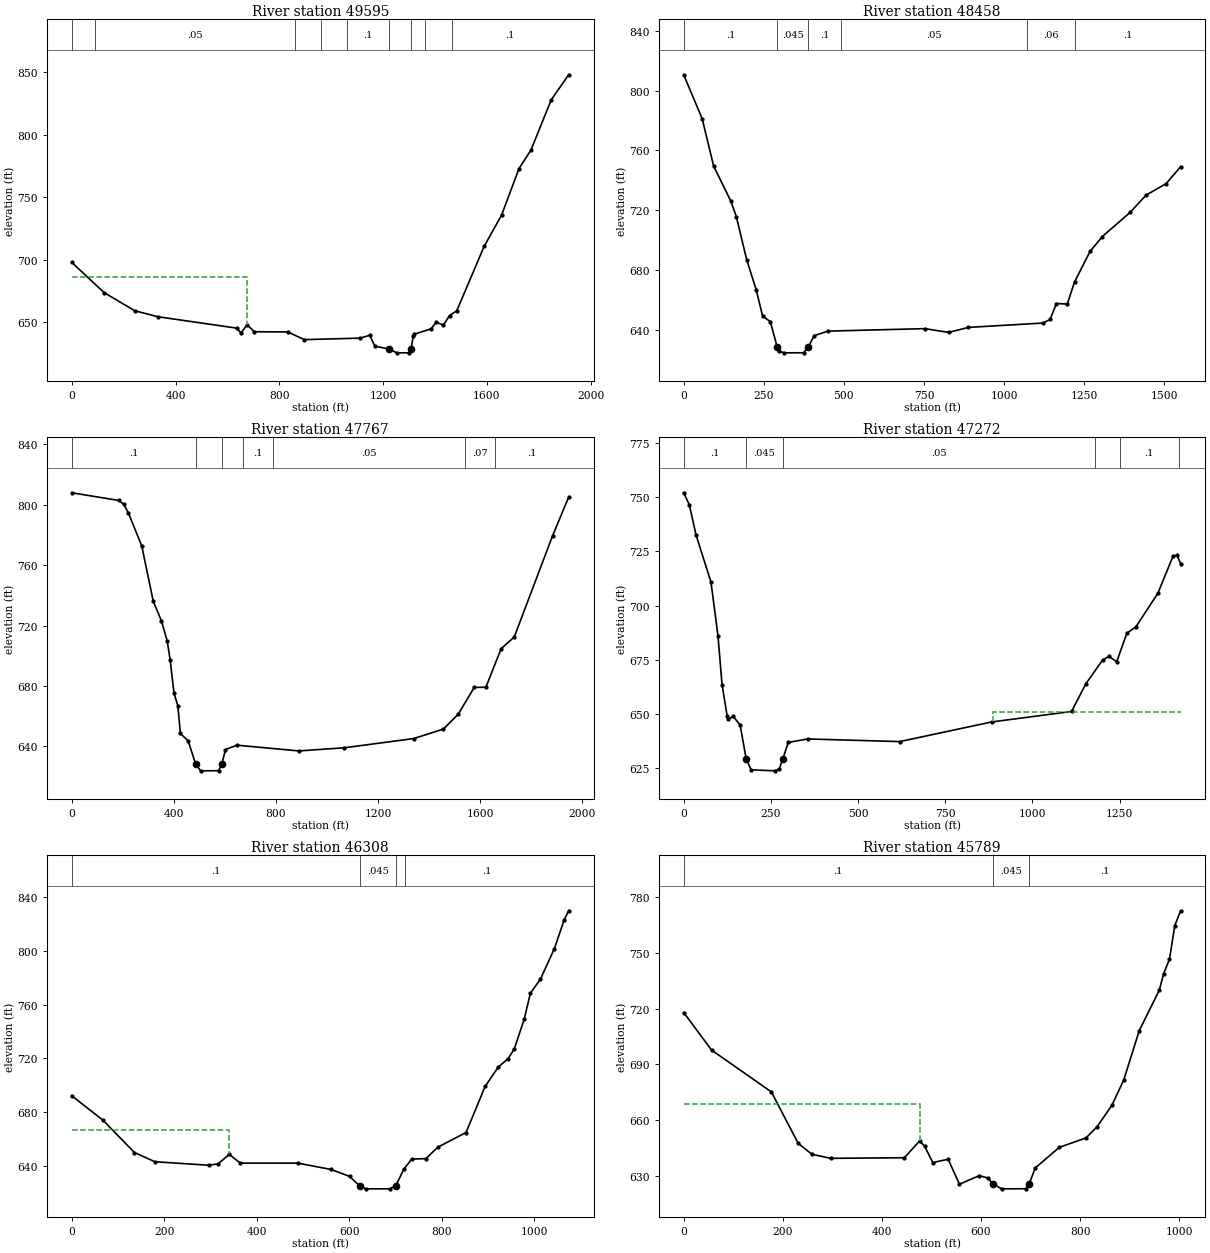
Type RM Length L Ch R = 1 ,49595   ,1177.9,1136.9,1101.4
XS GIS Cut Line= 4
1597801.02569415399074.673194624 1598034.0437919399246.559365766
1598077.81358171400359.9125574251598341.20158534400798.282253562
#Sta/Elev= 30
       0  697.79   124.4  673.68   242.4  659.18   331.6  654.37   635.8  645.25
   651.8  641.34   675.8   647.9   703.9  642.36     832  642.24     896  636.06
  1112.2  637.27  1148.2  639.54  1168.2  630.81  1224.3  628.48  1252.3   625.5
  1300.3  625.53 1307.62  628.47  1316.3  639.14  1320.3  640.47  1384.4  644.64
  1404.5  649.95  1432.5  647.71  1455.8  655.34  1483.8  659.13  1589.5  710.75
  1656.8  735.74  1723.6  772.84  1770.3  787.87  1847.8  827.82  1915.2  847.88
#Mann= 9 ,-1,0
       0      .1       0      90     .05       0  859.56      .1       0
  959.56     .05       0 1059.56      .1       0  1224.3    .045       0
 1307.62      .1       0 1359.56     .06       0 1463.77      .1       0
#XS Ineff= 2 , 0
          676.51   686.4
Permanent Ineff=
       F       F
Bank Sta=1224.3,1307.62
XS Rating Curve= 0 ,0
Exp/Cntr(USF)=0,0
Exp/Cntr=0.3,0.1

Type RM Length L Ch R = 1 ,48458   ,695.3,691.2,686.7
XS GIS Cut Line= 2
1596705.64674427399878.8943847551597843.31764083400932.933867756
#Sta/Elev= 30
       0   810.6    57.9  781.05    93.5  749.49   147.3  726.07   164.2  715.82
   196.6  686.97   226.1  666.97   246.3  649.27   270.6  645.54   291.6  628.76
   297.8  625.77   314.2  624.72   374.2  624.77  389.36  628.76   406.9  636.18
   450.5  639.25     753   640.9   826.8  638.38   888.9  641.73  1121.2  644.63
  1143.6  647.04  1163.4  657.69  1197.2  657.34    1220  672.14  1268.4  692.51
  1306.6  702.46  1393.9  718.66  1442.9   730.1  1505.9  737.83  1550.9  749.13
#Mann= 6 ,-1,0
       0      .1       0   291.6    .045       0  389.36      .1       0
     490     .05       0    1070     .06       0    1220      .1       0
Bank Sta=291.6,389.36
XS Rating Curve= 0 ,0
Exp/Cntr(USF)=0,0
Exp/Cntr=0.3,0.1

Type RM Length L Ch R = 1 ,47767   ,497.7,494.9,491.5
XS GIS Cut Line= 2
1596063.26101386400288.8220541871597604.95099154401479.097404601
#Sta/Elev= 30
       0  807.97     183  802.91   203.2  800.46   222.1  794.49     274   772.8
   319.4  735.96   351.2  723.18     374  709.72   385.4  697.38   400.3  675.39
   415.5   666.9   425.6  648.49   455.9  643.58  485.71628.1165   505.2  623.72
   575.5  623.82     588628.1364   602.4  637.85   647.5  640.71   889.7  636.92
  1067.4  638.98  1340.2  645.11  1456.5  651.38  1514.7  661.26  1577.4  678.99
  1623.2  679.11  1682.9  704.66  1734.4  712.44  1884.6  779.48  1947.7   805.1
#Mann= 7 ,-1,0
       0      .1       0  485.71    .045       0     588    .025       0
     670      .1       0     790     .05       0    1540     .07       0
    1660      .1       0
Bank Sta=485.71,588
XS Rating Curve= 0 ,0
Exp/Cntr(USF)=0,0
Exp/Cntr=0.3,0.1

Type RM Length L Ch R = 1 ,47272   ,908.4,963.5,1020.9
XS GIS Cut Line= 2
1596010.87714496400889.1684315211597190.03328526401688.818344418
#Sta/Elev= 30
       0  752.12      16  746.63    35.3  732.65    78.2  710.81    98.2  686.04
   109.9  663.47   124.3  649.13   127.2  647.31   141.7  648.74   161.7  644.84
  179.17  629.01   193.4  624.03   262.5  623.56     274  624.43   283.9 629.045
     300   636.7   355.2   638.3   619.6  637.09   882.6  646.15  1112.1  651.01
  1153.4  663.89  1201.4  674.85  1219.4  676.44  1241.7  674.05  1270.5  687.15
  1296.8  690.17  1359.8  705.73  1402.8  722.72  1414.5  723.29  1424.7  719.39
#Mann= 6 ,-1,0
       0      .1       0  179.17    .045       0   283.9     .05       0
    1180     .08       0    1250      .1       0    1420     .06       0
#XS Ineff= 2 , 0
                          886.23          650.82
Permanent Ineff=
       F       F
Bank Sta=179.17,283.9
XS Rating Curve= 0 ,0
Exp/Cntr(USF)=0,0
Exp/Cntr=0.3,0.1

Type RM Length L Ch R = 1 ,46308   ,517,519.4,521.9
XS GIS Cut Line= 4
1595508.71872879400949.8561632521595543.51840879401286.398736296
1595548.87281858401547.4932703071595363.93678613401985.055480365
#Sta/Elev= 30
       0  692.13      67  674.12   135.4  649.99   179.6  643.13   296.3  640.52
   316.4  641.56   340.5  648.59   364.5   642.1   488.5  642.09   560.5  637.38
   600.6  632.25  622.41  625.22   635.4  622.97   687.5  622.98   700.5  625.26
   717.9   637.5     735  645.14   765.7  645.41   791.7     654   852.5  664.84
   893.9  699.21     922  713.39   943.7   719.9   956.7  726.86   978.4  749.24
   991.6   768.4  1013.2  778.74  1043.6  801.65  1064.8     823  1074.5  829.76
#Mann= 4 ,-1,0
       0      .1       0  622.41    .045       0   700.5    .025       0
  719.49      .1       0
#XS Ineff= 2 , 0
          339.48  667.03
Permanent Ineff=
       F       F
Bank Sta=622.41,700.5
XS Rating Curve= 0 ,0
Exp/Cntr(USF)=0,0
Exp/Cntr=0.3,0.1

Type RM Length L Ch R = 1 ,45789   ,465.7,470,474.7
XS GIS Cut Line= 3
1595338.10365841400773.2581378721595144.23126818401211.929211902
1594908.40906416401678.931219881
#Sta/Elev= 30
       0   717.9    56.1  697.71   176.9  675.16     231  647.49   258.8  641.58
   296.6  639.39   445.3  639.72   475.9  648.69   486.1  645.99   502.7  637.12
   533.7   638.9   556.5  625.47   596.8   630.1   614.7  628.71  623.66  625.73
   641.6  622.97   690.9  623.02   697.5  625.75   709.4  634.21   758.1  645.32
   811.9  650.37   834.5  656.48   864.2  667.98   888.1  681.59   919.4  708.15
   959.8  729.91   968.7  738.83   980.4  746.62   991.1  764.67  1002.8  772.68
#Mann= 3 ,-1,0
       0      .1       0  623.66    .045       0   697.5      .1       0
#XS Ineff= 2 , 0
          476.75  668.79
Permanent Ineff=
       F       F
Bank Sta=623.66,697.5
XS Rating Curve= 0 ,0
Exp/Cntr(USF)=0,0
Exp/Cntr=0.3,0.1

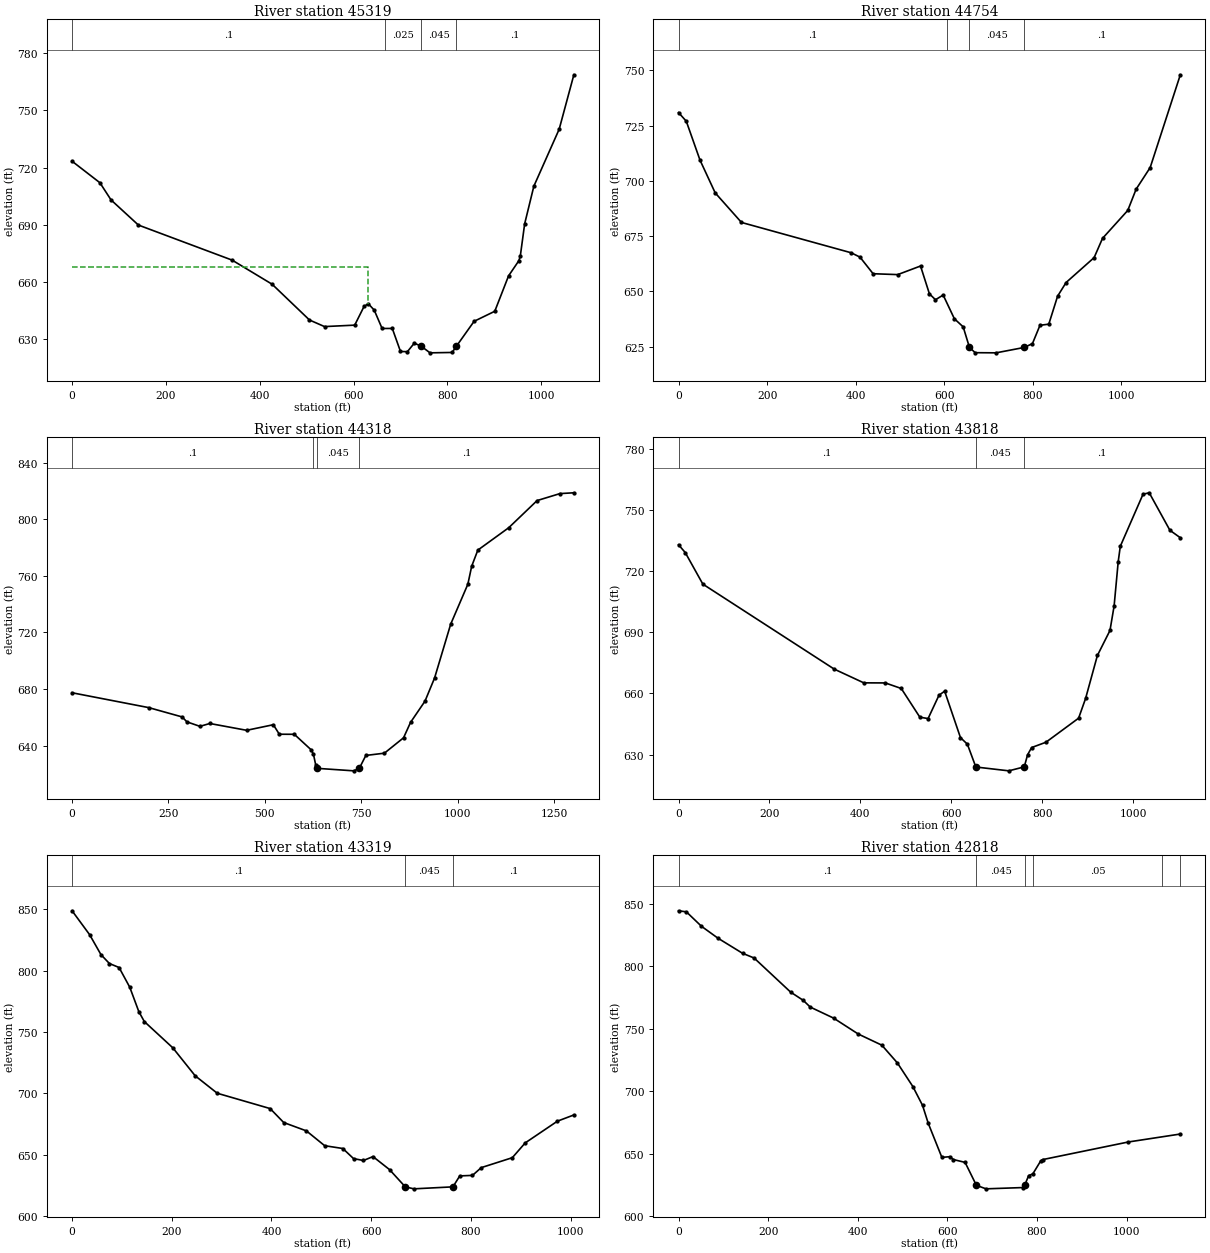
Type RM Length L Ch R = 1 ,45319   ,565.8,565,563.1
XS GIS Cut Line= 4
1595301.89699295400662.5817707231594979.34566616400737.362530968
1594790.33318969400964.3577942911594534.07458428401326.146041146
#Sta/Elev= 30
       0  723.32    59.3  712.05    83.1  703.03   141.4  689.86   341.3  671.47
   426.5  658.84   506.1   640.1   538.2  636.64   602.6   637.4   622.5   647.2
   631.6  648.61   644.2  645.27     661  635.64   682.7  635.67   700.2  623.59
   714.9  623.49   729.6  627.95   744.4  626.36   763.1  622.88   810.3  623.08
  819.59  626.42   857.1   639.4   901.2  644.67   930.6  663.23   952.5  671.16
   955.6  673.56   964.9   690.5   984.5  710.22  1038.5   740.1  1069.8  768.63
#Mann= 4 ,-1,0
       0      .1       0  666.49    .025       0   744.4    .045       0
  819.59      .1       0
#XS Ineff= 2 , 0
          630.26  667.98
Permanent Ineff=
       F       F
Bank Sta=744.4,819.59
XS Rating Curve= 0 ,0
Exp/Cntr(USF)=0,0
Exp/Cntr=0.3,0.1

Type RM Length L Ch R = 1 ,44754   ,430.8,435.8,446.5
XS GIS Cut Line= 3
1594766.89137109400134.7508815831594388.18260455400595.894037308
1594049.04948463401011.289274576
#Sta/Elev= 30
       0  730.86    17.5  726.94    48.5  709.33    82.8  694.52   142.1  681.15
   389.8  667.43   409.7  665.46   439.3  657.95   494.9  657.55   546.4  661.44
   566.5  648.84   580.2  646.18   597.5  648.31   622.8  637.58   642.7  633.91
   656.9   624.6   669.8  622.23     717  622.16   780.3  624.59   799.1  626.33
   816.1  634.62     836  635.13   855.9   647.8   875.1  653.98   938.4  665.25
   957.3  673.94  1014.3  686.58  1033.2   696.2  1064.9  705.97    1133  747.95
#Mann= 4 ,-1,0
       0      .1       0  606.72    .025       0   656.9    .045       0
   780.3      .1       0
Bank Sta=656.9,780.3
XS Rating Curve= 0 ,0
Exp/Cntr(USF)=0,0
Exp/Cntr=0.3,0.1

Type RM Length L Ch R = 1 ,44318   ,483.8,500,513.2
XS GIS Cut Line= 6
1594523.09559885399878.4101869171594239.28350243400151.901437834
 1594171.7760915400216.953473091 1593728.4777655400644.131096423
1593657.59470518400712.4360779231593586.14963809400781.283381179
#Sta/Elev= 30
       0  677.33   199.1  666.82   285.5  660.24   297.8  656.77   331.6   653.6
   357.2  655.62   452.7   650.8   521.9  654.75   537.4  648.03   576.3  647.98
   620.3  636.93     626   633.8   631.8  626.32   635.7623.9189   730.6  622.16
   744.8  623.91   761.8  633.04   809.9  634.64   859.6  645.52   877.7  656.39
   915.2  671.42     940  687.75   981.8   725.8  1026.3  754.02  1036.2  766.71
  1052.2  778.14  1132.3  793.95  1205.9  813.15  1265.1  818.07  1301.2  818.65
#Mann= 4 ,-1,0
       0      .1       0  625.39    .025       0   635.7    .045       0
   744.8      .1       0
Bank Sta=635.7,744.8
XS Rating Curve= 0 ,0
Exp/Cntr(USF)=0,0
Exp/Cntr=0.3,0.1

Type RM Length L Ch R = 1 ,43818   ,518.4,499.5,462.9
XS GIS Cut Line= 6
1594359.17433876399619.6105076671594184.17501684399713.992208675
1594097.53477018399760.7191493361593555.69038142400052.949207917
1593473.17578268400097.4517435881593387.91086134400143.436887845
#Sta/Elev= 30
       0  732.87    14.8  729.04    53.5  713.57   342.5  671.89   407.4  665.17
   454.7  665.13   489.8  662.41   530.7  648.33   548.8  647.66   572.8  659.12
   585.2  661.08     620  638.32   635.2   635.1   653.8  623.91   726.3  622.03
   760.3  623.98   767.6   629.9   776.5  633.45   807.9  636.04   879.8  647.85
   895.2  657.54   921.1  678.58   948.8  690.85   957.9  702.88   966.9  724.58
   971.5  732.13  1021.5  757.66  1035.1  758.36  1080.6  739.97  1103.5  736.31
#Mann= 3 ,-1,0
       0      .1       0   653.8    .045       0   760.3      .1       0
Bank Sta=653.8,760.3
XS Rating Curve= 0 ,0
Exp/Cntr(USF)=0,0
Exp/Cntr=0.3,0.1

Type RM Length L Ch R = 1 ,43319   ,529.9,500.5,438.1
XS GIS Cut Line= 6
1593792.78997284398938.6000586751593561.64837475399368.185157508
1593518.98376192399444.4373015911593481.47793142399509.349573344
1593432.20506409399596.4009084251593306.73385835399820.161615759
#Sta/Elev= 30
       0  848.79    35.2  829.31      58     813    74.9  805.78    94.3  802.52
   115.8   786.4   133.9  766.57   144.9  758.47   202.1  737.02     247  714.19
   291.3  699.96   397.4  687.46   424.6  676.08   470.1  669.27   506.8  657.18
   543.2   654.9   564.7  646.66   584.6  645.12   603.7  648.31   636.9  637.68
   668.5 623.619   685.8     622   764.1  623.62   777.8  632.55   803.3  632.97
   820.9   639.3   883.2   647.4   909.1  659.47   973.7  677.19  1006.7  682.26
#Mann= 3 ,-1,0
       0      .1       0   668.5    .045       0   764.1      .1       0
Bank Sta=668.5,764.1
XS Rating Curve= 0 ,0
Exp/Cntr(USF)=0,0
Exp/Cntr=0.3,0.1

Type RM Length L Ch R = 1 ,42818   ,526.4,500,450.3
XS GIS Cut Line= 6
1592709.52311051398892.3652430031592784.66042742399076.449520499
1593021.43751292 399656.550722511593058.88330418399735.774645418
1593110.53018251399817.2872776691593160.11604135399916.012802005
#Sta/Elev= 30
       0  844.47    17.5  843.62    51.2  832.05      88  822.53   142.8  810.46
   168.7  806.66   250.3  779.34   278.2  772.82     294  767.39     346  758.58
     401  745.85   453.8  736.89   488.4  722.73     523  703.79   544.6  688.73
   557.4  674.32   587.8  647.07     605  647.64   613.7  645.33   639.6  643.08
   664.8  624.73   686.3  621.91     769  622.94   772.5624.6315   781.4  632.49
   790.8  633.89   808.1  644.09   812.4  645.29  1003.9  659.41    1120  665.78
#Mann= 6 ,-1,0
       0      .1       0   664.8    .045       0   772.5      .1       0
  790.39     .05       0 1079.52      .1       0 1119.52     .05       0
Bank Sta=664.8,772.5
XS Rating Curve= 0 ,0
Exp/Cntr(USF)=0,0
Exp/Cntr=0.3,0.1