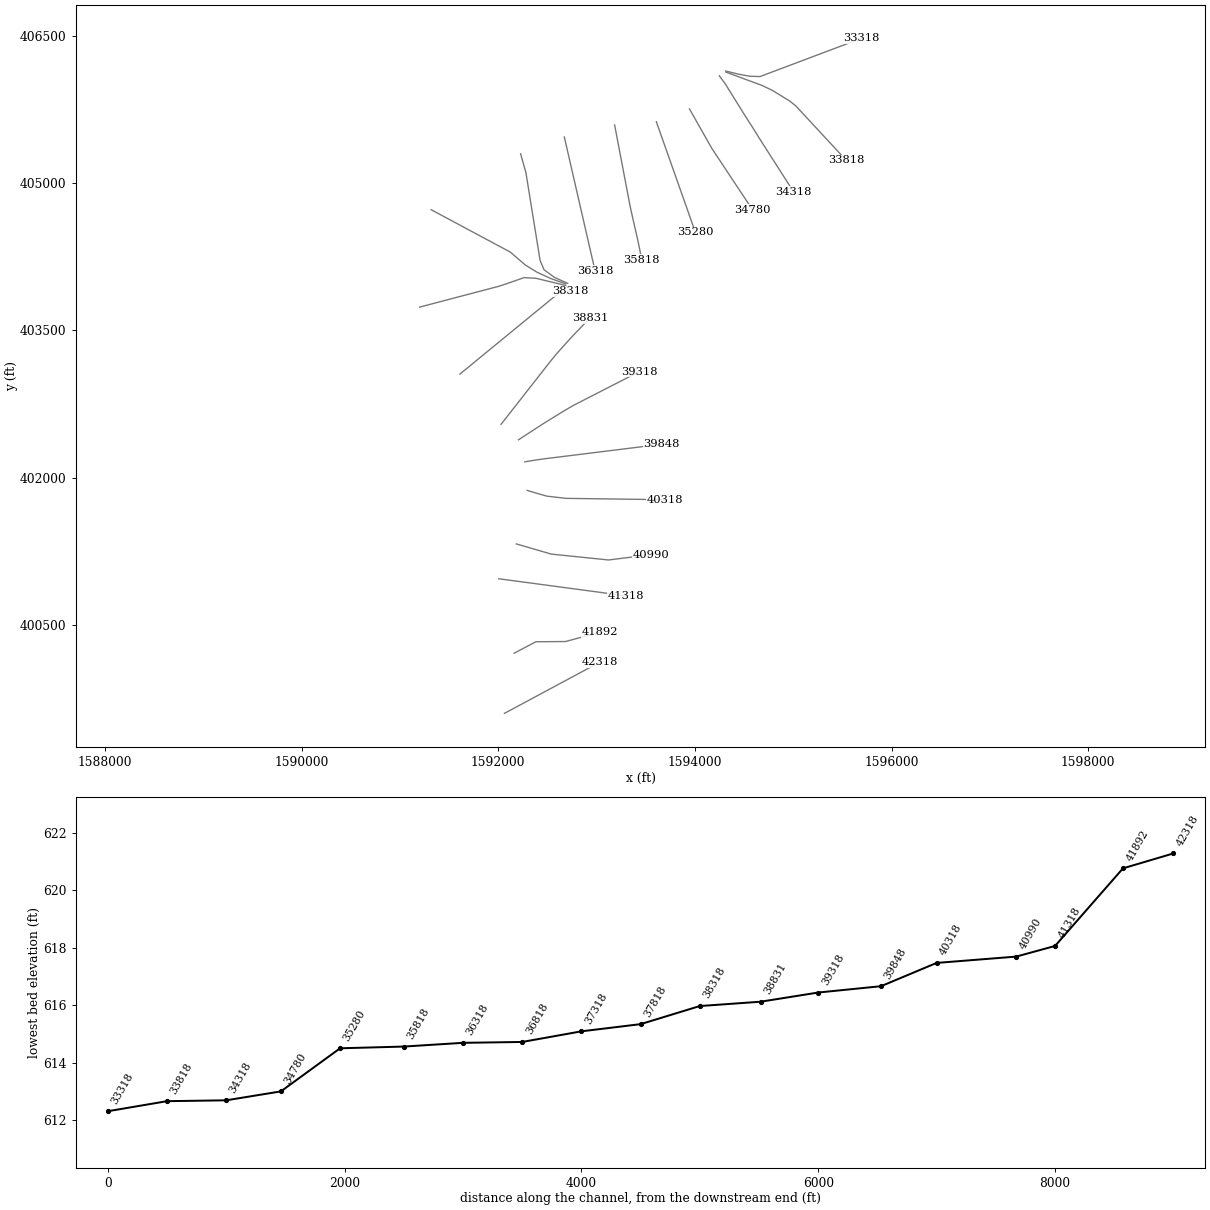
HEC-RAS study FISHINGCK.prj: FISHINGCK

--- FISHINGCK.g01 (geometry) --- (continued)

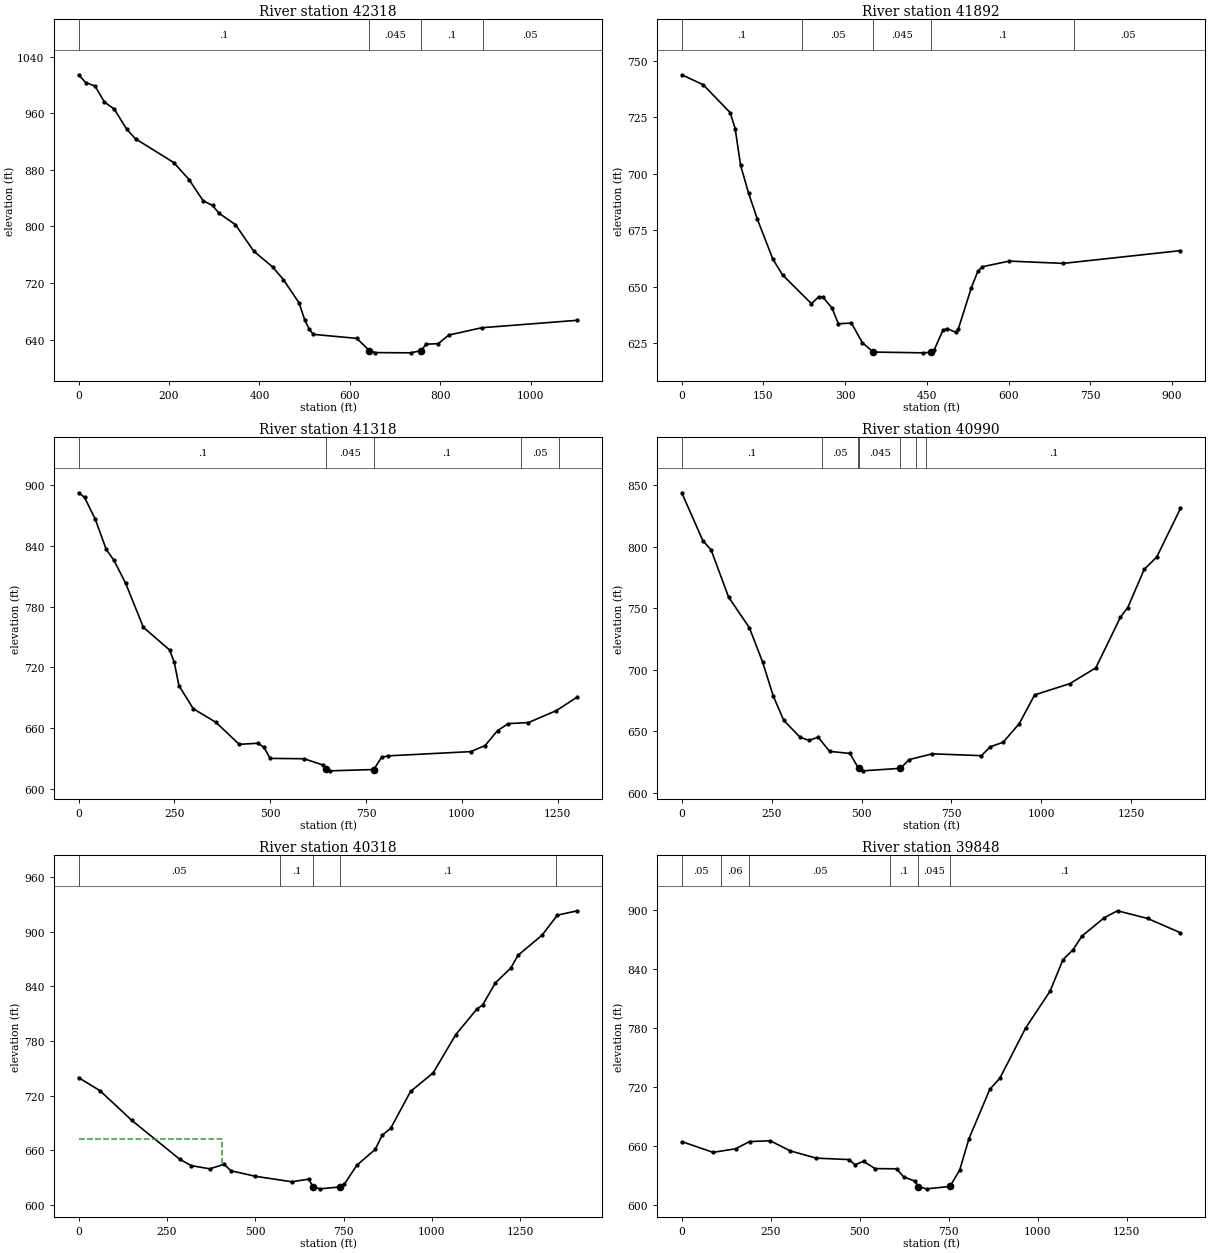
Type RM Length L Ch R = 1 ,42318   ,455.8,426.3,403.7
XS GIS Cut Line= 6
1592062.53129426399601.0239306691592150.29391401399648.138337761
1592324.44185968399741.6286363451592492.39526393399831.792826086
1592635.56820592399908.6545490031593034.80133134400122.979251593
#Sta/Elev= 30
       0 1014.62    15.4 1003.67    36.3  998.69    56.9   976.1      79  965.93
   106.2  937.65   125.8  924.03   210.4  890.48   244.2  866.35   275.5  836.37
   296.2  829.75   310.5  818.75   346.8  802.65   387.7  764.92   429.2  742.77
   452.8  724.99   487.6  692.05     500  668.21   510.3  654.51   519.4  647.42
   615.3  641.73   643.4624.4804   655.6  621.61   734.7  621.28   757.4624.4213
     769  633.53   795.5  634.26     819  646.44   891.6  656.78  1103.5  667.32
#Mann= 4 ,-1,0
       0      .1       0   643.4    .045       0   757.4      .1       0
  895.39     .05       0
Bank Sta=643.4,757.4
XS Rating Curve= 0 ,0
Exp/Cntr(USF)=0,0
Exp/Cntr=0.3,0.1

Type RM Length L Ch R = 1 ,41892   ,582.8,573.7,571.6
XS GIS Cut Line= 4
1592161.33752286400213.4269470311592382.65993848400329.896026855
1592683.61257011400332.3040400721593035.86186848400426.857032557
#Sta/Elev= 30
       0  743.91    39.3  739.51      89  727.13    98.1  720.05     108  703.83
   122.8  691.42   138.7  680.04   167.2  662.31     185  655.31   238.2  642.54
   251.6  645.63   259.6  645.32   275.6  640.71   287.6  633.66   311.6  633.93
   331.6  625.25   351.8   621.1   443.6  620.76   457.5621.0324   463.6   622.1
   479.6  630.76   487.6  631.51   503.6  629.79   507.6  631.16   531.9  649.68
   543.6   656.8   551.4  658.86   601.3  661.39   700.7  660.38   915.8  666.03
#Mann= 5 ,-1,0
       0      .1       0     220     .05       0   351.8    .045       0
   457.5      .1       0  721.06     .05       0
Bank Sta=351.8,457.5
XS Rating Curve= 0 ,0
Exp/Cntr(USF)=0,0
Exp/Cntr=0.3,0.1

Type RM Length L Ch R = 1 ,41318   ,326.1,327.9,330.5
XS GIS Cut Line= 6
1592004.91395542400971.105836168 1592201.9768815 400944.67117776
1592748.64278293 400871.33897534 1592909.6998755400849.733703583
1593098.63256851400824.3899222611593294.53440768400798.110775337
#Sta/Elev= 30
       0  892.29    15.3  887.83    43.6  865.98    71.8  836.47      92  825.74
   122.6  803.05   168.7  759.68   237.3  737.24   249.4  725.16   261.5  702.16
     299  679.32   358.4  665.81   418.9  644.22   467.3  645.25   483.5   641.3
   499.6  630.35   588.7  629.98   636.9  623.86   646.5 619.421     657  618.06
   769.8  619.37   790.2  631.28   806.4  632.82  1022.9  637.01  1060.6  643.04
  1092.9  657.78  1121.2  664.63  1173.6  665.69  1246.3  677.46  1301.2  690.91
#Mann= 5 ,-1,0
       0      .1       0   646.5    .045       0   769.8      .1       0
 1153.52     .05       0 1251.95      .1       0
Bank Sta=646.5,769.8
XS Rating Curve= 0 ,0
Exp/Cntr(USF)=0,0
Exp/Cntr=0.3,0.1

Type RM Length L Ch R = 1 ,40990   ,669.3,672.1,661.4
XS GIS Cut Line= 4
1592183.86159146401325.5314035521592539.39696307401221.963953952
1593121.48925823401162.2318222031593549.56796212401215.627922286
#Sta/Elev= 30
       0  844.07    58.6  805.14    81.7  797.52   130.1  759.21   188.1  734.16
   225.2  705.97   254.4  678.65   283.6  658.73   329.4  644.98   354.4  642.48
   379.1   645.1   411.2  633.52   467.5  631.85   491.7  619.72   503.7  617.69
   608.3  619.75   632.4  626.84   696.8  631.54   833.4  630.05   857.9  637.28
   893.8  640.97   938.6  656.13   981.4  679.54    1079  688.65  1151.6  701.57
  1220.1  742.89  1240.3  750.63    1286  781.65  1320.9   791.8  1386.9  831.31
#Mann= 7 ,-1,0
       0      .1       0  390.31     .05       0  490.31      .1       0
   491.7    .045       0   608.3      .1       0  650.31    .025       0
  680.31      .1       0
Bank Sta=491.7,608.3
XS Rating Curve= 0 ,0
Exp/Cntr(USF)=0,0
Exp/Cntr=0.3,0.1

Type RM Length L Ch R = 1 ,40318   ,463.9,469.8,475.6
XS GIS Cut Line= 6
 1592294.4255155401870.3005600871592395.26520884 401839.87870492
1592494.72760834401811.7330919211592689.75674585 401789.28858301
1593302.20138709401781.0674708341593696.30657001401775.776799008
#Sta/Elev= 30
       0  739.57    60.3  725.31   150.8  692.56   286.6  649.83   318.8  642.95
   371.1  639.47   411.4  644.39   431.4  637.31   499.4  631.31   603.4  625.23
   651.4  628.14   663.5619.5145   683.4  617.47   739.6 619.543   751.4  622.26
   787.4   643.4   839.4  660.78   859.4  676.46   883.4  684.01   939.4  724.47
  1003.4  744.84  1067.4  786.85  1127.4  815.08  1143.4  819.43  1179.4  843.61
  1223.4  860.12  1243.4     874  1311.5  896.04    1355  918.15  1411.7  922.94
#Mann= 5 ,-1,0
       0     .05       0  568.76      .1       0   663.5    .045       0
   739.6      .1       0 1352.04     .06       0
#XS Ineff= 2 , 0
          407.06   672.1
Permanent Ineff=
       F       F
Bank Sta=663.5,739.6
XS Rating Curve= 0 ,0
Exp/Cntr(USF)=0,0
Exp/Cntr=0.3,0.1

Type RM Length L Ch R = 1 ,39848   ,515.9,530.2,549.5
XS GIS Cut Line= 6
1592270.25408067402161.1365817621592368.58951393402177.557808755
1592466.82520984402191.6112583411593175.44485559402279.609113841
1593268.48010259 402291.162240341593659.61645943402339.734649761
#Sta/Elev= 30
       0  664.64      88  653.73   151.7  657.36   190.3  664.72   248.6  665.45
   304.9  655.21   377.6  647.84   470.3  646.38   486.4  641.09   510.6  644.66
   542.8  637.22   603.3     637   623.5  628.79   655.7  624.42   663.8  618.92
   687.9  616.66   753.3  619.08   780.7  635.78   806.8  667.68   865.3  717.78
   893.5  728.99   966.1  780.13  1034.6  817.49  1070.9  849.49  1099.1  859.52
  1124.4  873.54  1186.9  892.04    1224   899.1  1308.5   891.3  1400.9  876.77
#Mann= 6 ,-1,0
       0     .05       0   109.7     .06       0   189.7     .05       0
   585.5      .1       0   663.8    .045       0   753.3      .1       0
Bank Sta=663.8,753.3
XS Rating Curve= 0 ,0
Exp/Cntr(USF)=0,0
Exp/Cntr=0.3,0.1

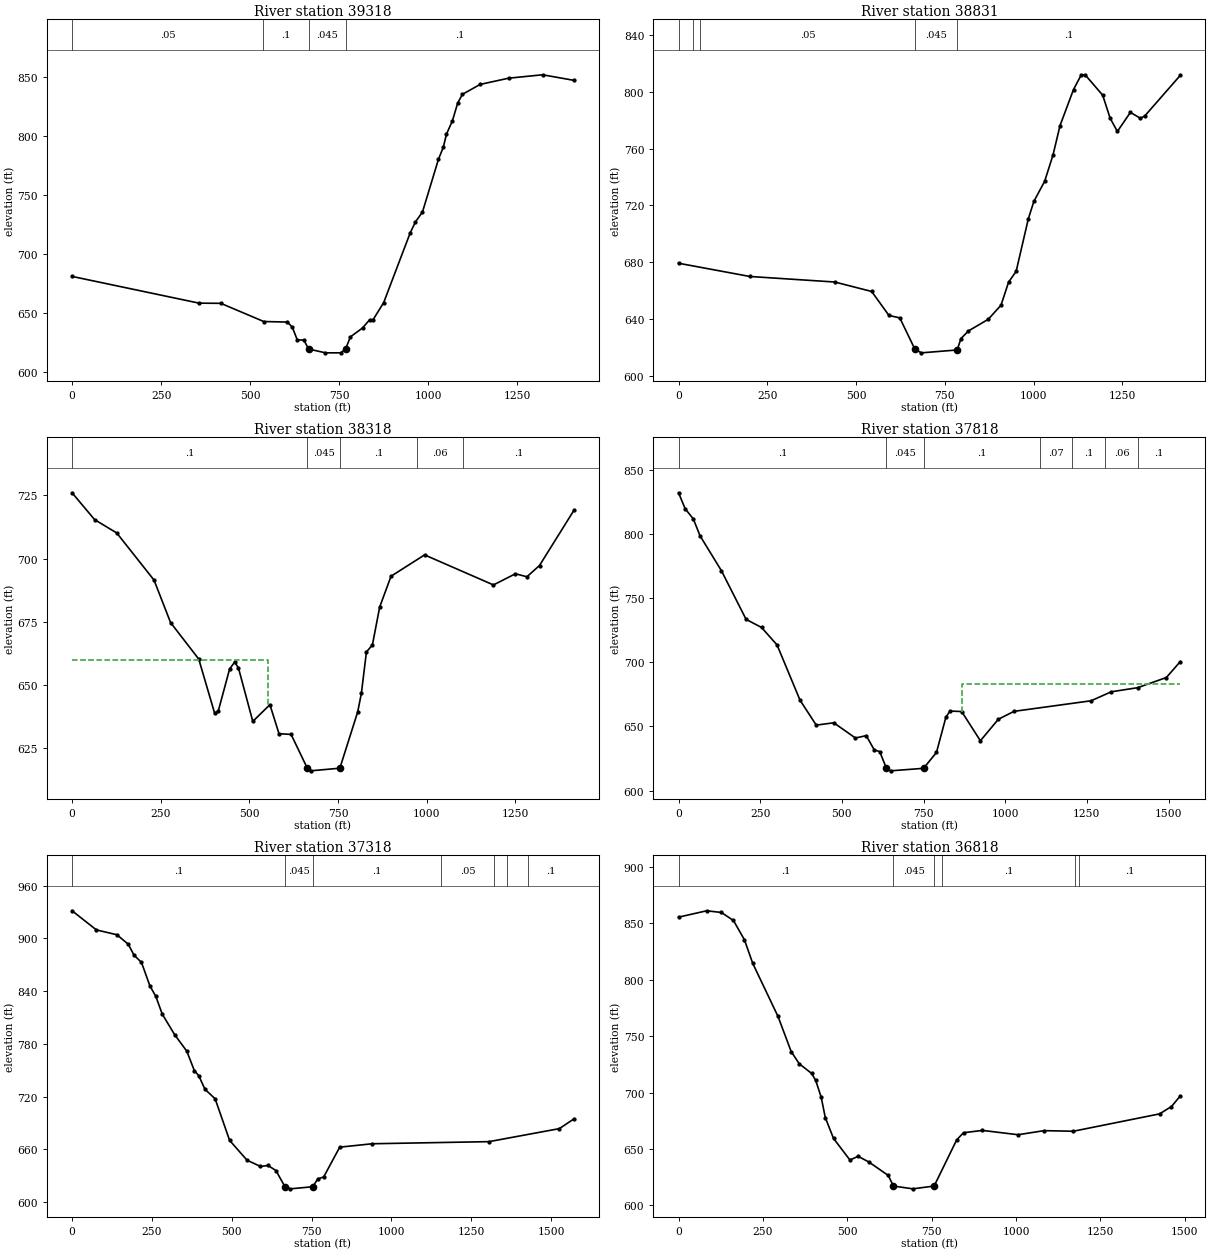
Type RM Length L Ch R = 1 ,39318   ,468.7,487.4,515.2
XS GIS Cut Line= 6
1592204.86139017402385.0049112591592459.40353201402550.528530344
1592622.74506883402651.3606777491592697.77182168 402696.80350025
 1592762.7395395402734.4710758331593430.26281075403077.252542511
#Sta/Elev= 30
       0  681.18   356.4  658.55   417.6  658.38   538.2  642.97   604.5  642.52
   618.4  638.17   632.3  627.35   650.7  627.28  664.14619.6764   711.5  616.44
   754.4  616.45   767.9  619.61   781.4  629.95   815.4   637.5   835.3   644.4
   845.2  644.55   874.9  659.03   949.1  717.91     964  727.36   983.7  735.69
  1028.7  780.48  1042.2  790.57  1051.2  801.74    1068  813.16  1082.8  828.21
  1096.1  835.48  1145.6  843.85  1225.4  849.12  1320.9  852.02  1408.8  847.32
#Mann= 4 ,-1,0
       0     .05       0  535.59      .1       0  664.14    .045       0
   767.9      .1       0
Bank Sta=664.14,767.9
XS Rating Curve= 0 ,0
Exp/Cntr(USF)=0,0
Exp/Cntr=0.3,0.1

Type RM Length L Ch R = 1 ,38831   ,519.2,512.6,491.5
XS GIS Cut Line= 6
1592028.08192662402542.5916569291592536.97559387403192.436813927
1592592.73105978403260.4255230931592722.66715162403405.470836675
1592791.75526803403479.2167521781592934.12801478403625.230239681
#Sta/Elev= 30
       0  679.24   200.9  669.91     440  666.01   543.9  659.35   592.6  642.44
   623.1  640.74   665.8618.5641   684.1  616.12   784.6618.1457   795.4  626.17
   816.3  631.55   872.1  639.72   908.3  649.74   929.4  665.92   950.7  673.48
   985.2  710.68  1000.8  722.89  1030.9  736.88  1054.6  755.51  1074.3   776.2
  1112.3   801.6  1134.2     812  1145.3  811.91  1194.5   797.6  1215.4  781.43
  1235.8  772.05  1272.5  785.53  1300.8  781.29  1313.2  783.06  1413.1  811.62
#Mann= 5 ,-1,0
       0     .05       0      40      .1       0      60     .05       0
   665.8    .045       0   784.6      .1       0
Bank Sta=665.8,784.6
XS Rating Curve= 0 ,0
Exp/Cntr(USF)=0,0
Exp/Cntr=0.3,0.1

Type RM Length L Ch R = 1 ,38318   ,525.1,500,477.7
XS GIS Cut Line= 6
1591609.35962842403053.9025235921592054.17862068403418.882764757
1592247.44693492403577.4618439231592538.55691701403816.322258592
1592615.26017568403879.2581563441592727.67924218403898.584561259
#Sta/Elev= 30
       0  726.04    63.5  715.42     126  710.13   231.2  691.47   277.8  674.66
   357.3  660.21     402   638.8   412.3  639.62   444.4  656.34   458.6  659.01
   469.2  656.72   509.7  635.55     558  642.15   583.6  630.66   617.7   630.4
   663.2  617.07   672.6  615.97  755.24617.0185   805.6  639.32   815.9  646.63
   830.2  663.04     847  665.78   867.6  680.83   899.6  693.01   994.2  701.45
  1188.4  689.56  1250.5  693.98  1282.8  692.79  1318.3  697.25  1415.2  719.06
#Mann= 5 ,-1,0
       0      .1       0   663.2    .045       0  755.24      .1       0
  972.89     .06       0 1103.52      .1       0
#XS Ineff= 2 , 0
          553.01  659.95
Permanent Ineff=
       F       F
Bank Sta=663.2,755.24
XS Rating Curve= 0 ,0
Exp/Cntr(USF)=0,0
Exp/Cntr=0.3,0.1

Type RM Length L Ch R = 1 ,37818   ,536.9,500,460.7
XS GIS Cut Line= 6
1591200.44279534403735.8831150081591998.65740626 403945.93748492
1592082.07718693 403972.763546751592263.34454092 404036.20338051
1592384.46306509 404028.779838921592685.57696417403956.060496166
#Sta/Elev= 30
       0  831.91    20.3  819.46    45.2  811.58    65.8  798.41   131.2  771.25
   206.9   733.3   254.1  727.01   301.6   713.4   371.9  670.39   421.6  650.94
   475.3  652.77   541.5   640.9   574.6  642.76   599.4  631.59     616  630.27
  636.36 617.366     649  615.34   750.1  617.31   789.7  629.69   818.6  657.18
   831.1   661.9   866.8  661.52   924.1  638.76     979   655.5  1027.1  661.68
    1263  669.91  1324.7   676.9  1405.7  680.11  1493.5  688.03  1536.2  700.49
#Mann= 7 ,-1,0
       0      .1       0  636.36    .045       0   750.1      .1       0
 1105.07     .07       0 1205.07      .1       0 1306.42     .06       0
 1407.03      .1       0
#XS Ineff= 2 , 0
                          868.44          682.84
Permanent Ineff=
       F       F
Bank Sta=636.36,750.1
XS Rating Curve= 0 ,0
Exp/Cntr(USF)=0,0
Exp/Cntr=0.3,0.1

Type RM Length L Ch R = 1 ,37318   ,538.1,500,448.6
XS GIS Cut Line= 6
1591316.75850759404727.2508829241592121.45079584404296.156600758
1592275.68211468404164.032521173  1592390.632016404092.694081172
1592534.14025918404026.1673113411592687.11928393403972.039138749
#Sta/Elev= 30
       0   931.3    76.3  909.52   140.5  904.05   175.8   893.3   194.2  880.79
   217.4  872.57     244  845.67   262.2  834.09   282.4  813.84   321.1  790.49
   359.3  771.67   382.9  749.61   396.8  743.72   416.3   728.3   448.1  717.49
   493.4  670.23   547.8  647.71   589.9  640.59   613.6  641.65   638.5  635.94
   666.7  617.54   683.8  615.09  753.61617.4687   769.9  626.45   788.1  628.59
   838.3  662.48   940.1  666.36  1305.8  668.76  1526.1  683.55  1571.7  694.56
#Mann= 7 ,-1,0
       0      .1       0   666.7    .045       0  753.61      .1       0
    1156     .05       0 1321.29      .1       0 1361.29     .06       0
 1429.47      .1       0
Bank Sta=666.7,753.61
XS Rating Curve= 0 ,0
Exp/Cntr(USF)=0,0
Exp/Cntr=0.3,0.1

Type RM Length L Ch R = 1 ,36818   ,491.8,500,505.8
XS GIS Cut Line= 6
1592227.01292068405296.3668706721592281.13256308405103.755707338
1592425.29205167404210.6160894191592465.43665643404115.986029342
1592571.54274343404037.813285425  1592705.820362403977.861961752
#Sta/Elev= 30
       0   855.4    83.3  861.06   126.6  859.58   162.6  852.49   195.1  835.44
   219.6  814.63   294.7  767.44   333.7  736.33   357.7   725.5   394.2  716.98
   406.4  710.71   422.6  695.94   434.7  677.89   459.1   659.4   507.7  640.28
   532.1  643.53   564.5  638.38   621.3  626.56  636.55617.1975   694.3  614.72
   757.2   617.2     824  658.09   844.2  664.43   900.4  666.48    1006  662.65
  1082.7  666.27  1169.6  665.75  1425.1  681.13  1460.3  687.66  1486.5  697.06
#Mann= 6 ,-1,0
       0      .1       0  636.55    .045       0   757.2    .025       0
  781.66      .1       0 1174.86     .05       0 1184.86      .1       0
Bank Sta=636.55,757.2
XS Rating Curve= 0 ,0
Exp/Cntr(USF)=0,0
Exp/Cntr=0.3,0.1

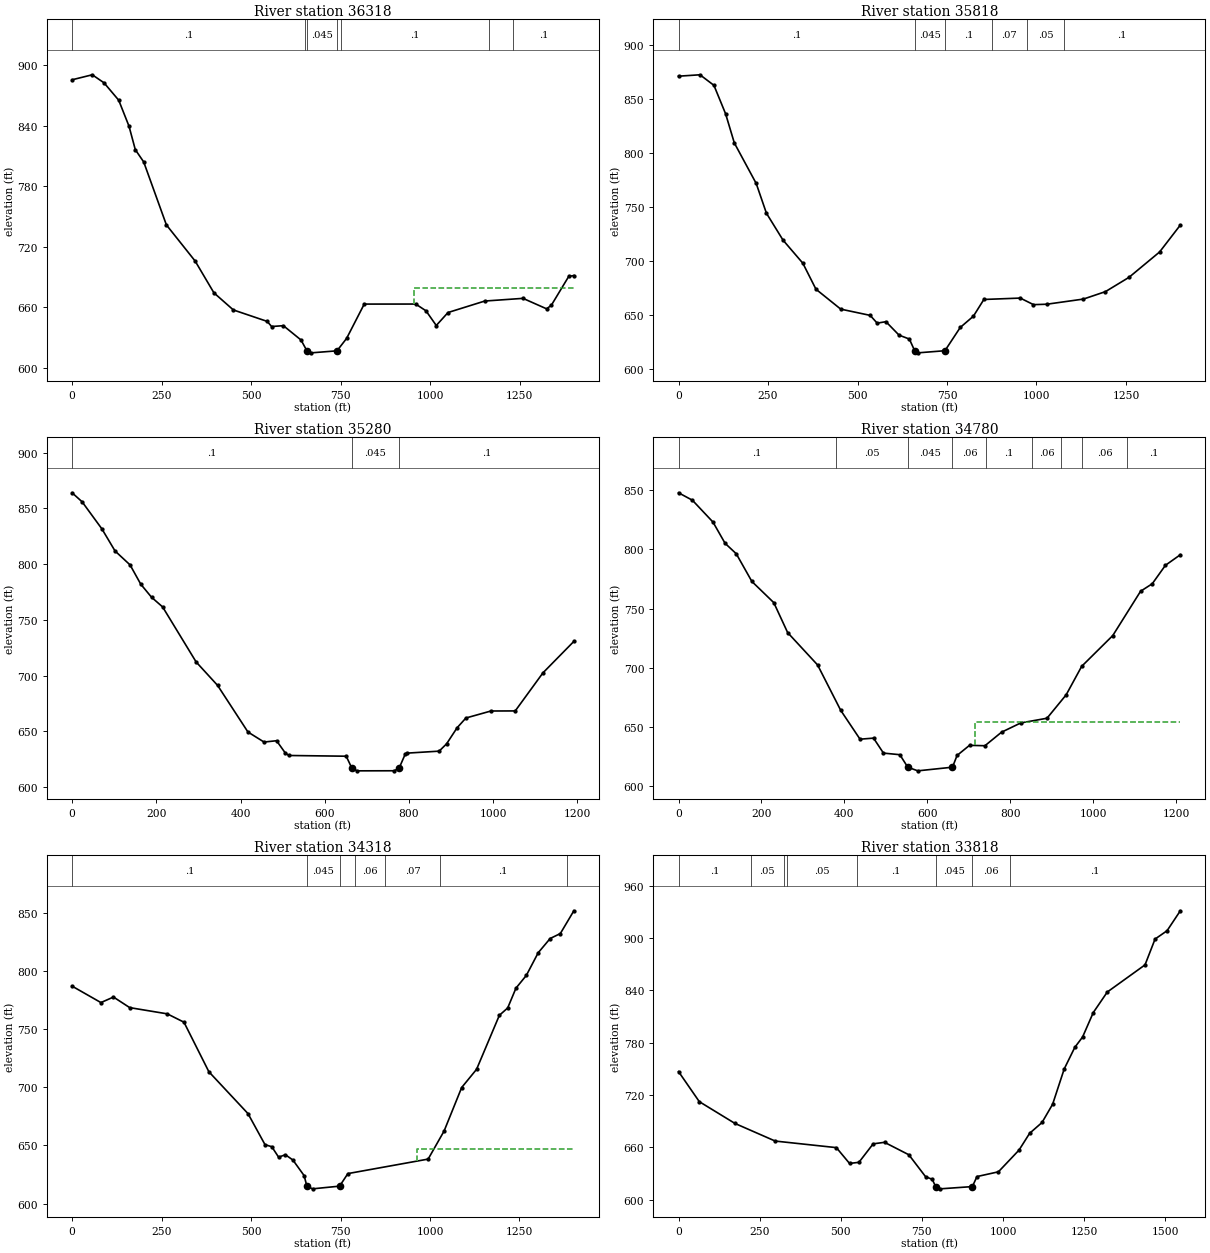
Type RM Length L Ch R = 1 ,36318   ,501.4,500,498.3
XS GIS Cut Line= 6
1592671.52088992405467.4849667551592693.80266951405370.399531007
1592759.68738025 405083.332191751592896.69891725404486.352742672
1592962.58362801404199.2850753371592986.32340993404102.534612671
#Sta/Elev= 30
       0  885.37    56.4  890.34    89.2  882.37   130.2  865.14     159  839.32
   176.5  816.11     200  803.92   263.3  741.53   343.7  705.62     396  674.17
   450.2  657.22   544.8  645.85     557  640.78   589.9  641.62   639.1  627.42
   655.6  616.72   667.9  614.69  739.54616.6812   766.4     629   815.6  663.02
   959.3  663.06     988  656.35  1016.7  641.79  1049.5  654.66  1152.1  666.04
  1258.8   668.7  1324.6  658.34  1337.8  661.78  1386.4   690.4  1400.8  691.34
#Mann= 7 ,-1,0
       0      .1       0  650.39    .025       0   655.6    .045       0
  739.54    .025       0  750.39      .1       0 1163.52     .06       0
 1231.95      .1       0
#XS Ineff= 2 , 0
                          953.56          679.44
Permanent Ineff=
       F       F
Bank Sta=655.6,739.54
XS Rating Curve= 0 ,0
Exp/Cntr(USF)=0,0
Exp/Cntr=0.3,0.1

Type RM Length L Ch R = 1 ,35818   ,525.9,538.1,546.8
XS GIS Cut Line= 6
1593183.21245185405589.669761762 1593337.6478385404778.855766594
1593355.90830067404693.2604653391593420.23756833404411.176383838
 1593440.4767011404313.7815655021593458.02883135404215.207287595
#Sta/Elev= 30
       0  871.15    59.9  872.46    98.9  862.66   131.5  836.26   155.9   809.2
     217  771.64   245.5  744.08     292  719.06   347.2  697.72   383.9  673.57
   453.1   655.1   535.3  649.31   554.9  642.11   579.4  643.45     616  630.98
   644.8  627.35   659.6616.5683   668.9  614.56  744.21 616.528     787   638.1
   823.7  648.53     853  664.06   954.7  665.35   991.6  659.26  1028.5  659.64
  1131.1  664.43  1192.6  671.33  1258.5   684.6  1343.9  708.11  1401.8  733.06
#Mann= 6 ,-1,0
       0      .1       0   659.6    .045       0  744.21      .1       0
  875.39     .07       0  972.91     .05       0 1076.72      .1       0
Bank Sta=659.6,744.21
XS Rating Curve= 0 ,0
Exp/Cntr(USF)=0,0
Exp/Cntr=0.3,0.1

Type RM Length L Ch R = 1 ,35280   ,484.5,500.2,512.6
XS GIS Cut Line= 2
1593607.64546245405622.373488872 1594003.9871479404498.858467848
#Sta/Elev= 30
       0   863.9    23.8  855.83    70.8  831.52   102.1  811.67   137.7   799.2
   163.1  781.91   188.6  770.22     215  761.51   294.6  712.14   345.5  691.14
   417.6  649.32   455.8  640.32   485.5  641.51   506.7  630.27   515.2  628.27
   650.9  627.62     664617.1686   676.4   614.5   765.4  614.57  776.83   617.2
   790.9  629.39   795.1  630.38   871.5  632.16   889.2  638.72   914.2  653.14
   935.1  661.89   994.5  668.17  1052.2  668.24    1118  702.38  1191.4   730.6
#Mann= 3 ,-1,0
       0      .1       0     664    .045       0  776.83      .1       0
Bank Sta=664,776.83
XS Rating Curve= 0 ,0
Exp/Cntr(USF)=0,0
Exp/Cntr=0.3,0.1

Type RM Length L Ch R = 1 ,34780   ,463.1,461.9,460.5
XS GIS Cut Line= 3
1593944.16387245405753.6743827041594171.91978048405350.834687647
1594585.12697084404727.774503917
#Sta/Elev= 30
       0  847.75    33.5  841.45      83  823.05   112.3  805.08   139.2  796.29
   176.9  772.89   229.8  754.98   263.2  729.71   335.4   702.4   391.2  664.09
   437.8  639.71   470.4  640.62   494.3  627.97   533.8  626.63  552.92   616.1
   577.1     613   660.8  616.08   671.9  626.01   701.9  634.53   739.1  634.19
   779.1  645.62   825.5  653.44   888.8  657.41     935  677.16   972.5  701.25
  1047.5  727.23  1114.5   764.6  1142.7  770.95  1174.5  786.54  1210.4  795.43
#Mann= 9 ,-1,0
       0      .1       0     380     .05       0  552.92    .045       0
   660.8     .06       0  742.77      .1       0  852.77     .06       0
  922.77      .1       0  972.77     .06       0 1082.77      .1       0
#XS Ineff= 2 , 0
                          716.06          654.43
Permanent Ineff=
       F       F
Bank Sta=552.92,660.8
XS Rating Curve= 0 ,0
Exp/Cntr(USF)=0,0
Exp/Cntr=0.3,0.1

Type RM Length L Ch R = 1 ,34318   ,488.1,499.9,511.8
XS GIS Cut Line= 6
1594248.32482292406089.3022926751594307.79255176406009.038673669
1594512.82987134405679.3086900861594600.43566726405542.735800505
1594652.81121868405457.5030313431595003.82692084404908.761674762
#Sta/Elev= 30
       0   786.8    80.6  772.68   115.7  777.42   161.1  768.33     266  762.99
   312.6  755.83   382.2  713.26   491.5   677.3     539  650.65     558  648.86
     577  639.91     596  641.97     617  637.43   648.3  624.05  656.01 615.014
   671.8  612.69  747.35615.0037   770.6  625.79   994.8  638.24  1039.3  662.31
  1088.5  699.73  1130.1  715.35  1193.8  761.76    1217  768.03  1240.1  785.05
  1269.1     796  1302.3  815.48  1335.7  827.71  1364.1  831.95  1401.9  851.52
#Mann= 7 ,-1,0
       0      .1       0  656.01    .045       0  747.35      .1       0
  790.47     .06       0  875.57     .07       0  1027.1      .1       0
  1382.1     .06       0
#XS Ineff= 2 , 0
                          962.79          646.72
Permanent Ineff=
       F       F
Bank Sta=656.01,747.35
XS Rating Curve= 0 ,0
Exp/Cntr(USF)=0,0
Exp/Cntr=0.3,0.1

Type RM Length L Ch R = 1 ,33818   ,433.7,500,564
XS GIS Cut Line= 6
1594315.41359951406127.5112057631594680.70191093405992.394678086
1594788.54355876405941.0010800961594966.22857083405831.499002501
1595027.20646726405782.3422766771595537.02598567405231.733797833
#Sta/Elev= 30
       0  746.93      64  712.51     174  687.54     298  667.37   486.5  659.85
   527.1  641.75     556  643.02   599.9  664.18   634.9  665.93   709.9  651.67
   761.5  626.55     782  623.56   792.5  615.23   806.7  612.66   905.7  615.24
   919.9  626.72     986  632.16  1049.5  657.03  1082.2  676.24  1120.4  688.63
  1153.1  709.55  1188.8  749.96  1221.5  774.73  1245.4  786.49  1278.4  814.53
  1321.6  838.06  1437.9  869.14  1468.8  898.69  1505.8  908.22  1546.7  931.08
#Mann= 8 ,-1,0
       0      .1       0  223.36     .05       0   324.2     .06       0
   334.2     .05       0  549.11      .1       0   792.5    .045       0
   905.7     .06       0 1021.26      .1       0
Bank Sta=792.5,905.7
XS Rating Curve= 0 ,0
Exp/Cntr(USF)=0,0
Exp/Cntr=0.3,0.1

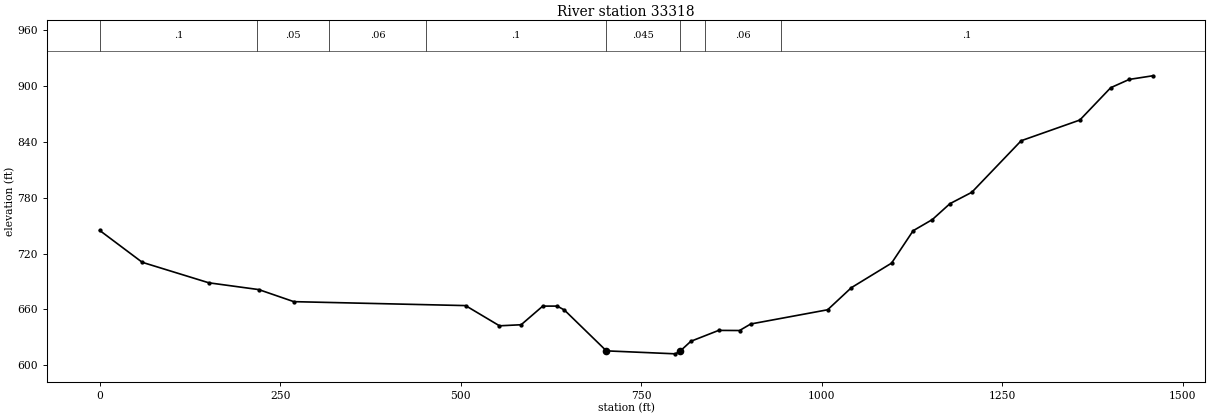
Type RM Length L Ch R = 1 ,33318   ,492.1,500,507.5
XS GIS Cut Line= 6
1594313.06222625406138.7431386711594437.26801459406107.920693755
1594555.47283067406085.5224445911594661.89289342406082.249157175
1594922.17026001406180.2761920841595694.59424008406471.189652249
#Sta/Elev= 30
       0  744.84      59  710.57   151.2  688.57   220.4  681.28   268.9  668.33
   506.7   664.1   553.7   642.4   583.7  643.55   613.6  663.54   633.6  663.57
   643.5  659.39   701.7  615.51   797.4  612.31  804.17 615.467   818.7  625.79
   857.2  637.48   886.1  637.35   901.6  644.35  1008.1  659.62    1041  683.36
  1096.6  709.69  1126.5  744.48  1153.1  756.46  1177.4  773.49  1207.7  785.72
  1276.1  841.08  1357.3  863.29  1400.1  898.01  1425.7   906.9  1458.3  910.81
#Mann= 8 ,-1,0
       0      .1       0  217.97     .05       0  318.28     .06       0
  451.63      .1       0   701.7    .045       0  804.17     .07       0
  837.88     .06       0  942.88      .1       0
Bank Sta=701.7,804.17
XS Rating Curve= 0 ,0
Exp/Cntr(USF)=0,0
Exp/Cntr=0.3,0.1