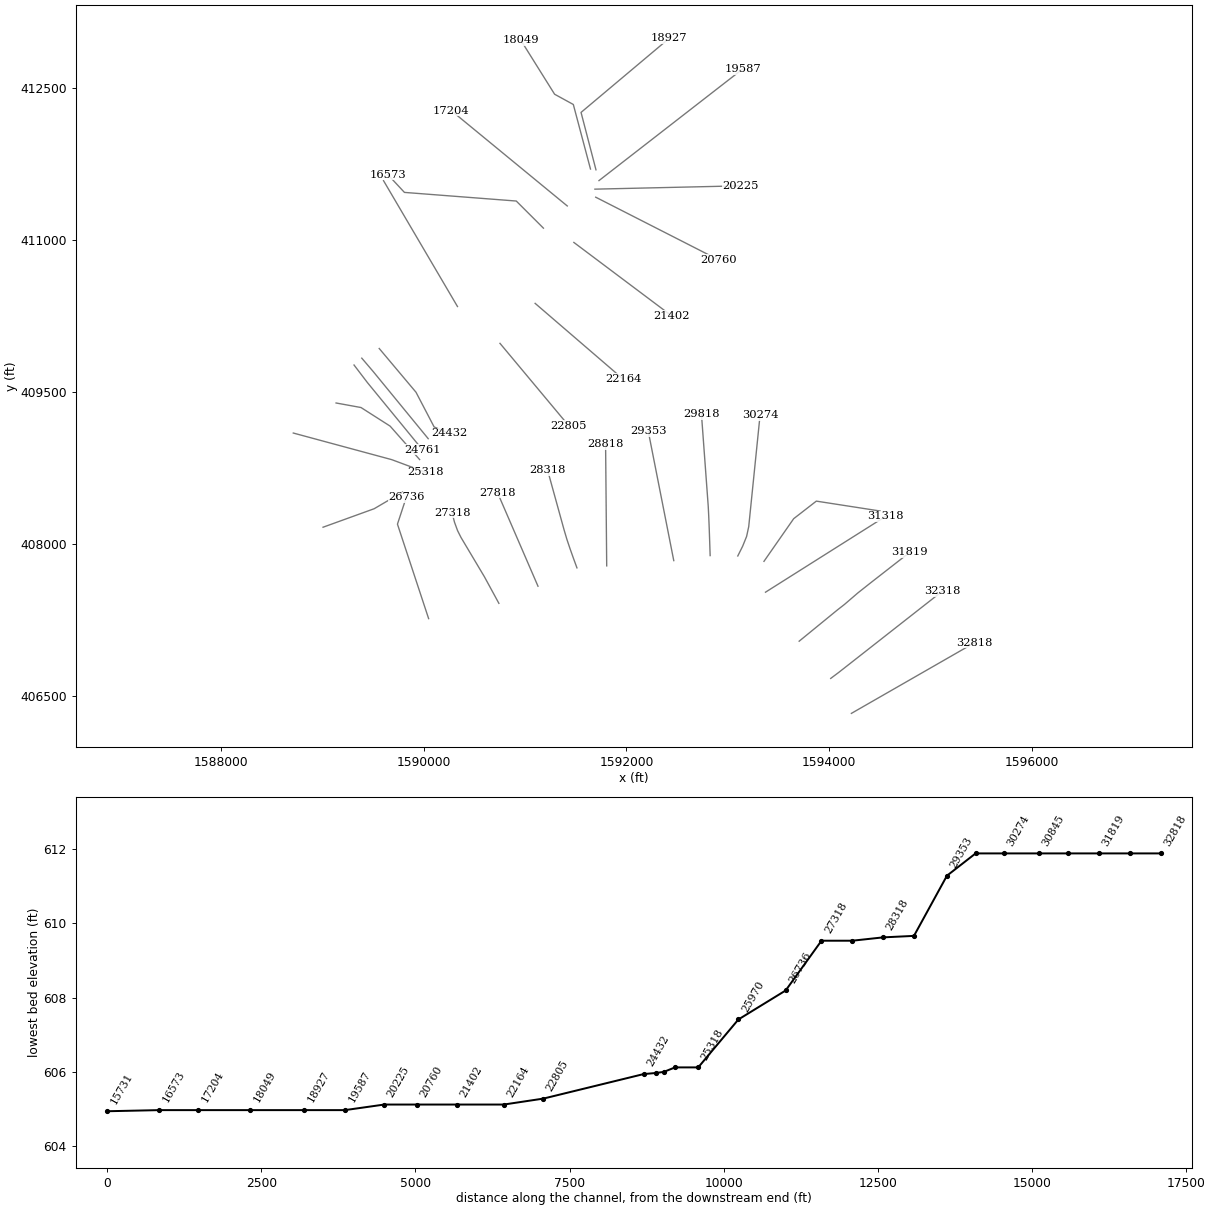
HEC-RAS study FISHINGCK.prj: FISHINGCK

--- FISHINGCK.g01 (geometry) --- (continued)

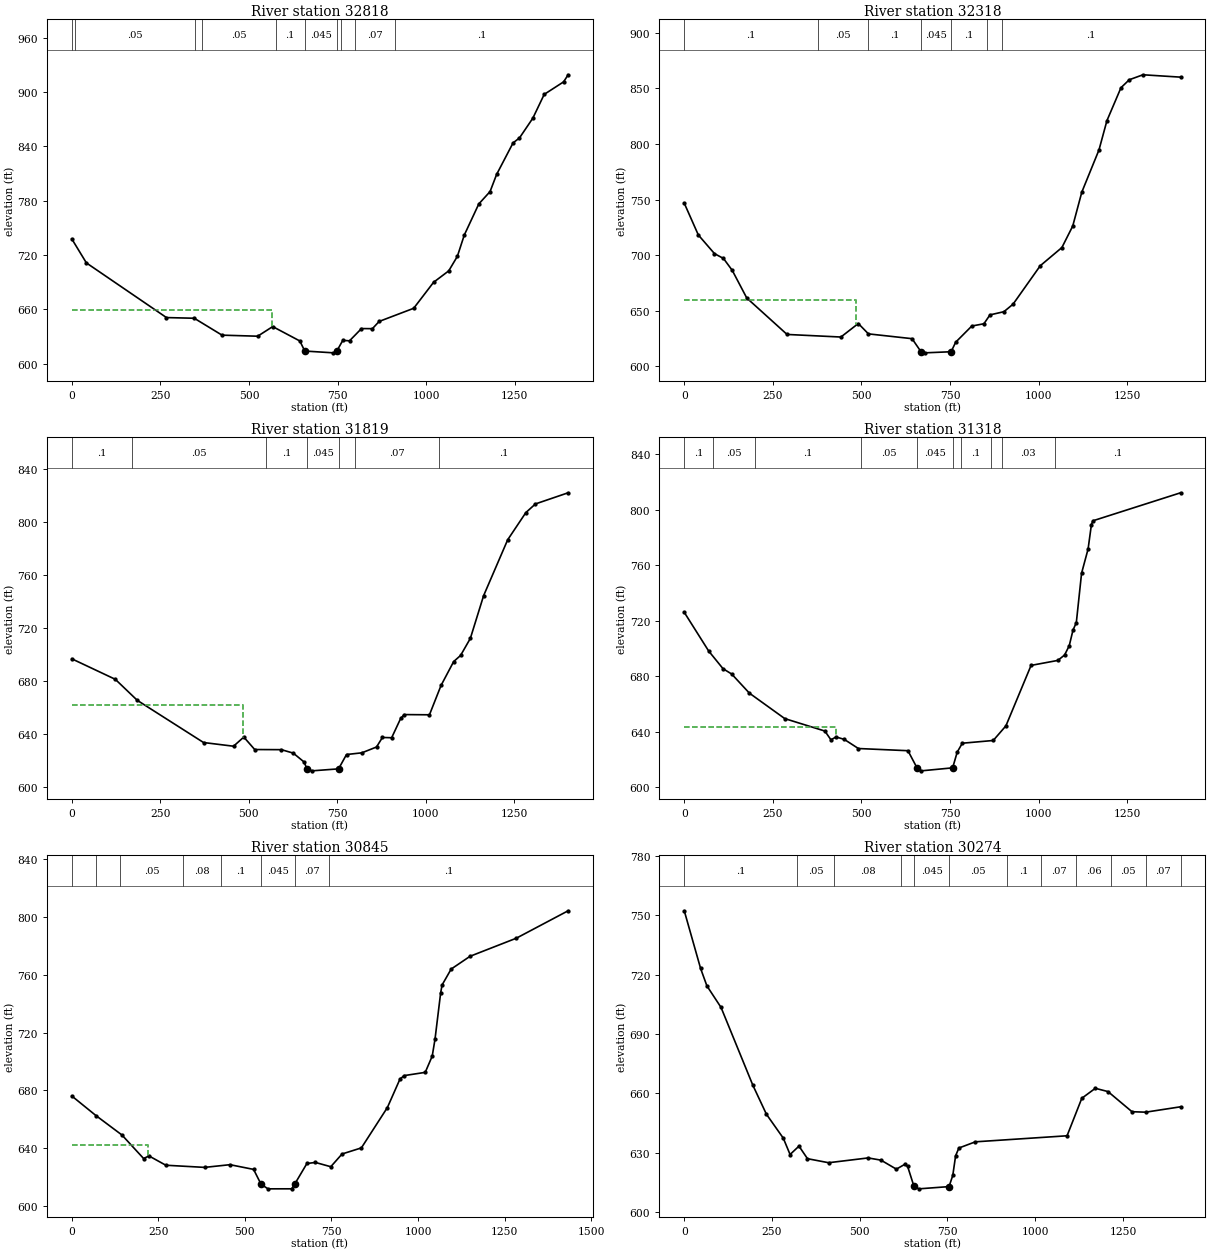
Type RM Length L Ch R = 1 ,32818   ,495.2,500,507.4
XS GIS Cut Line= 6
1594220.39705725406328.0705159161594306.77910234406377.670810416
1594478.18853642406476.0925295951594562.19919518 406524.33127825
1595348.78390808406975.9835901711595435.16628125407025.583556592
#Sta/Elev= 30
       0  737.78    41.2  711.25   267.2  650.85   345.6  650.11     424  631.42
   524.6  630.26     567  640.89   643.6  624.99  657.54613.8596   738.5  611.88
     748  613.91   764.9  625.69   783.8  625.15   817.6   638.7   848.4  638.59
   867.4  646.58   964.9  661.11  1021.1  689.87  1063.8  702.46  1088.2  718.54
  1107.7  742.04  1148.7  776.43  1180.5  790.12  1198.9     809  1245.4   843.9
  1263.5  849.38  1301.2  871.21  1333.3  897.52    1388  911.34  1400.8  919.17
#Mann= 10 ,-1,0
       0      .1       0      10     .05       0  347.27      .1       0
  367.27     .05       0  575.39      .1       0  657.54    .045       0
     748      .1       0  760.39     .06       0  800.39     .07       0
  912.89      .1       0
#XS Ineff= 2 , 0
          564.82  659.59
Permanent Ineff=
       F       F
Bank Sta=657.54,748
XS Rating Curve= 0 ,0
Exp/Cntr(USF)=0,0
Exp/Cntr=0.3,0.1

Type RM Length L Ch R = 1 ,32318   ,498.2,499.5,501.5
XS GIS Cut Line= 6
1594016.33972259406673.3437755111594096.05052118406733.118262261
1594174.10253042406794.3740452531594470.32995634407026.857832253
1594607.99601959407134.8996109221595119.63377585407536.440146416
#Sta/Elev= 30
       0  746.68    39.7  718.06    85.3  701.24   110.7  696.88   135.3  686.24
   176.4  661.28   290.1  628.45   442.1  626.12   491.2  638.28   519.8  628.96
   642.9  624.64  668.12612.8922   679.4  611.88  753.15612.8689     766  621.45
   811.5  636.03   845.7  638.07   862.8  646.06   902.1  648.93     928  655.73
  1004.8  690.36  1065.8  706.73  1096.4   726.1    1122  756.65  1170.5   794.7
  1192.9  821.04  1232.5  850.69  1255.9  857.87  1294.6  862.35  1400.8  860.22
#Mann= 7 ,-1,0
       0      .1       0  377.29     .05       0  517.91      .1       0
  668.12    .045       0  753.15      .1       0  855.41     .06       0
  895.41      .1       0
#XS Ineff= 2 , 0
           486.1  659.09
Permanent Ineff=
       T       F
Bank Sta=668.12,753.15
XS Rating Curve= 0 ,0
Exp/Cntr(USF)=0,0
Exp/Cntr=0.3,0.1

Type RM Length L Ch R = 1 ,31819   ,506,500.5,492.9
XS GIS Cut Line= 6
1593704.99454476407040.9844444251594082.54497075407349.823721752
1594151.53695875407403.5752546791594284.19056484407517.721023753
1594411.75330184407618.6814517531594796.93953934407919.290758669
#Sta/Elev= 30
       0  696.55   122.9  681.05   184.9  665.17     372  633.28   456.7  630.49
   485.7   637.4   516.5  627.98   591.9  627.88   625.4  625.27   655.5  618.65
   664.2  613.41   678.4  611.88  753.28613.3777   775.7  624.21   818.9  625.49
   860.4  629.89   877.1   637.1   903.2   636.9   928.6  651.46   938.8   654.4
  1009.9  654.24  1042.7  676.45  1078.3  694.47  1097.8  699.09  1125.4     712
  1162.8  744.25  1230.8  786.51  1282.1  807.07  1309.2  813.61  1401.5  822.04
#Mann= 7 ,-1,0
       0      .1       0  169.56     .05       0  547.78      .1       0
   664.2    .045       0  753.28      .1       0  800.24     .07       0
  1036.8      .1       0
#XS Ineff= 2 , 0
          482.16  661.94
Permanent Ineff=
       F       F
Bank Sta=664.2,753.28
XS Rating Curve= 0 ,0
Exp/Cntr(USF)=0,0
Exp/Cntr=0.3,0.1

Type RM Length L Ch R = 1 ,31318   ,468.3,472.6,477.7
XS GIS Cut Line= 6
1593372.70255843   407524.9975841593456.90711442407578.210404083
1593785.14070992407785.6351860911594070.44591358407965.932397678
1594305.55896042408114.5101845121594556.85242109408273.313672677
#Sta/Elev= 30
       0  726.11    68.8  698.27   109.4  685.49   133.9  681.64   183.8  667.87
   283.7  649.52   396.8  640.56   413.9  634.26   428.4   636.3   451.6  634.55
   491.4  627.97   631.3  626.39  656.61614.1602     669  611.88  757.46614.0389
   770.4  625.41   784.8  631.79     872  633.75   907.8   644.3   978.8  687.87
  1054.5  691.47  1073.4  695.38  1086.5  702.03  1097.1  713.28  1106.5   718.7
  1121.3  754.26  1139.7  771.73  1149.1  789.33  1153.2  792.07  1400.8  812.27
#Mann= 10 ,-1,0
       0      .1       0      80     .05       0  198.83      .1       0
  497.89     .05       0  656.61    .045       0  757.46    .025       0
  780.39      .1       0  865.39     .06       0  895.39     .03       0
 1046.64      .1       0
#XS Ineff= 2 , 0
          429.64  643.63
Permanent Ineff=
       F       F
Bank Sta=656.61,757.46
XS Rating Curve= 0 ,0
Exp/Cntr(USF)=0,0
Exp/Cntr=0.3,0.1

Type RM Length L Ch R = 1 ,30845   ,528.8,571.3,608.4
XS GIS Cut Line= 4
1593357.63537309407829.5950286841593650.73284954408250.786957796
 1593874.3553686408424.4743512451594503.97216985 408326.77519243
#Sta/Elev= 30
       0  676.12      70  662.52   144.9  649.11   207.4  632.85   222.9  634.64
   271.6  628.21   383.7  626.72   456.8  628.59     525  625.33  546.61  615.04
   566.7  611.88   635.1   611.9   643.6  615.08     679  629.41   703.5  630.14
   747.9  627.18   780.5  635.99   836.3  640.21   911.4  668.12   947.8  687.84
     960  690.22  1020.7  692.46  1040.9  703.71    1049   715.5  1065.2  747.38
  1069.3  752.88  1095.6  763.92  1150.2  772.76  1283.8  785.27  1433.4  804.24
#Mann= 8 ,-1,0
       0     .05       0      70      .1       0     140     .05       0
     320     .08       0     430      .1       0  546.61    .045       0
   643.6     .07       0  743.14      .1       0
#XS Ineff= 2 , 0
          220.48   642.4
Permanent Ineff=
       F       F
Bank Sta=546.61,643.6
XS Rating Curve= 0 ,0
Exp/Cntr(USF)=0,0
Exp/Cntr=0.3,0.1

Type RM Length L Ch R = 1 ,30274   ,446,456.1,465.6
XS GIS Cut Line= 6
1593099.31561881407882.7880458451593147.36276681407979.166462011
1593186.27476248408075.669549844 1593207.1917154408172.487597681
1593216.99222073408268.865685753 1593318.8371614409270.341045014
#Sta/Elev= 30
       0  752.22    46.6  723.09    64.5  714.32   104.8  703.44   195.4  664.19
   234.2  649.51   282.2  637.45   301.5  629.21   326.9  633.44   351.1   627.1
   411.4  625.06   523.9  627.48   560.5  626.36   604.4  621.82   628.5  624.26
   636.5  623.19   654.6   613.1   668.7  611.88   754.5613.0095   765.2   618.7
   773.2  628.57   782.5  632.48   829.5  635.61  1090.8  638.66  1132.8  657.58
  1171.3  662.62  1207.4  660.97  1275.8  650.81  1314.7  650.57  1414.3  653.29
#Mann= 12 ,-1,0
       0      .1       0   320.8     .05       0  427.67     .08       0
  618.92    .025       0   654.6    .045       0   754.5     .05       0
  918.92      .1       0 1016.42     .07       0 1117.05     .06       0
 1215.48     .05       0  1314.7     .07       0 1414.31     .06       0
Bank Sta=654.6,754.5
XS Rating Curve= 0 ,0
Exp/Cntr(USF)=0,0
Exp/Cntr=0.3,0.1

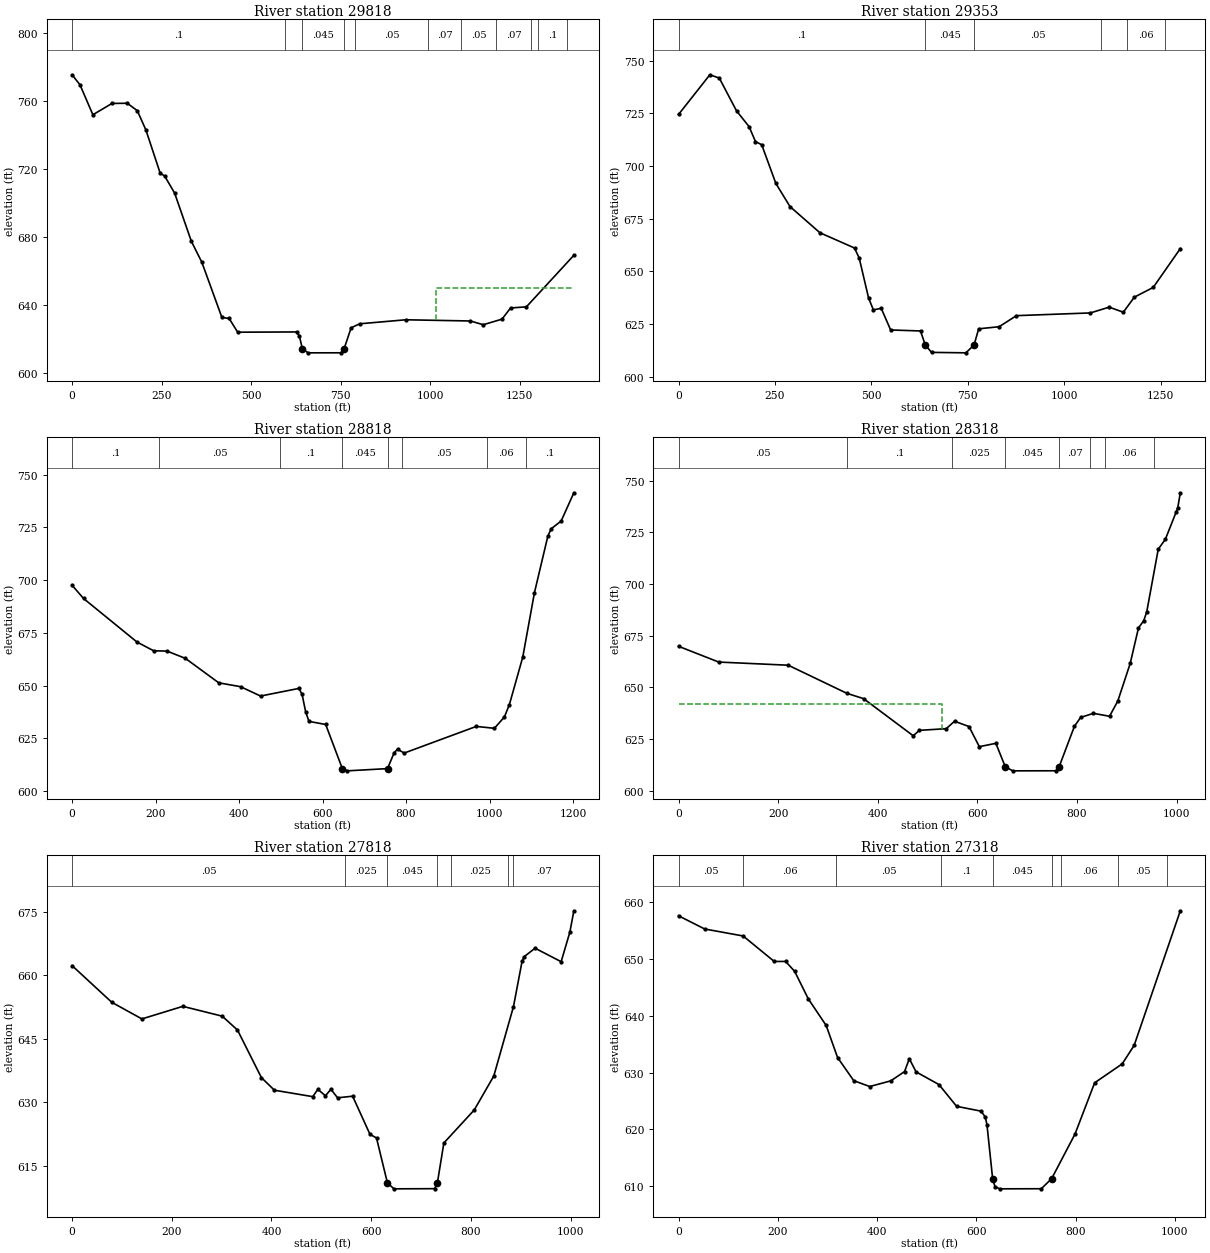
Type RM Length L Ch R = 1 ,29818   ,457.5,464.9,472.3
XS GIS Cut Line= 6
1592826.59078975407886.4532259261592819.89460893408085.326843917
1592816.30570534408183.7666076721592812.33196001408280.611558333
1592807.58754693408374.2662266791592740.64575167409284.699117094
#Sta/Elev= 30
       0  775.21    22.1  769.33    58.1  751.72   111.4  758.38   154.2  758.48
   182.2   754.1   206.2  742.77   246.2  717.29   258.2  715.86   286.3  705.74
     333  677.43   362.3  665.12   418.4  632.64   438.4  632.11   462.4     624
   626.8  624.16   634.8  621.73   642.9  614.35   658.9  611.88   751.2   611.9
   759.7 614.341   779.2   626.6   803.3  628.94   931.7   631.3  1112.1  630.59
  1148.2   628.4  1200.4  631.67  1224.4  638.23  1268.6   638.9  1401.1  669.18
#Mann= 11 ,-1,0
       0      .1       0  595.69    .025       0   642.9    .045       0
   759.7      .1       0  790.69     .05       0  993.19     .07       0
 1086.94     .05       0 1183.82     .07       0 1282.26     .06       0
 1301.47      .1       0 1381.47     .06       0
#XS Ineff= 2 , 0
                          1016.1          650.18
Permanent Ineff=
       F       F
Bank Sta=642.9,759.7
XS Rating Curve= 0 ,0
Exp/Cntr(USF)=0,0
Exp/Cntr=0.3,0.1

Type RM Length L Ch R = 1 ,29353   ,546,535.1,523.7
XS GIS Cut Line= 6
 1592467.5070302407836.8708050351592448.25674063407934.602236877
1592410.05865429408128.5326232861592373.21883295408315.563745285
 1592235.2220617409016.1650343791592216.21488188409113.546401287
#Sta/Elev= 30
       0  724.47    81.2  743.32   105.7  741.76   150.5  726.15   183.1  718.66
   199.4  711.63   215.7  710.09   252.4  691.71   289.1  680.73   366.6  668.31
   456.3  661.06   468.5  656.29   492.8  637.32   505.2  631.69   525.6  632.42
     550  622.14   627.5  621.67   639.7  615.04     656   611.5   745.1  611.28
  766.34  615.02   778.3  622.69   831.3  623.68   876.2  628.94  1067.8  630.23
  1116.7  632.97  1153.4  630.57  1181.9  637.71  1230.9  642.34  1301.2  660.79
#Mann= 6 ,-1,0
       0      .1       0   639.7    .045       0  766.34     .05       0
 1096.64     .07       0 1163.52     .06       0 1261.95      .1       0
Bank Sta=639.7,766.34
XS Rating Curve= 0 ,0
Exp/Cntr(USF)=0,0
Exp/Cntr=0.3,0.1

Type RM Length L Ch R = 1 ,28818   ,487.4,500,515.5
XS GIS Cut Line= 6
 1591805.6866636407785.0144524281591801.25130501408272.884867758
1591800.45603101408360.3814119251591799.77394576408435.378309175
1591798.18339776408610.3710694161591794.75984818408986.917888507
#Sta/Elev= 30
       0  697.59    27.5  691.32   155.4   670.7   195.5  666.54   227.5   666.4
   271.5  662.94   351.5  651.35   403.5  649.54   451.5   645.1   543.5  648.72
     551   645.9   559.5  637.64   567.5  633.09   607.5  631.63   647.5  610.67
   659.5  609.66   755.6  610.71   771.6  618.26   779.6  619.92   795.6  618.08
   968.3  630.71  1011.6  629.81  1035.6  635.17  1047.6  641.08  1079.6  663.56
  1107.6  694.08  1139.6  720.79  1147.6  724.34  1171.6  728.04    1202  741.41
#Mann= 8 ,-1,0
       0      .1       0  208.83     .05       0  497.89      .1       0
   647.5    .045       0   755.6    .025       0  790.39     .05       0
  992.89     .06       0 1086.64      .1       0
Bank Sta=647.5,755.6
XS Rating Curve= 0 ,0
Exp/Cntr(USF)=0,0
Exp/Cntr=0.3,0.1

Type RM Length L Ch R = 1 ,28318   ,494.7,500,510.5
XS GIS Cut Line= 6
1591512.06585975407765.1145578321591477.80805425407858.994291335
1591444.50529934407952.7319647521591413.11133325408046.186174169
1591385.53625718408139.0724713361591222.65534934408729.518140838
#Sta/Elev= 30
       0  669.89    80.6  662.26   220.3  660.73     338  647.12   371.5  644.56
   471.1   626.6   483.5  629.22   537.5  630.02   554.1  633.63   583.1  631.05
   603.9  621.31   637.1  622.94   655.9  611.61     671  609.62   757.4  609.65
     764611.5349   794.8  631.17   807.2  635.47     833  637.44   865.3  636.02
   881.9  643.42   906.8  661.61   923.4  678.79   933.9  682.26     940  686.59
   963.1   716.9   977.3  721.61   998.9  734.79  1002.2  736.92  1007.4  744.17
#Mann= 8 ,-1,0
       0     .05       0     338      .1       0  548.64    .025       0
   655.9    .045       0     764     .07       0  826.14    .025       0
  856.14     .06       0  953.64      .1       0
#XS Ineff= 2 , 0
          529.03  641.92
Permanent Ineff=
       F       F
Bank Sta=655.9,764
XS Rating Curve= 0 ,0
Exp/Cntr(USF)=0,0
Exp/Cntr=0.3,0.1

Type RM Length L Ch R = 1 ,27818   ,490.9,500,506.8
XS GIS Cut Line= 6
1591127.70737651407583.9508781731591009.75944968407856.815489918
 1590971.3218625407945.7388685051590934.12377417408031.793486416
1590869.64785326408180.9546054151590728.29610184408507.961825415
#Sta/Elev= 30
       0  662.25    79.6  653.59   140.1  649.66   222.2  652.63   301.2  650.31
   331.8  647.04   379.8   635.8   405.9  632.82   482.9   631.3     493  633.03
   508.2  631.51   519.2  633.04   532.6  631.03   562.8  631.41   597.6  622.41
   610.7  621.54   632.5  610.98   645.6  609.53   727.3  609.57   732.9610.9814
   745.8  620.36   806.8  628.16     846  636.18   885.5  652.58   902.7  663.26
     907  664.37   928.8  666.36   981.1  663.17   998.6  670.17  1006.6   675.2
#Mann= 7 ,-1,0
       0     .05       0  547.89    .025       0   632.5    .045       0
   732.9      .1       0  760.39    .025       0  875.39     .06       0
  885.39     .07       0
Bank Sta=632.5,732.9
XS Rating Curve= 0 ,0
Exp/Cntr(USF)=0,0
Exp/Cntr=0.3,0.1

Type RM Length L Ch R = 1 ,27318   ,595.3,581.8,567.3
XS GIS Cut Line= 6
1590741.75604868407414.8337623331590599.55226484407676.179696336
1590367.87326625408065.602145836  1590334.171562408132.845449671
1590303.65751542408216.2908208371590280.03748393408309.497327343
#Sta/Elev= 30
       0  657.65    52.7  655.32   130.1  654.09   192.8   649.6   215.7   649.6
   233.9  647.86   261.4  643.01   297.4  638.32   320.4  632.67     353  628.59
   385.2  627.56   427.6  628.56   455.3  630.19   464.9  632.45   478.6  630.14
   524.7   627.9   560.2  624.07   609.5  623.22     618  622.18   621.4  620.79
   632.8  611.31   637.5  609.92   646.8  609.53   730.8  609.55   751.7611.3303
   798.7  619.18   838.3  628.22   893.7  631.54   917.9  634.81  1010.9  658.53
#Mann= 9 ,-1,0
       0     .05       0  129.72     .06       0  317.53     .05       0
  528.17      .1       0   632.8    .045       0   751.7      .1       0
  770.67     .06       0  885.89     .05       0  984.74     .07       0
Bank Sta=632.8,751.7
XS Rating Curve= 0 ,0
Exp/Cntr(USF)=0,0
Exp/Cntr=0.3,0.1

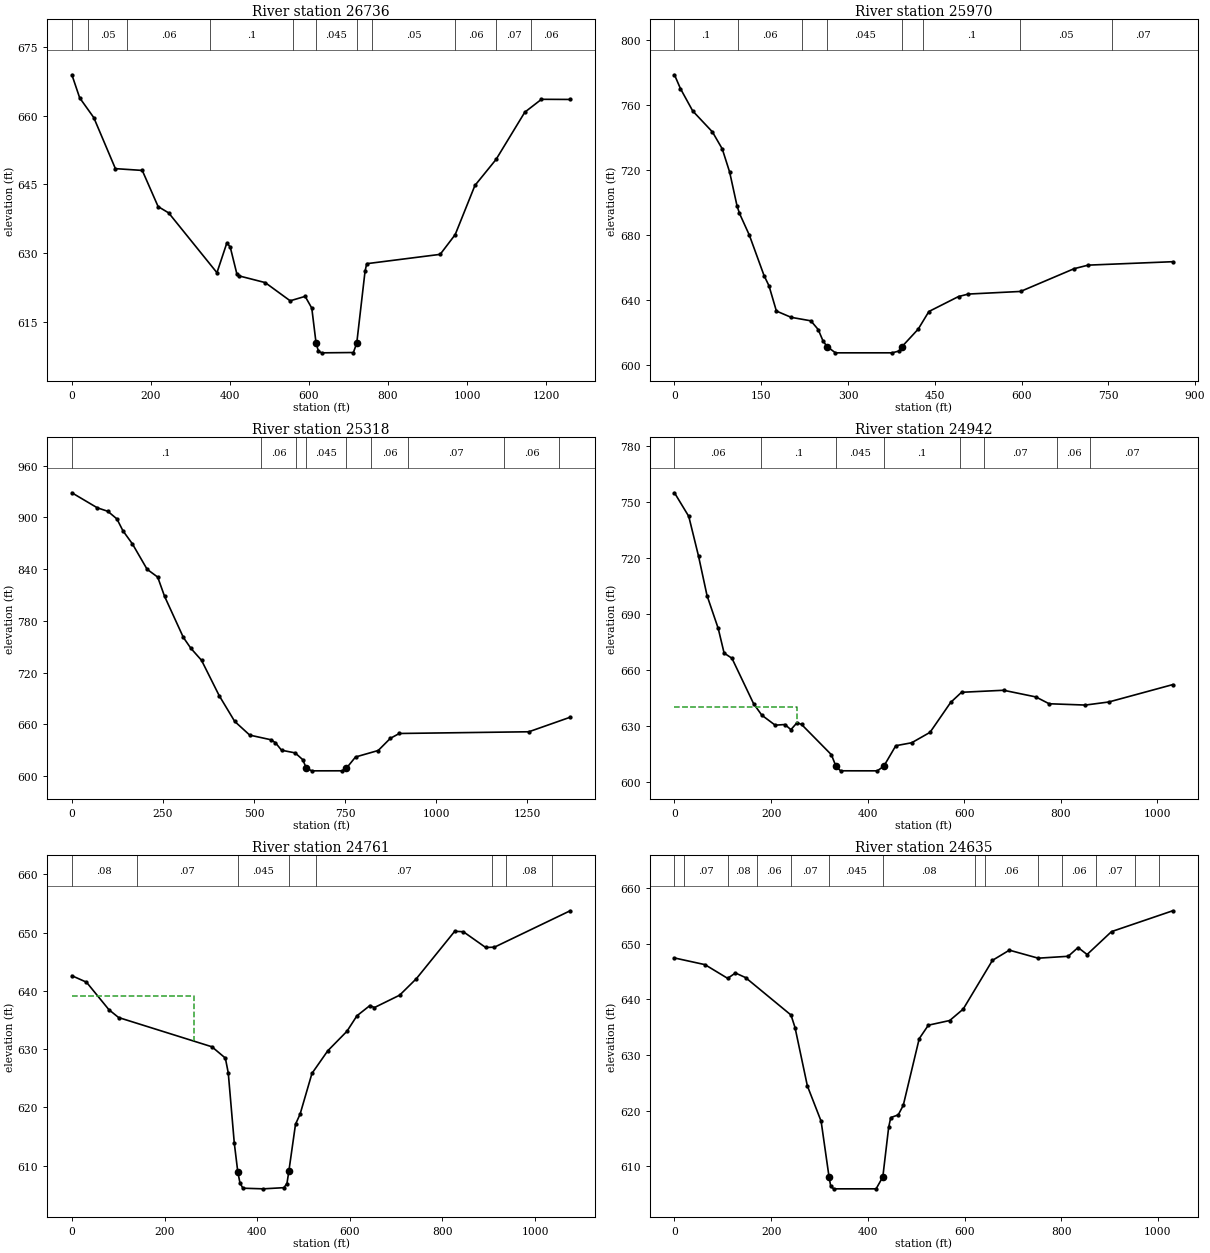
Type RM Length L Ch R = 1 ,26736   ,858.8,766.4,686.7
XS GIS Cut Line= 3
1590048.43173703407263.9353265031589740.77040824408197.044638807
 1589827.7932444408461.444720603
#Sta/Elev= 30
       0  668.95    19.7  663.91    55.4  659.59   110.1  648.44   178.1  648.05
   218.2  640.15   244.9  638.77   367.1   625.7   392.3  632.24   400.8  631.27
   417.6   625.4   421.8  625.03   489.2  623.54   552.4  619.56   590.3  620.53
   607.1  617.96  617.88  610.35     624  608.51   632.4  608.19   712.4  608.26
   720.9  610.33   741.9  626.03   746.1  627.67     932  629.71     970  634.02
  1019.9  644.76  1073.5  650.46  1146.2  660.78  1188.3  663.59  1260.9  663.56
#Mann= 11 ,-1,0
       0      .1       0      40     .05       0     140     .06       0
     350      .1       0     560    .025       0  617.88    .045       0
   720.9    .025       0     760     .05       0     970     .06       0
 1072.52     .07       0 1162.52     .06       0
Bank Sta=617.88,720.9
XS Rating Curve= 0 ,0
Exp/Cntr(USF)=0,0
Exp/Cntr=0.3,0.1

Type RM Length L Ch R = 1 ,25970   ,688.4,651.9,611.7
XS GIS Cut Line= 3
 1589006.4302524408166.6722359781589511.00343543408349.369612891
1589791.11462841408513.587622831
#Sta/Elev= 30
       0  778.52    10.3  770.03    31.6  756.23    65.6  743.37    82.6  732.93
    95.4  718.62   108.1  697.93   112.4  693.22   129.4  679.87   154.9  654.93
   163.4  648.67   176.2  633.13   201.7  629.26   235.8  627.11   248.5  621.74
     257  614.58     264  611.24   278.3  607.41   376.2  607.42   388.9  608.58
   393.2  611.18   393.2  611.19   421.3  621.99   439.8  632.84     491  642.05
     508  643.58   598.3  645.19   690.9   659.2   715.1  661.38   861.3  663.49
#Mann= 8 ,-1,0
       0      .1       0     110     .06       0     220      .1       0
     264    .045       0   393.2    .025       0     430      .1       0
  596.63     .05       0  756.63     .07       0
Bank Sta=264,393.2
XS Rating Curve= 0 ,0
Exp/Cntr(USF)=0,0
Exp/Cntr=0.3,0.1

Type RM Length L Ch R = 1 ,25318   ,392.9,375.7,362.9
XS GIS Cut Line= 6
1588712.90413526409096.9868940861589183.85824583408969.552437678
 1589340.7171841 408927.108624921589437.24586242  408900.9889265
 1589684.6003546408834.0579580071590022.22376481408708.202082319
#Sta/Elev= 30
       0  928.39    69.6     911    98.6  906.92   123.5   898.1   140.1  884.31
   166.1  869.11   206.4   839.7   235.4  830.69   254.1  808.55   305.8  760.75
   326.5   748.1   355.6  734.27   404.1  693.29   446.7  663.41   487.9  647.53
   546.2  642.13   558.6  638.62   575.2  630.01   612.5  626.92   633.2  619.13
   643.3609.2271   658.1  606.12   740.9  606.16   753.4  609.32   778.2  622.17
   840.4  629.69   873.8  643.82   898.4  649.42  1253.7   651.4    1367  668.24
#Mann= 9 ,-1,0
       0      .1       0  517.89     .06       0  615.39      .1       0
   643.3    .045       0   753.4    .025       0  820.39     .06       0
  922.89     .07       0 1186.64     .06       0 1336.64     .07       0
Bank Sta=643.3,753.4
XS Rating Curve= 0 ,0
Exp/Cntr(USF)=0,0
Exp/Cntr=0.3,0.1

Type RM Length L Ch R = 1 ,24942   ,200.5,181.2,165.8
XS GIS Cut Line= 4
1589135.00028253409393.8052840161589381.20216274409348.863670961
1589668.43768965 409165.189252391589959.58118292408834.966095596
#Sta/Elev= 30
       0  754.76    29.6  742.15    49.9  720.81    67.4  699.82    90.6  682.23
   102.8  669.06     119   666.3   163.8  642.03   180.8  635.88   208.5  630.53
   228.8  630.88     241  628.12   253.7  631.84   263.2   630.9   324.9  614.73
   334.4   608.5   343.9  606.14   419.9  606.12  433.46  608.62   458.2  619.55
   491.1  621.13   529.1   626.7   571.8  642.69   594.3  648.11   681.4  649.19
     748  645.64   775.7  641.98   850.8  641.28   899.2  642.93  1031.5  652.21
#Mann= 8 ,-1,0
       0     .06       0     180      .1       0   334.4    .045       0
  433.46      .1       0  590.27     .06       0  641.21     .07       0
  791.21     .06       0  861.21     .07       0
#XS Ineff= 2 , 0
          254.32  640.33
Permanent Ineff=
       F       F
Bank Sta=334.4,433.46
XS Rating Curve= 0 ,0
Exp/Cntr(USF)=0,0
Exp/Cntr=0.3,0.1

Type RM Length L Ch R = 1 ,24761   ,120.8,126.6,120.6
XS GIS Cut Line= 3
1589312.31462427409768.8162792181589443.53788415409596.349955334
1589987.68343387 408931.68894829
#Sta/Elev= 30
       0  642.59    31.5  641.48      80  636.75   100.9  635.41   302.3  630.39
   331.3  628.45   337.6  625.91   350.6  613.86   358.1608.9554   362.9     607
   369.2  606.11   413.1     606   457.6   606.2   464.3  606.91   468.4609.0248
   482.8   617.1   492.7  618.83   518.3  625.82   552.4   629.7   593.8  633.05
   615.4  635.71   643.4  637.47   653.3  637.13   707.6  639.25   743.8  642.09
   826.5  650.22   845.2  650.14   893.3  647.44   912.2  647.49  1075.7  653.74
#Mann= 8 ,-1,0
       0     .08       0     140     .07       0   358.1    .045       0
   468.4     .08       0  526.71     .07       0  906.71     .06       0
  936.71     .08       0 1036.71     .07       0
#XS Ineff= 2 , 0
          262.76  639.15
Permanent Ineff=
       F       F
Bank Sta=358.1,468.4
XS Rating Curve= 0 ,0
Exp/Cntr(USF)=0,0
Exp/Cntr=0.3,0.1

Type RM Length L Ch R = 1 ,24635   ,199.8,202.5,203.9
XS GIS Cut Line= 3
1589388.74869843409836.5159800771589500.14362926 409705.90946199
1590044.28917898409041.248454946
#Sta/Elev= 30
       0  647.42    63.1  646.22     110  643.76   126.1  644.72     147   643.9
   241.1  637.17   249.4  634.93   274.9  624.46   303.4   618.1   319.9608.0293
   323.3  606.42   329.5  605.97   417.1  605.97     431608.1075   443.1  617.01
   447.4  618.76   462.9  619.25   473.3  620.96   506.3  632.93   525.2  635.35
   569.4  636.19   597.3  638.24   657.8  646.99   692.8  648.82   752.4  647.38
   814.5  647.72   834.9  649.29   853.6  648.04   904.1  652.15  1030.7  655.89
#Mann= 14 ,-1,0
       0     .08       0      20     .07       0     110     .08       0
  171.66     .06       0  241.66     .07       0   319.9    .045       0
     431     .08       0  621.66     .07       0  641.66     .06       0
  751.66     .07       0  801.66     .06       0  871.66     .07       0
  951.66     .06       0 1001.66     .07       0
Bank Sta=319.9,431
XS Rating Curve= 0 ,0
Exp/Cntr(USF)=0,0
Exp/Cntr=0.3,0.1

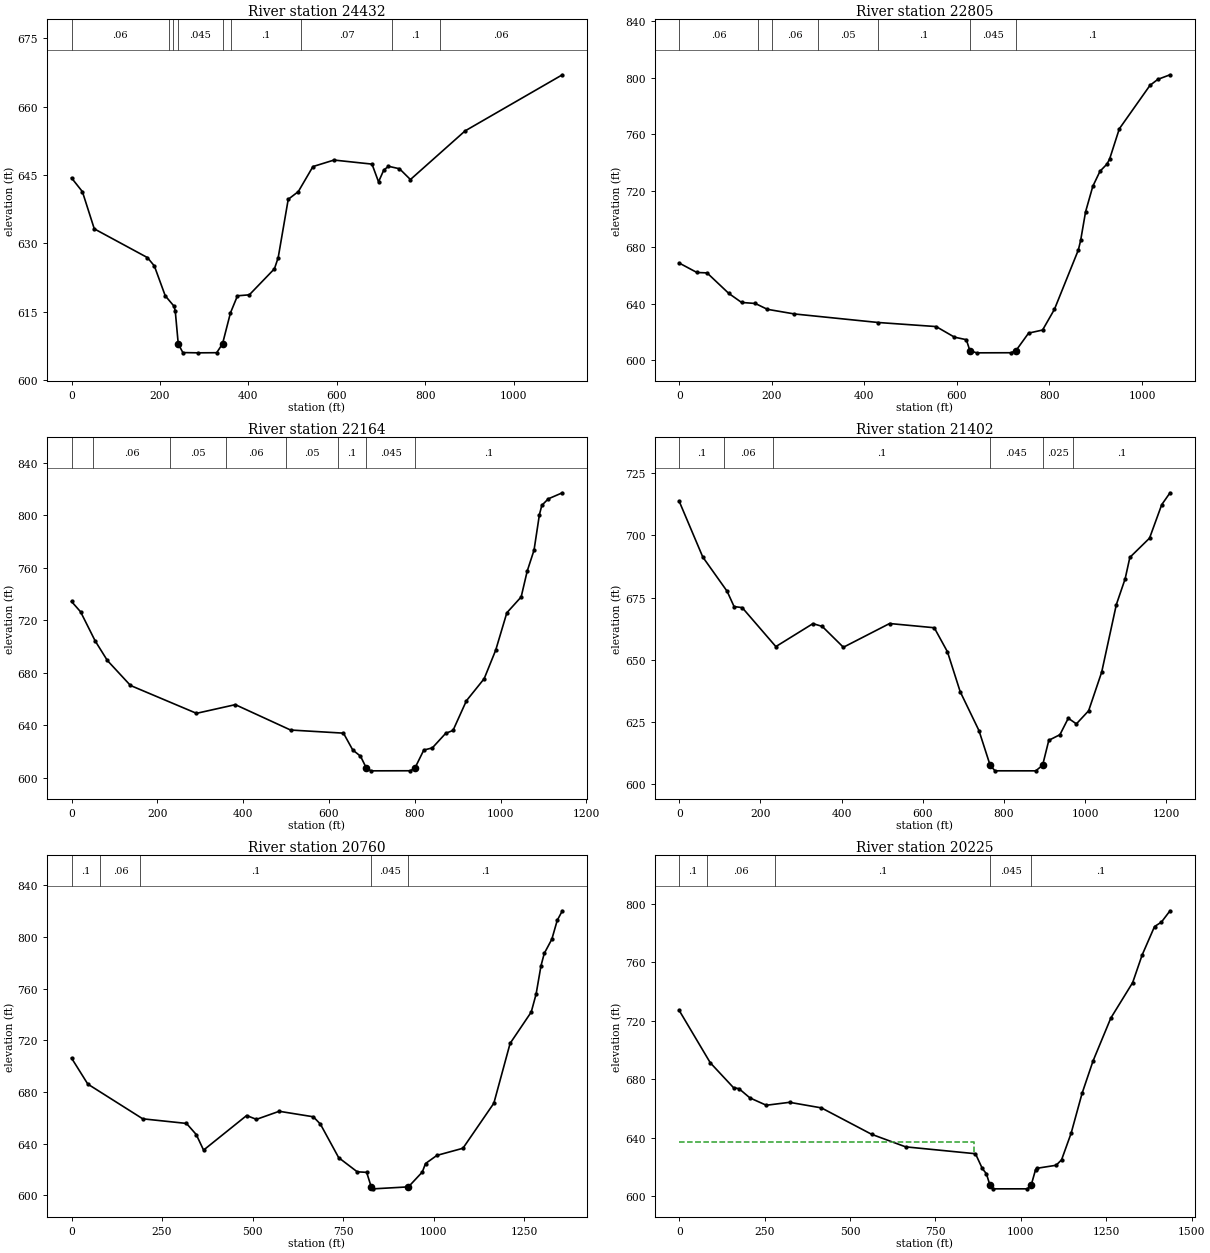
Type RM Length L Ch R = 1 ,24432   ,1608,1626.7,1606.9
XS GIS Cut Line= 4
1589560.86151555409931.9817103251589923.89602769409499.827085534
1590102.75438643409157.0866705681590248.79928014409093.589074429
#Sta/Elev= 30
       0  644.36    24.6  641.34    51.5  633.17   171.7  626.86   187.3  625.04
     212  618.47   231.9  616.18   234.7  615.08   241.4  607.92   251.8     606
   286.6  605.94   328.4  605.97  341.61  607.93   359.5  614.71   375.4  618.47
   402.2  618.68     459   624.4   467.5  626.85   490.2  639.66     513  641.35
   546.1  646.85   593.7  648.28   679.7  647.39   694.5  643.49   706.3  646.08
     717  646.91   741.9  646.37   766.6     644   890.2  654.68  1110.3  667.01
#Mann= 9 ,-1,0
       0     .06       0     220      .1       0     230     .06       0
   241.4    .045       0  341.61     .06       0     360      .1       0
     520     .07       0   724.4      .1       0   834.4     .06       0
Bank Sta=241.4,341.61
XS Rating Curve= 0 ,0
Exp/Cntr(USF)=0,0
Exp/Cntr=0.3,0.1

Type RM Length L Ch R = 1 ,22805   ,633.4,641.8,651.7
XS GIS Cut Line= 2
1590752.55441881409982.7767051391591431.82336008409168.384372332
#Sta/Elev= 30
       0  668.83    38.2  662.15    60.2  661.85   107.1  647.35   134.8  640.93
   164.4  640.22   190.4  636.09   249.1  632.79     430  626.75   555.1  623.87
   594.8  616.37   620.4  614.58     628  606.87   642.5  605.28     717  605.35
  727.64606.8767   754.9  619.24   785.1  621.42   810.7  636.06   862.4  678.09
   867.4  684.92     878  705.08   893.6  723.11   909.2  733.81   924.3  738.89
     930  742.49   950.9  763.83  1017.2  794.59  1034.2  798.82  1060.5  802.06
#Mann= 7 ,-1,0
       0     .06       0     170     .05       0     200     .06       0
     300     .05       0     430      .1       0     628    .045       0
  727.64      .1       0
Bank Sta=628,727.64
XS Rating Curve= 0 ,0
Exp/Cntr(USF)=0,0
Exp/Cntr=0.3,0.1

Type RM Length L Ch R = 1 ,22164   ,757.7,761.9,765.9
XS GIS Cut Line= 2
1591099.47935897410377.6333032561591966.13663612 409631.20593738
#Sta/Elev= 30
       0  734.31    21.1  726.44    55.1  704.24    83.5  689.31   137.4  670.24
   291.2  648.99   381.7  655.61   510.4  636.26   633.7  633.87   655.4  621.01
   673.4  616.31   686.9607.3613   697.7  605.12   789.7  605.18   800.4  607.33
   820.9  620.97   840.8  622.63   871.9  633.73     889  635.95   920.2  658.57
   961.6  675.41   988.5  697.21  1014.4  725.68  1047.8  737.77  1061.9   757.5
  1077.8  773.48  1090.4  800.67    1096  807.68  1111.1  812.63  1143.8  817.24
#Mann= 8 ,-1,0
       0      .1       0      50     .06       0     230     .05       0
     360     .06       0     500     .05       0     620      .1       0
   686.9    .045       0   800.4      .1       0
Bank Sta=686.9,800.4
XS Rating Curve= 0 ,0
Exp/Cntr(USF)=0,0
Exp/Cntr=0.3,0.1

Type RM Length L Ch R = 1 ,21402   ,631,641.9,651.5
XS GIS Cut Line= 2
1591481.68640245410979.4776492051592448.53527234410253.088601876
#Sta/Elev= 30
       0  713.79    58.1  691.32   118.1   677.5   135.2  671.34   155.2  670.93
   238.1  655.21   329.5  664.47   352.4  663.35   404.5  654.94   518.4  664.51
   628.4  662.81   660.9  653.11   692.3  637.03   738.5  621.37  766.01  607.39
     778  605.13   878.6  605.12   895.4 607.414   910.6  617.43     938  619.69
   958.6  626.33   978.6  624.05  1008.7  629.33  1040.9  644.92    1077  672.14
  1098.7  682.54  1110.3  691.17  1158.8  698.93  1188.8  712.42  1209.3  717.22
#Mann= 6 ,-1,0
       0      .1       0     110     .06       0     230      .1       0
  766.01    .045       0   895.4    .025       0     970      .1       0
Bank Sta=766.01,895.4
XS Rating Curve= 0 ,0
Exp/Cntr(USF)=0,0
Exp/Cntr=0.3,0.1

Type RM Length L Ch R = 1 ,20760   ,508.8,535.1,566.5
XS GIS Cut Line= 2
1591697.33108082411426.3471924231592904.63977328410810.168897103
#Sta/Elev= 30
       0  706.33      45  686.18   196.7  659.31   317.5  655.74   344.4  647.16
   364.7   635.1   483.6  661.86   510.6  658.89   573.5  665.14   667.8  660.88
   687.3  655.21   737.8  629.24     789  618.31   815.1  617.88   827.6606.6872
   833.9  605.12   930.4606.6445   968.7  618.12   977.6   624.7  1009.1  631.01
  1080.9  636.52  1166.3  671.38  1211.2  717.68  1269.5   741.9    1283  755.84
  1296.5  777.75  1305.5  787.31  1326.5  798.34  1341.4  812.94  1355.5  820.31
#Mann= 5 ,-1,0
       0      .1       0      80     .06       0     190      .1       0
   827.6    .045       0   930.4      .1       0
Bank Sta=827.6,930.4
XS Rating Curve= 0 ,0
Exp/Cntr(USF)=0,0
Exp/Cntr=0.3,0.1

Type RM Length L Ch R = 1 ,20225   ,602,637.6,677.3
XS GIS Cut Line= 2
1591689.17899188411505.8026321681593125.50412414411538.670484165
#Sta/Elev= 30
       0  727.12      91  691.32     159   674.3     175  673.62     207  667.31
     255  662.28     323  664.29   416.3  660.48   563.1  642.43   662.7  633.84
   867.2  629.13   887.2  619.03   899.2  615.42   909.2   607.9   919.2  605.12
  1019.2  605.12  1030.5607.8463  1043.2  618.33  1047.2  619.18  1103.2  621.24
  1119.2  624.95  1147.2  643.17  1179.2  670.41  1211.3  692.56  1263.3  721.88
  1327.3  746.17    1355  765.02  1391.3   784.5  1411.3  787.49  1436.7  795.28
#Mann= 5 ,-1,0
       0      .1       0      80     .06       0     280      .1       0
   909.2    .045       0  1030.5      .1       0
#XS Ineff= 2 , 0
          863.13  636.96
Permanent Ineff=
       F       F
Bank Sta=909.2,1030.5
XS Rating Curve= 0 ,0
Exp/Cntr(USF)=0,0
Exp/Cntr=0.3,0.1

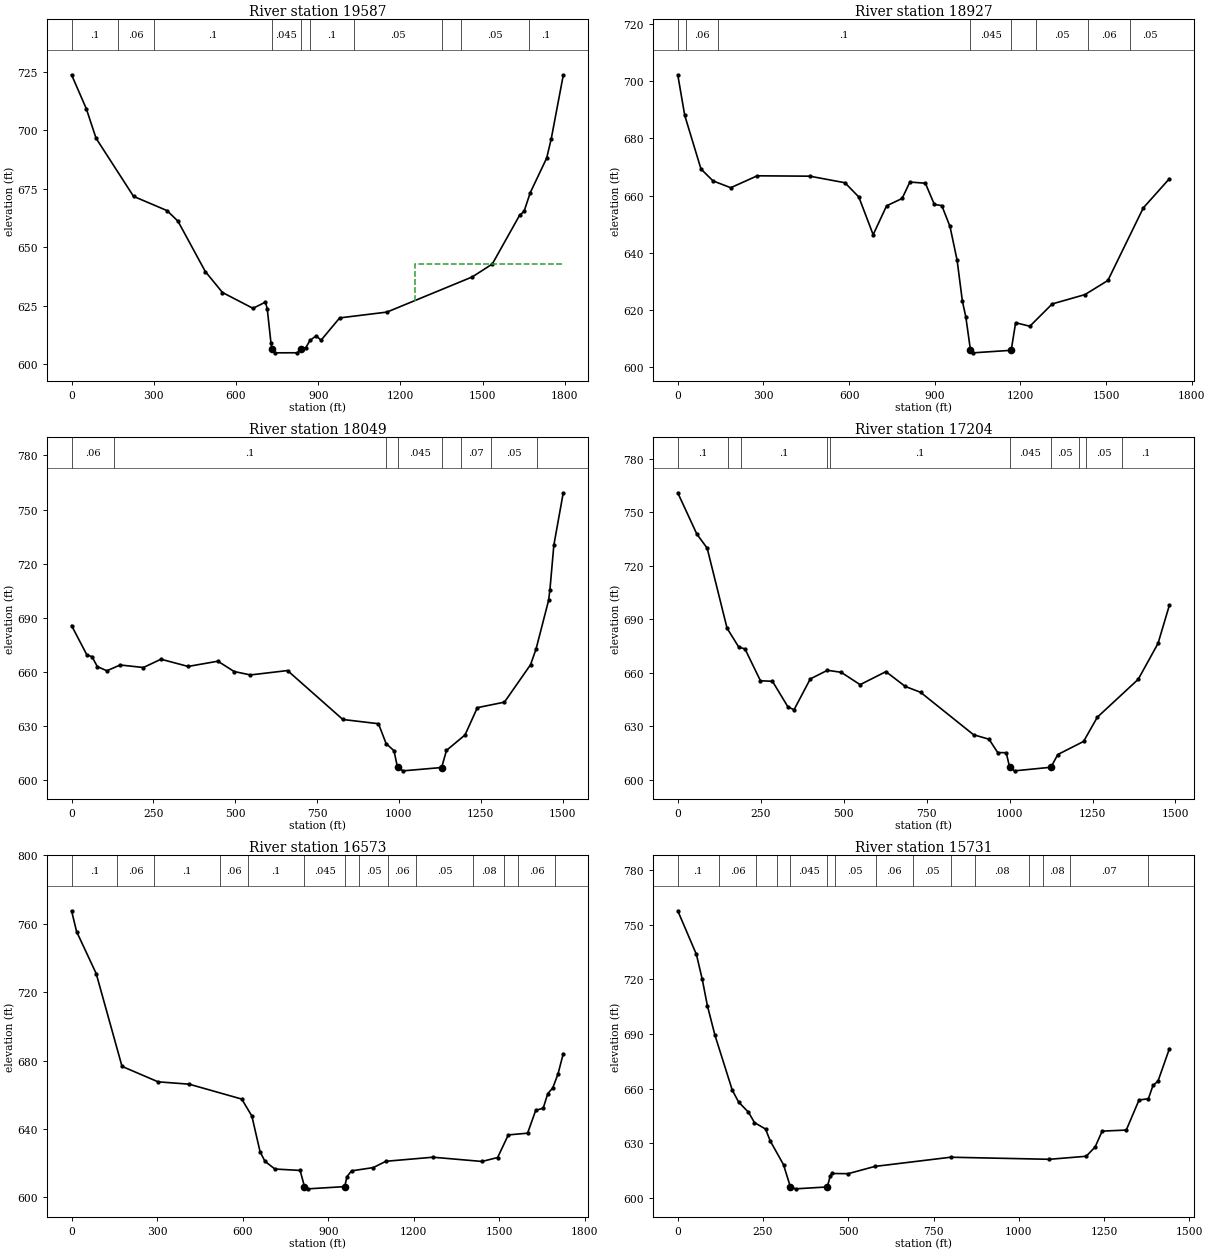
Type RM Length L Ch R = 1 ,19587   ,657.6,660.3,663.2
XS GIS Cut Line= 2
1591729.49493448411590.3242340131593146.09935554412691.397275902
#Sta/Elev= 30
       0  723.64      54   709.1    89.4  696.55   226.2  671.75   348.4  665.68
   388.2  661.17     488  639.68   550.7  630.72   661.9  623.97   707.5  626.62
   714.1  623.72   727.8  608.99  731.36  606.73     743  604.97   824.4     605
   835.7 606.625   854.4  607.11     870  610.24   892.8  612.29   910.2  610.32
   978.3  619.88  1150.8  622.36  1462.4  637.38  1535.3  642.88  1634.6  663.62
  1651.1  665.32  1673.9  673.36  1733.7  688.08  1750.4  696.33  1794.2  723.44
#Mann= 10 ,-1,0
       0      .1       0     170     .06       0     300      .1       0
  731.36    .045       0   835.7    .025       0     870      .1       0
    1030     .05       0    1350     .06       0    1420     .05       0
    1670      .1       0
#XS Ineff= 2 , 0
                         1252.88          642.89
Permanent Ineff=
       F       F
Bank Sta=731.36,835.7
XS Rating Curve= 0 ,0
Exp/Cntr(USF)=0,0
Exp/Cntr=0.3,0.1

Type RM Length L Ch R = 1 ,18927   ,764.2,878.2,965.6
XS GIS Cut Line= 3
1591699.77475778411696.8896058311591552.54978833412263.692426729
1592422.29807631412995.396182681
#Sta/Elev= 30
       0  702.29    24.4  688.08    81.4  669.29   123.6  665.14   185.6  662.76
   278.3  666.93   462.5   666.8   585.6   664.5   634.2  659.51   684.4  646.31
   731.4  656.42   785.8  658.99     813  664.74   867.3  664.34   898.7   656.9
   924.8  656.51   953.5  649.19   978.4  637.41     997  623.02  1008.9  617.56
 1025.29605.8889  1034.3  604.97  1167.9  605.86  1183.4  615.51  1233.2  614.28
  1311.6  622.09  1426.2  625.35  1506.5  630.29  1630.6   655.7  1722.2  665.94
#Mann= 8 ,-1,0
       0      .1       0      30     .06       0     140      .1       0
 1025.29    .045       0  1167.9      .1       0 1255.61     .05       0
 1435.61     .06       0 1585.61     .05       0
Bank Sta=1025.29,1167.9
XS Rating Curve= 0 ,0
Exp/Cntr(USF)=0,0
Exp/Cntr=0.3,0.1

Type RM Length L Ch R = 1 ,18049   ,819.7,844.9,862.6
XS GIS Cut Line= 4
 1591645.6720954 411704.474663711591476.30091516412342.051280572
1591291.65382335412443.3093631731590956.89597073412979.058356121
#Sta/Elev= 30
       0  685.61    47.1  669.21    62.1  668.39    78.7  662.85   107.7   660.5
   148.5  663.72   219.4  662.32   273.2  666.92     356  662.91     447  665.82
   496.7  660.08   546.4   658.2   659.7  660.63   828.7  633.47   937.6  631.12
   960.8  620.11   984.9  616.13   995.7  606.86  1012.8  604.97 1130.48  606.81
  1145.3  616.33  1201.9  624.87  1239.6  640.04  1322.3  643.09  1402.1  663.88
  1418.9  672.59  1457.2  699.58  1461.3  705.51  1473.3  730.27    1502   759.3
#Mann= 8 ,-1,0
       0     .06       0     130      .1       0  960.28    .025       0
   995.7    .045       0 1130.48     .06       0 1190.28     .07       0
 1280.28     .05       0 1420.28      .1       0
Bank Sta=995.7,1130.48
XS Rating Curve= 0 ,0
Exp/Cntr(USF)=0,0
Exp/Cntr=0.3,0.1

Type RM Length L Ch R = 1 ,17204   ,588.4,630.5,668
XS GIS Cut Line= 2
1591416.53896478411339.7601050891590272.25078416412281.160310427
#Sta/Elev= 30
       0  760.85    57.5  737.69    88.6  729.82   148.6  684.92   183.8  674.36
   202.6  673.31   249.2  655.46   285.4  655.17   332.1   640.8   350.4  639.21
   399.4  656.51   451.2  661.34   492.5  660.21   549.6  653.28   627.3  660.58
   685.7  652.27   731.6  649.02   891.5   625.2   938.1  622.69   964.2  615.22
   989.9  615.13  1000.2  606.96  1014.9  604.97 1124.72606.9811  1145.3  614.12
    1223  621.45  1264.4  635.03  1387.6  656.27  1447.3  676.37  1481.8  697.95
#Mann= 10 ,-1,0
       0      .1       0     150     .06       0     190      .1       0
     450     .07       0     460      .1       0  1000.2    .045       0
 1124.72     .05       0    1210     .06       0    1230     .05       0
    1340      .1       0
Bank Sta=1000.2,1124.72
XS Rating Curve= 0 ,0
Exp/Cntr(USF)=0,0
Exp/Cntr=0.3,0.1

Type RM Length L Ch R = 1 ,16573   ,903.8,842.1,793.3
XS GIS Cut Line= 4
1591181.18891345411120.6410917771590913.37678607411388.453219158
 1589809.6662005411473.6661687791589647.35582027411648.149827527
#Sta/Elev= 30
       0  767.65    17.7  755.45    86.4  730.89   176.9  676.62   303.3  667.58
   412.1  666.21   596.7  657.49   632.2  647.55   660.8  626.76   677.9   621.1
     713  616.56   801.3  615.74  816.72606.2509   829.3  604.97   957.7  606.27
   965.7  612.13   981.8  615.49  1057.8   617.4  1102.2  621.09  1266.9  623.47
  1439.2  620.99  1493.9  623.29  1531.3  636.52  1598.9  637.53  1627.6  650.95
  1653.6  652.11  1669.9  660.73    1687  663.95  1705.3  672.01    1724  684.01
#Mann= 14 ,-1,0
       0      .1       0     160     .06       0     290      .1       0
  518.74     .06       0  618.74      .1       0  816.72    .045       0
   957.7      .1       0 1008.74     .05       0 1108.74     .06       0
 1208.74     .05       0 1408.74     .08       0 1515.74     .07       0
 1565.74     .06       0 1695.74      .1       0
Bank Sta=816.72,957.7
XS Rating Curve= 0 ,0
Exp/Cntr(USF)=0,0
Exp/Cntr=0.3,0.1

Type RM Length L Ch R = 1 ,15731   ,524.5,530.8,541.5
XS GIS Cut Line= 2
1590333.03986842410346.6072313041589603.24925467411589.725141164
#Sta/Elev= 30
       0  757.71    54.7  733.71    71.8  720.06    86.8   705.6   108.9  689.42
   159.9  659.12   178.5   652.6   207.3  647.04   224.9  641.34   257.3   637.8
   271.3   631.2     310  618.22  330.13606.0411   345.5  604.94  438.25605.9807
   447.5  612.25   452.2  613.37   499.6  613.27   577.8  617.25     800  622.31
  1089.3  621.17  1197.4  622.83  1223.7  627.97  1244.2  636.65  1314.9  637.23
  1352.3  653.74  1379.8  654.46  1393.2  661.72  1407.9   664.1  1441.5  682.01
#Mann= 15 ,-1,0
       0      .1       0     120     .06       0     230     .05       0
     290     .06       0  330.13    .045       0  438.25    .025       0
     460     .05       0     580     .06       0     690     .05       0
     800     .06       0     870     .08       0    1030     .05       0
    1070     .08       0    1150     .07       0    1380     .06       0
Bank Sta=330.13,438.25
XS Rating Curve= 0 ,0
Exp/Cntr(USF)=0,0
Exp/Cntr=0.3,0.1