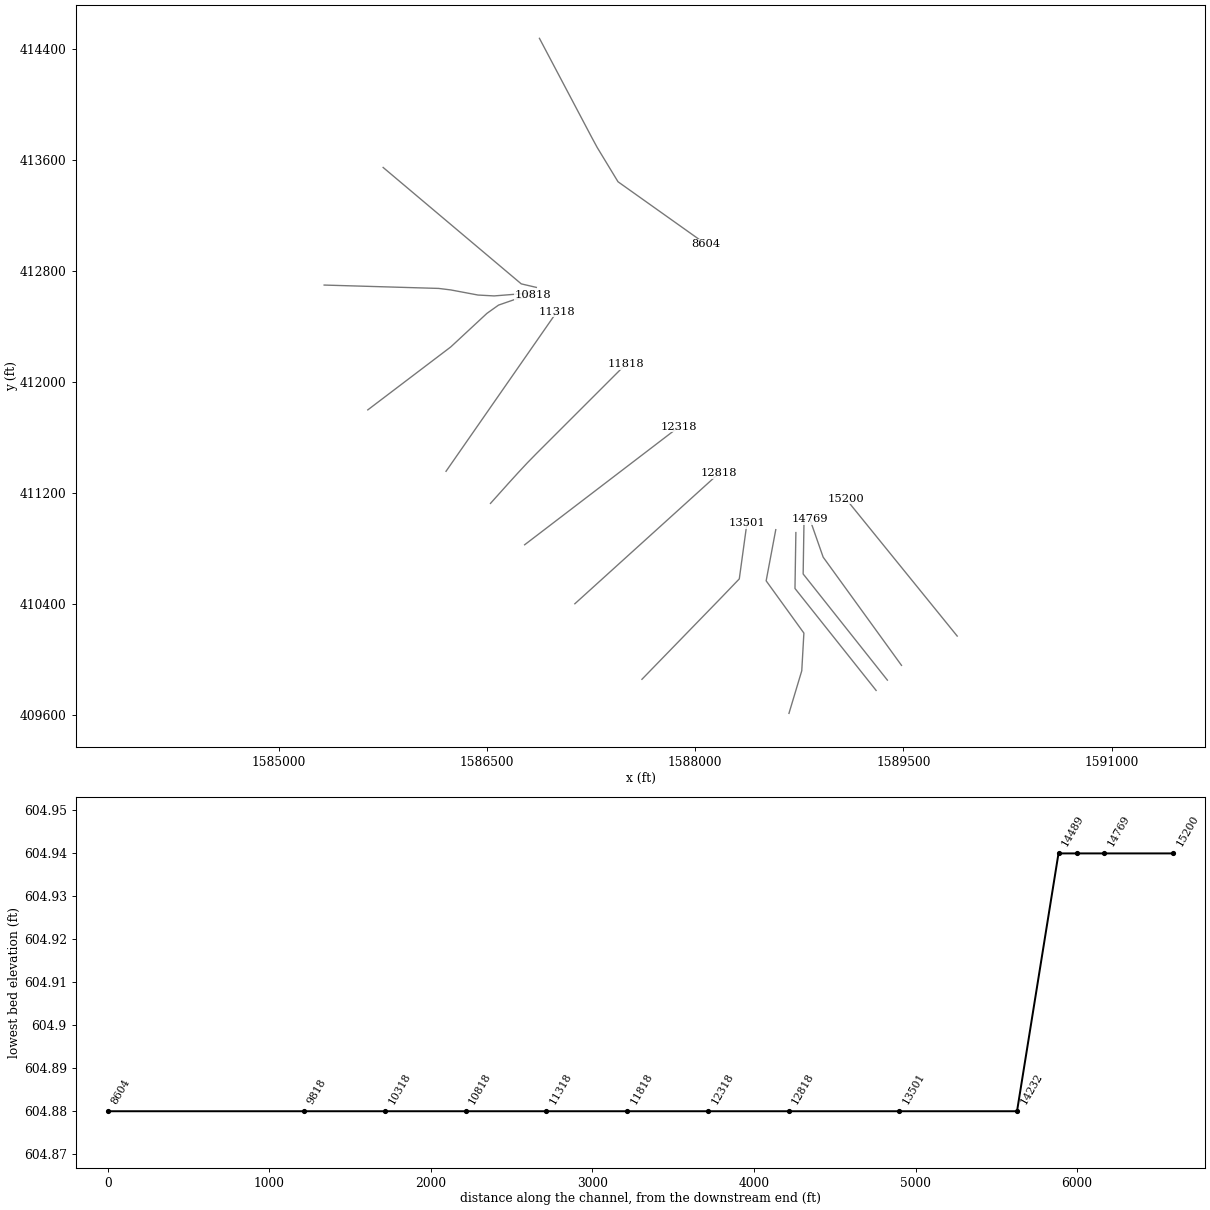
HEC-RAS study FISHINGCK.prj: FISHINGCK

--- FISHINGCK.g01 (geometry) --- (continued)

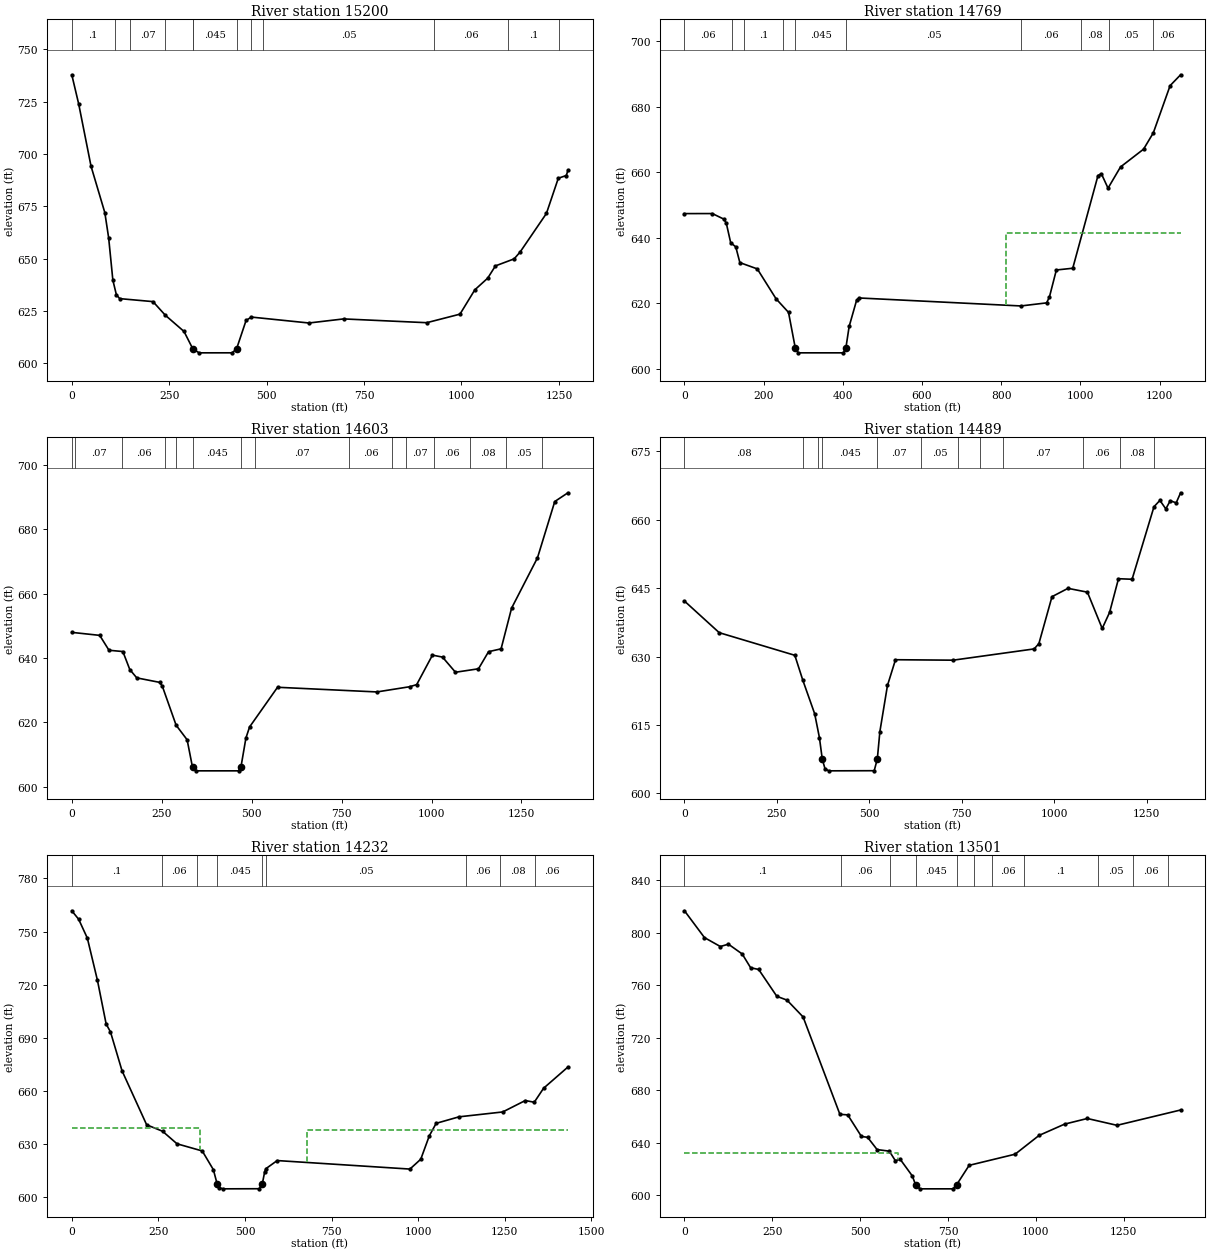
Type RM Length L Ch R = 1 ,15200   ,433.3,431.5,428.6
XS GIS Cut Line= 2
1589887.24308635410166.636850863 1589085.7085182411155.686386789
#Sta/Elev= 30
       0  737.89    17.7  723.95    49.4  694.16    84.8  671.97    94.6  659.93
   105.4  639.68   114.5  632.66     123  630.86   208.4  629.43     240  622.92
     288  615.16   310.7   606.8   326.8  604.94   411.6  604.95   422.9606.8804
   447.2  620.42   460.7  622.04   608.5  619.21   697.5  621.16   910.8  619.35
   996.1  623.44  1034.2  635.07  1067.2  640.64  1087.1  646.51  1135.1  649.87
  1150.6  653.19  1217.9  671.58  1248.4  688.42    1269  689.73  1273.1   692.2
#Mann= 12 ,-1,0
       0      .1       0     110     .08       0     150     .07       0
     240    .025       0     310     .07       0   310.7    .045       0
   422.9    .025       0     460     .07       0     490     .05       0
     930     .06       0    1120      .1       0    1250     .06       0
Bank Sta=310.7,422.9
XS Rating Curve= 0 ,0
Exp/Cntr(USF)=0,0
Exp/Cntr=0.3,0.1

Type RM Length L Ch R = 1 ,14769   ,162.1,165.4,169.3
XS GIS Cut Line= 3
1589486.10347957409955.5283554681588921.93256018410735.453306575
1588825.98077413411009.514588787
#Sta/Elev= 30
       0  647.44    70.4  647.45     100  645.72   105.8  644.43   116.7  638.57
   129.6  637.27   139.9  632.48   183.9  630.56   231.3  621.44   262.8  617.29
     280  606.33   287.6  604.94   401.1  604.94  407.55  606.36   415.9  612.99
   434.7  620.98   440.4  621.69   849.7  619.25   914.6  620.19   921.7  621.99
   939.2  630.23   980.6  630.76  1044.3  659.03  1052.8  659.63  1069.7   655.2
  1101.2  661.67  1159.5  667.11  1184.1  672.09  1226.5   686.5    1253  689.81
#Mann= 10 ,-1,0
       0     .06       0     120     .07       0     150      .1       0
     250    .025       0     280    .045       0  407.55     .05       0
     850     .06       0 1002.59     .08       0 1072.59     .05       0
 1182.59     .06       0
#XS Ineff= 2 , 0
                          811.07          641.55
Permanent Ineff=
       F       F
Bank Sta=280,407.55
XS Rating Curve= 0 ,0
Exp/Cntr(USF)=0,0
Exp/Cntr=0.3,0.1

Type RM Length L Ch R = 1 ,14603   ,114,114.7,118.8
XS GIS Cut Line= 3
1589384.35607887409849.2822479321588777.90103274410614.182347308
1588784.35956566411017.058217166
#Sta/Elev= 30
       0  647.99    77.6  647.06   103.4  642.43     142  642.03   161.3  636.42
   180.7  633.84   244.1  632.45   251.5  631.31     290  619.13   320.6   614.6
   335.6  606.04   346.2  604.94   463.7  604.94   470.2606.1118     484  615.13
   494.2  618.58   571.9  630.92   848.1  629.47   939.2  631.09   958.7  631.75
  1002.5  640.92  1030.5   640.3  1066.5  635.59  1130.5  636.67  1158.5  641.99
  1193.3  642.87  1222.5  655.52  1294.5  671.18  1342.5  688.67  1379.1  691.39
#Mann= 15 ,-1,0
       0     .08       0      10     .07       0     140     .06       0
     260    .025       0     290      .1       0   335.6    .045       0
   470.2     .08       0     510     .07       0     770     .06       0
     890     .05       0     930     .07       0 1006.15     .06       0
 1106.15     .08       0 1206.15     .05       0 1306.15     .06       0
Bank Sta=335.6,470.2
XS Rating Curve= 0 ,0
Exp/Cntr(USF)=0,0
Exp/Cntr=0.3,0.1

Type RM Length L Ch R = 1 ,14489   ,303.3,256.8,201.9
XS GIS Cut Line= 3
1589303.27796852409774.9533860991588719.01845849410509.634275086
 1588725.4769914410912.510144944
#Sta/Elev= 30
       0  642.16      94  635.23   298.4  630.27     320  624.81   352.1  617.45
   364.9  612.23   372.6607.5272   380.2  605.34   390.5  604.94   513.1  604.97
  521.52  607.56   528.4  613.55   548.9  623.65   570.6   629.3   726.5   629.2
   945.6  631.67   958.4  632.84   993.8  643.12  1037.1  644.95  1089.6  644.11
  1129.6  636.15  1149.6  639.68  1173.6  647.06  1210.4  646.94  1269.6  662.84
  1285.6  664.23  1301.6  662.37  1313.6  664.16  1329.6  663.69  1341.6   665.9
#Mann= 12 ,-1,0
       0     .08       0     320     .07       0     360    .025       0
   372.6    .045       0  521.52     .07       0     640     .05       0
     740     .07       0     800     .05       0     860     .07       0
 1078.68     .06       0 1178.68     .08       0 1268.68     .05       0
Bank Sta=372.6,521.52
XS Rating Curve= 0 ,0
Exp/Cntr(USF)=0,0
Exp/Cntr=0.3,0.1

Type RM Length L Ch R = 1 ,14232   ,776.4,731.2,688.5
XS GIS Cut Line= 5
1588675.68710109409609.5548753931588767.93136336409916.760884855
1588783.14544357410188.2196616091588511.38161211410564.714927988
1588580.65453443410933.459555933
#Sta/Elev= 30
       0  761.73    19.8  756.96    44.9   746.3    74.1  722.46    99.2  697.85
   111.7   693.4   145.1  671.44   216.1  641.01   262.1  637.35   303.8  630.28
   376.6  626.25   408.7  615.69   419.4   607.8   424.7   605.5   436.7  604.88
   540.9  604.94  550.04  607.74   556.9  614.57   560.9  616.34     593  620.83
   976.1  616.03  1007.4  621.59  1032.1   634.8  1051.8  641.83  1117.8   645.5
    1244  648.25  1309.1  654.69    1335  653.73    1362  661.64  1432.2  673.59
#Mann= 9 ,-1,0
       0      .1       0     260     .06       0  360.76      .1       0
   419.4    .045       0  550.04    .025       0  560.76     .05       0
 1136.97     .06       0 1236.97     .08       0 1336.97     .06       0
#XS Ineff= 2 , 0
          368.77  639.29  679.59          638.25
Permanent Ineff=
       F       F
Bank Sta=419.4,550.04
XS Rating Curve= 0 ,0
Exp/Cntr(USF)=0,0
Exp/Cntr=0.3,0.1

Type RM Length L Ch R = 1 ,13501   ,686.3,682.6,678.9
XS GIS Cut Line= 6
1587616.95916873409855.1763185881587686.35010607409926.638774084
1587824.04438448410068.4426243331588191.95375365410447.333926918
1588317.97665208410578.693873324 1588372.9667869410979.718708974
#Sta/Elev= 30
       0  816.67    56.9  796.25   102.1  789.45   125.1  791.24   164.4  783.75
   188.3  773.29   211.2  771.98   262.9  751.52   291.8  748.63   337.6  735.82
   442.4  661.65   464.7  661.21   503.7  644.79   521.3  644.11   548.3  634.79
   583.1  633.57   600.1  626.39   614.2  627.33   648.7  614.65     658  607.77
   670.6  604.88   764.1  604.88   774.6607.9629   810.3  622.78   941.2  631.27
  1009.3  645.57  1081.9  654.16  1146.6  658.46  1231.1  653.26  1412.2  664.93
#Mann= 11 ,-1,0
       0      .1       0  444.14     .06       0  585.39      .1       0
     658    .045       0   774.6      .1       0  825.39     .05       0
  875.39     .06       0  965.39      .1       0 1177.43     .05       0
 1277.43     .06       0 1377.43     .07       0
#XS Ineff= 2 , 0
          608.86  632.08
Permanent Ineff=
       F       F
Bank Sta=658,774.6
XS Rating Curve= 0 ,0
Exp/Cntr(USF)=0,0
Exp/Cntr=0.3,0.1

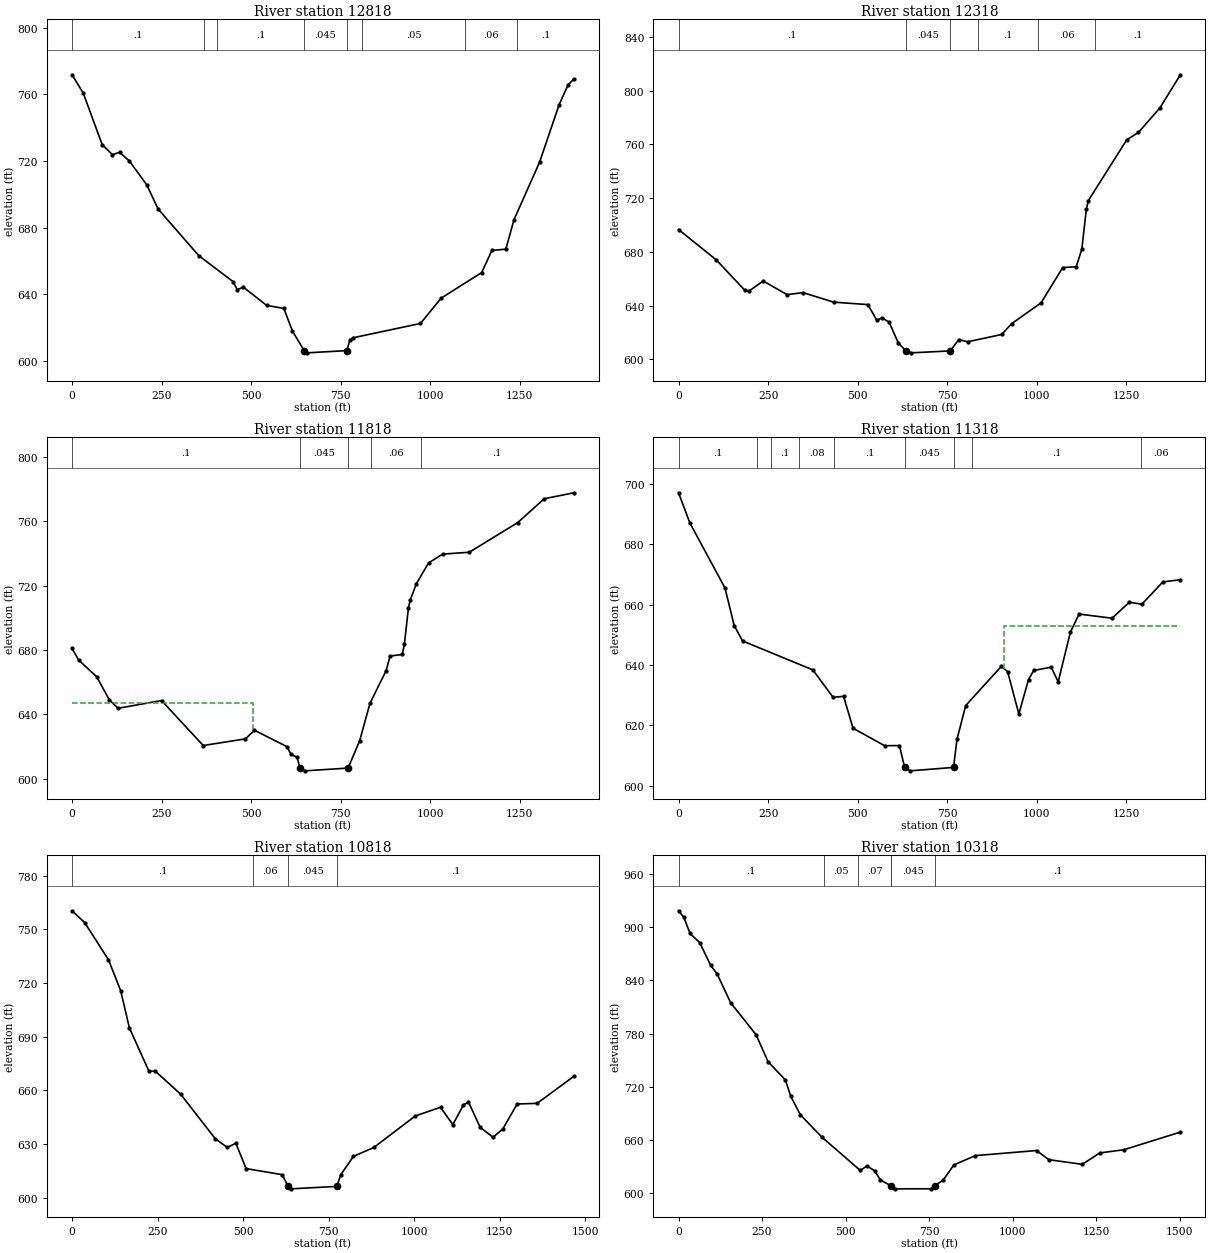
Type RM Length L Ch R = 1 ,12818   ,505.2,500,494.9
XS GIS Cut Line= 6
1587133.85742459410399.5495776681587354.15652467410599.137105003
1587425.94936009410664.179953918 1587615.8521955410836.229150504
 1588024.6072835411206.5541972521588171.95574209411340.049665168
#Sta/Elev= 30
       0  771.77    31.3  760.73      84  729.89   112.7  723.81   132.5  725.21
   159.6  720.13   208.2  705.83   240.2  691.21   353.9  663.18   449.7   647.6
   461.1  642.75   478.1  644.34   542.8   633.4   591.3  631.51   615.1     618
     648  606.18   656.1  604.88  766.95606.2189   775.4  612.44   783.9  613.89
   972.6  622.51  1030.3   637.7  1143.5  653.06  1171.9  666.31  1210.9  667.12
  1233.7  684.77    1305  719.26  1359.8  753.91  1384.8  765.71  1400.8  769.27
#Mann= 8 ,-1,0
       0      .1       0  367.27     .06       0  404.14      .1       0
     648    .045       0  766.95    .025       0  810.39     .05       0
 1096.64     .06       0 1241.95      .1       0
Bank Sta=648,766.95
XS Rating Curve= 0 ,0
Exp/Cntr(USF)=0,0
Exp/Cntr=0.3,0.1

Type RM Length L Ch R = 1 ,12318   ,491.3,500,508.8
XS GIS Cut Line= 6
1586772.22855468410824.5854730011586930.16918367410945.363446668
1587229.29456967411174.1067555841587427.88406751411325.968984678
1587727.00912543411554.7119655011587884.95008251411675.490267262
#Sta/Elev= 30
       0  696.62   105.6  673.97   185.4   651.3   196.2  650.72   236.5  658.35
   302.8  648.15   347.3   649.7   432.9  642.59   528.6  640.77   553.5  629.08
   567.7  630.93   587.7  627.76   613.4  612.29  634.48606.4008   649.4  604.88
   758.9  606.32   781.7  614.69   807.4  613.12   902.1  618.54   930.1  626.61
    1012  642.03  1072.4  668.32  1109.9  668.88  1125.9  681.95  1138.4  711.73
  1144.1  718.17  1251.1   763.3    1284  768.88  1343.9   787.1  1400.8  811.73
#Mann= 6 ,-1,0
       0      .1       0  634.48    .045       0   758.9    .025       0
  835.39      .1       0 1002.89     .06       0 1163.52      .1       0
Bank Sta=634.48,758.9
XS Rating Curve= 0 ,0
Exp/Cntr(USF)=0,0
Exp/Cntr=0.3,0.1

Type RM Length L Ch R = 1 ,11818   ,488.4,500,512.2
XS GIS Cut Line= 6
1586526.21231443411122.7531837521586659.11624809411271.034383252
1586725.41598426411343.9466390011586791.47195451 411414.89236325
1586857.04039292411481.9066649231587502.55156909412127.417841092
#Sta/Elev= 30
       0  681.01    18.5  673.76    68.9  663.39   104.3  648.92   128.8   643.8
   249.8  648.62   366.2  620.63   483.9  624.75   509.4  630.11   599.9  619.97
   611.5  615.06   628.2  613.35  636.83606.5497   650.5  604.88  770.76606.5924
   803.2  623.59   831.8  646.81   877.1  667.23   888.1  676.28     922  677.26
     928  683.54   939.3  706.28   944.6  711.22   961.6  721.33   995.5  734.19
  1035.1  739.71  1109.3  740.85  1244.4  759.29  1318.6  774.14  1401.3  777.85
#Mann= 5 ,-1,0
       0      .1       0  636.83    .045       0  770.76      .1       0
  835.87     .06       0  973.37      .1       0
#XS Ineff= 2 , 0
          505.78  646.89
Permanent Ineff=
       F       F
Bank Sta=636.83,770.76
XS Rating Curve= 0 ,0
Exp/Cntr(USF)=0,0
Exp/Cntr=0.3,0.1

Type RM Length L Ch R = 1 ,11318   ,520.7,500,477.2
XS GIS Cut Line= 6
1586206.11157668411354.1621697551586534.40521142411826.706172168
1586577.19712059 411888.300209091586634.25278075411970.426029086
1586780.45852509 412180.873114751587005.33865276412504.564068422
#Sta/Elev= 30
       0  697.09    31.6  687.08   129.5  665.57   155.5     653   178.8  647.95
   375.1  638.34   431.4  629.25   460.7  629.59   487.2  619.01   575.4  613.21
   616.6  613.26   631.2  606.02   646.9  604.88   767.7  606.02   777.3  615.33
   801.7  626.54   900.9   639.5   918.6  637.81     950  623.75     977  635.15
   991.6  638.16  1040.3  639.26  1059.8  634.39  1093.9  650.86  1118.2  656.87
  1210.2  655.49  1258.4  660.79  1293.5  660.14    1352  667.52  1400.8  668.26
#Mann= 9 ,-1,0
       0      .1       0  218.83     .08       0  258.83      .1       0
  337.27     .08       0  434.14      .1       0   631.2    .045       0
   767.7    .025       0  820.39      .1       0 1291.95     .06       0
#XS Ineff= 2 , 0
                          909.23          652.99
Permanent Ineff=
       F       F
Bank Sta=631.2,767.7
XS Rating Curve= 0 ,0
Exp/Cntr(USF)=0,0
Exp/Cntr=0.3,0.1

Type RM Length L Ch R = 1 ,10818   ,543.6,500,450.5
XS GIS Cut Line= 6
  1585642.696693411796.6767046751586240.34247933412250.444826007
1586500.35705118412491.9453272521586584.37624009412551.814630091
1586700.51216267412592.086859256  1586832.635258412623.066128001
#Sta/Elev= 30
       0  760.38    36.9  753.77   106.5  732.97   142.4  715.52   167.5  694.95
   224.7  670.69   243.6  670.65   317.3  657.85   418.6  632.95   453.8  628.02
   478.9  630.38     509  616.19   614.7   612.8   631.8   606.2   639.6  604.88
   774.3 606.239   785.8  612.82   822.8  623.03   882.3  628.01  1003.7  645.64
  1077.4  650.49  1113.4   640.8  1144.5   651.8  1159.2  653.41  1193.6  639.21
    1231  633.76  1259.2  638.25  1301.5  652.33  1359.9  652.68  1467.3  667.81
#Mann= 4 ,-1,0
       0      .1       0  527.89     .06       0   631.8    .045       0
   774.3      .1       0
Bank Sta=631.8,774.3
XS Rating Curve= 0 ,0
Exp/Cntr(USF)=0,0
Exp/Cntr=0.3,0.1

Type RM Length L Ch R = 1 ,10318   ,542,500,452.7
XS GIS Cut Line= 6
1585328.22816184412696.1722810121586153.26194485412671.905925334
1586240.48158668412661.0817999991586436.57371417412624.207858011
1586552.48457159 412617.946059511586824.66250493412639.598903343
#Sta/Elev= 30
       0  918.63    15.9  911.06    34.5   893.1    63.9   882.4    95.9  857.26
   115.9  847.13     156  814.82     232  778.84     268  748.32     320  727.68
     336  709.16   364.9  688.36   428.1  663.59   544.1  625.59   564.1  630.82
   588.1  624.91   604.1  614.78   636.2  608.35   648.2  604.88   756.2  604.95
  766.67608.2781   792.2   614.8   824.2  631.88   888.7  642.38  1071.7   648.1
  1108.3  637.76  1208.5  632.54  1260.6  645.36  1332.7  648.97    1502   668.9
#Mann= 6 ,-1,0
       0      .1       0  434.14     .05       0  537.89     .07       0
  635.39    .025       0   636.2    .045       0  766.67      .1       0
Bank Sta=636.2,766.67
XS Rating Curve= 0 ,0
Exp/Cntr(USF)=0,0
Exp/Cntr=0.3,0.1

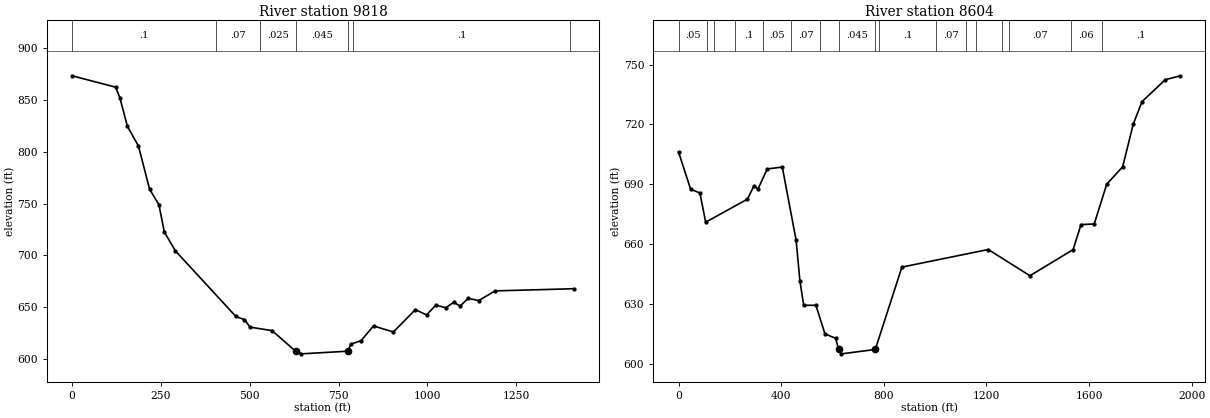
Type RM Length L Ch R = 1 ,9818    ,1235.7,1214.5,1179.6
XS GIS Cut Line= 6
1585753.23223309413543.600376174 1586193.0797786413172.644425169
1586384.18832026413011.468894511  1586672.045028412768.697726503
1586747.89133301 412704.731319011586856.32484317412679.388193846
#Sta/Elev= 30
       0  873.33   122.6  862.34   134.6   852.1   155.5  824.72   186.9  805.47
   218.3  763.75   244.5  748.83   259.7   722.5   290.9  704.29   461.2  640.94
   485.2  637.89   501.1  630.64   563.1  627.29   629.1607.4408   645.7  604.88
   776.3  607.44   784.8  614.22   813.2  617.58   848.6  631.79   904.4  625.98
   966.4  647.51     998  642.47  1024.1     652  1051.7  649.33  1074.4  654.68
  1092.2  650.98  1115.3  658.48  1144.5   656.3  1190.8  665.65  1412.5  667.75
#Mann= 7 ,-1,0
       0      .1       0  404.14     .07       0  527.89    .025       0
   629.1    .045       0   776.3    .025       0  790.39      .1       0
 1401.17     .06       0
Bank Sta=629.1,776.3
XS Rating Curve= 0 ,0
Exp/Cntr(USF)=0,0
Exp/Cntr=0.3,0.1

Type RM Length L Ch R = 1 ,8604    ,,,
XS GIS Cut Line= 6
1586878.74082218414474.1731212011587255.26078555413760.534539578
 1587294.6927735413687.704858059 1587343.3143954413607.549178476
1587444.60946841413440.5573864821588077.87482122412990.425483592
#Sta/Elev= 30
       0  706.21    47.1  687.49    83.3  685.61   105.8  670.94   268.7  682.53
   294.4  689.32   309.4  687.55   345.8  697.66   404.4  698.62   458.2  661.94
     473   641.6   487.8  629.26   535.5  629.24   570.7  614.88   612.4  612.69
   623.9   607.1     635  604.88  766.82  607.07   870.6  648.41  1207.1  657.24
  1369.5  644.08  1537.8  657.17  1568.5  669.72  1620.2  670.08  1668.9  690.03
  1731.1  698.78  1772.2  720.17  1806.6  731.48  1896.8  742.45  1955.7  744.43
#Mann= 17 ,-1,0
       0     .05       0     110      .1       0     140     .06       0
     220      .1       0     330     .05       0     440     .07       0
     550      .1       0   623.9    .045       0  766.82    .025       0
     780      .1       0 1003.44     .07       0 1120.32      .1       0
 1160.32     .07       0 1258.76     .06       0 1288.76     .07       0
 1528.76     .06       0 1648.76      .1       0
Bank Sta=623.9,766.82
XS Rating Curve= 0 ,0
Exp/Cntr(USF)=0,0
Exp/Cntr=0.3,0.1
LCMann Table=0

Chan Stop Cuts=-1
Use User Specified Reach Order=0
Composite Channel Slope=5